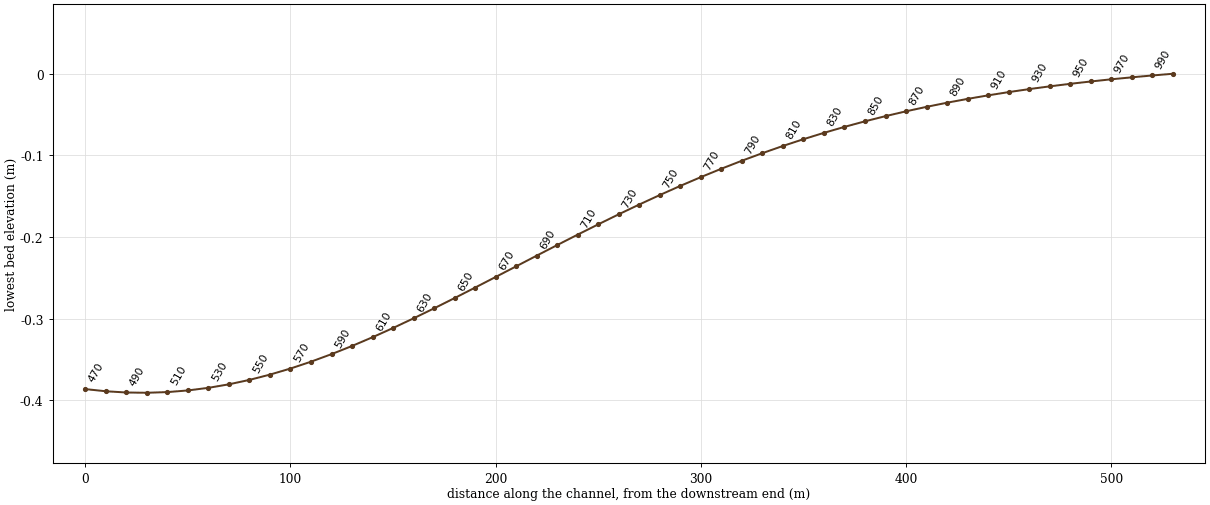
--- macdonald.prj (project) ---

Proj Title=A1F-001 MacDonald backwater dx=10 m
Current Plan=p01
Default Exp/Contr=0,0
SI Units
Geom File=g01
Flow File=f01
Plan File=p01
Y Axis Title=Elevation
X Axis Title(PF)=Main Channel Distance
X Axis Title(XS)=Station
BEGIN DESCRIPTION:
A1F-001 MacDonald backwater dx=10 m
END DESCRIPTION:

--- macdonald.p01 (plan) ---

Plan Title=A1F-001 MacDonald backwater dx=10 m
Program Version=6.60
Short Identifier=dx10
Geom File=g01
Flow File=f01
Subcritical Flow
K Sum by GR= 0
Std Step Tol= .00001
Critical Tol= .00001
Num of Std Step Trials= 40
Max Error Tol= .3
Flow Tol Ratio= .001
Log Output Level= 0
Friction Slope Method= 1

--- macdonald.f01 (steady flow) ---

Flow Title=A1F-001 MacDonald backwater dx=10 m
Program Version=6.60
Number of Profiles= 1
Profile Names=PF 1
River Rch & RM=Channel,Main            ,1000
   20000
Boundary for River Rch & Prof#=Channel,Main            , 1
Up Type= 0
Dn Type= 1
Dn Known WS=0.690867

--- macdonald.g01 (geometry) ---

Geom Title=A1F-001 MacDonald backwater dx=10 m
Program Version=6.60

River Reach=Channel         ,Main
Reach XY= 2
          0.5000          1.0000          0.5000          0.0000

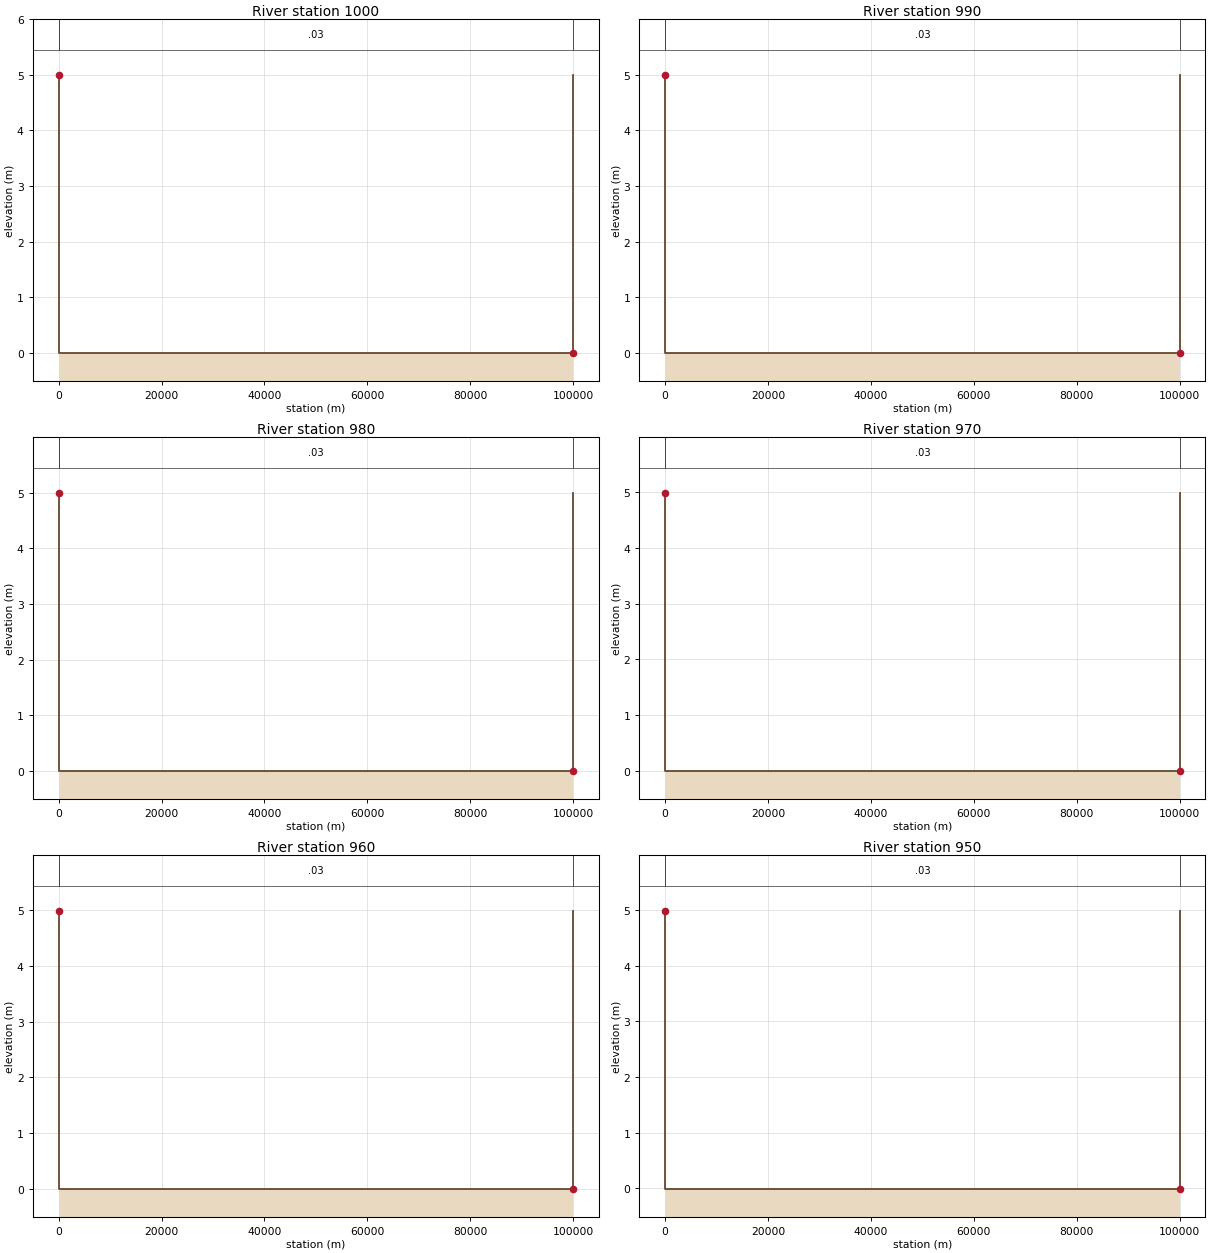
Type RM Length L Ch R = 1 ,1000    ,10,10,10
#Sta/Elev= 4
 0.00000       5 0.00000 0.00000  100000 0.00000  100000       5
#Mann= 3 ,0,0
 0.00000 0.03000 0.00000 0.00000 0.03000 0.00000  100000 0.03000 0.00000
Bank Sta=0,100000
XS Rating Curve= 0 ,0
Exp/Cntr=0,0

Type RM Length L Ch R = 1 ,990     ,10,10,10
#Sta/Elev= 4
 0.00000  4.9979 0.00000-0.00210  100000-0.00210  100000  4.9979
#Mann= 3 ,0,0
 0.00000 0.03000 0.00000 0.00000 0.03000 0.00000  100000 0.03000 0.00000
Bank Sta=0,100000
XS Rating Curve= 0 ,0
Exp/Cntr=0,0

Type RM Length L Ch R = 1 ,980     ,10,10,10
#Sta/Elev= 4
 0.00000 4.99564 0.00000-0.00436  100000-0.00436  100000 4.99564
#Mann= 3 ,0,0
 0.00000 0.03000 0.00000 0.00000 0.03000 0.00000  100000 0.03000 0.00000
Bank Sta=0,100000
XS Rating Curve= 0 ,0
Exp/Cntr=0,0

Type RM Length L Ch R = 1 ,970     ,10,10,10
#Sta/Elev= 4
 0.00000  4.9932 0.00000-0.00680  100000-0.00680  100000  4.9932
#Mann= 3 ,0,0
 0.00000 0.03000 0.00000 0.00000 0.03000 0.00000  100000 0.03000 0.00000
Bank Sta=0,100000
XS Rating Curve= 0 ,0
Exp/Cntr=0,0

Type RM Length L Ch R = 1 ,960     ,10,10,10
#Sta/Elev= 4
 0.00000 4.99055 0.00000-0.00945  100000-0.00945  100000 4.99055
#Mann= 3 ,0,0
 0.00000 0.03000 0.00000 0.00000 0.03000 0.00000  100000 0.03000 0.00000
Bank Sta=0,100000
XS Rating Curve= 0 ,0
Exp/Cntr=0,0

Type RM Length L Ch R = 1 ,950     ,10,10,10
#Sta/Elev= 4
 0.00000 4.98768 0.00000-0.01232  100000-0.01232  100000 4.98768
#Mann= 3 ,0,0
 0.00000 0.03000 0.00000 0.00000 0.03000 0.00000  100000 0.03000 0.00000
Bank Sta=0,100000
XS Rating Curve= 0 ,0
Exp/Cntr=0,0

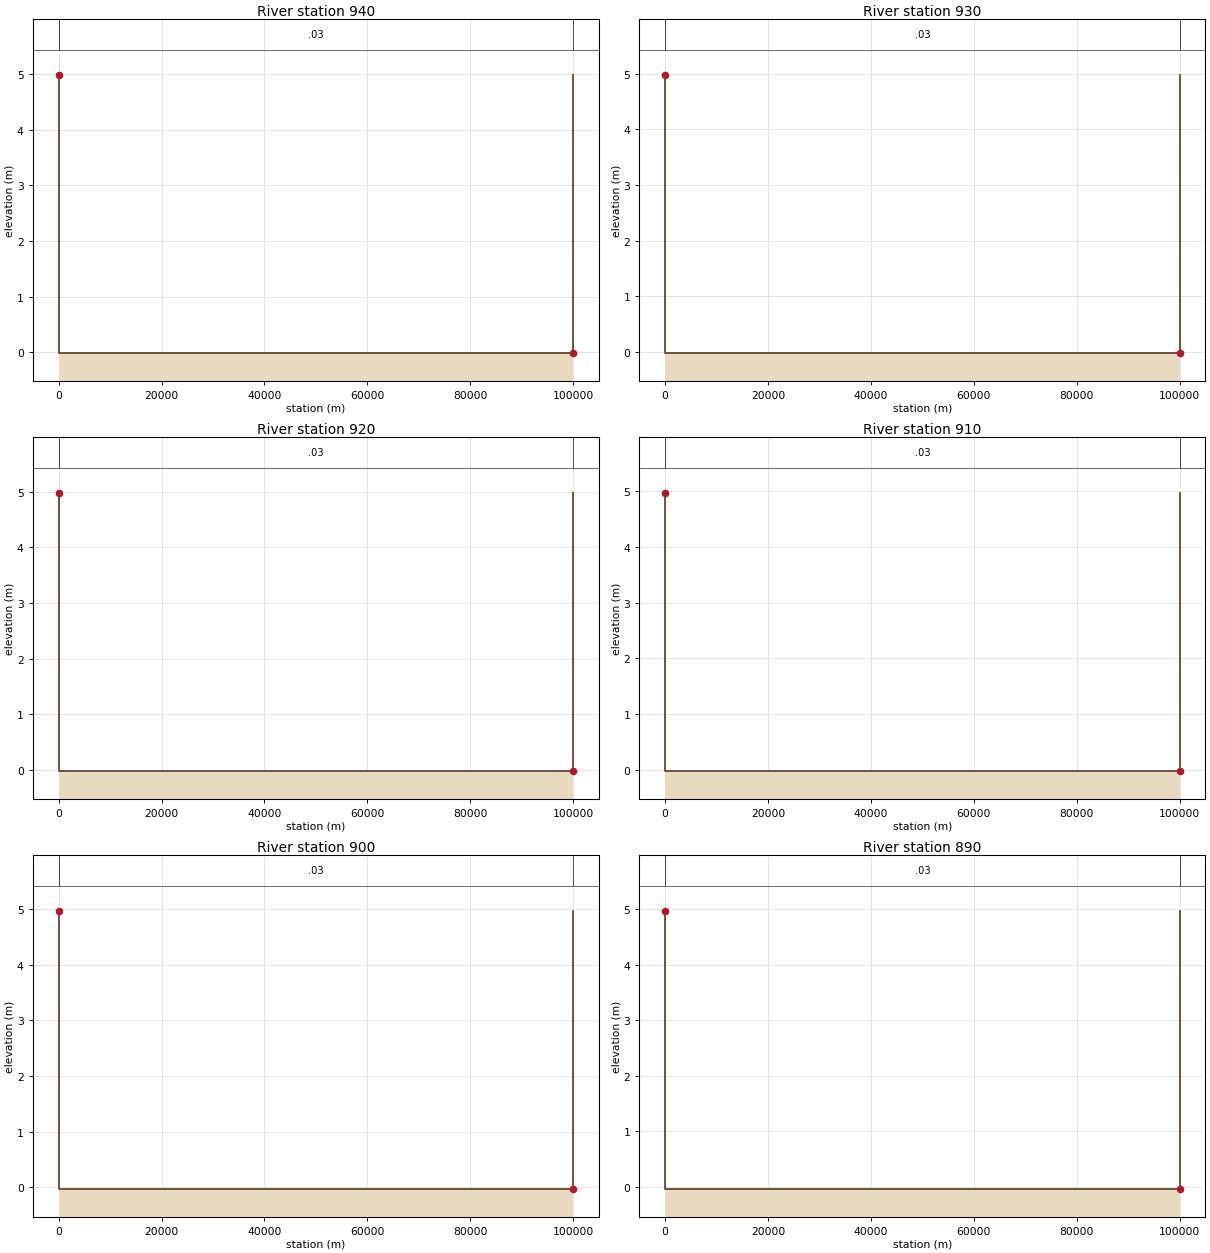
Type RM Length L Ch R = 1 ,940     ,10,10,10
#Sta/Elev= 4
 0.00000 4.98457 0.00000-0.01543  100000-0.01543  100000 4.98457
#Mann= 3 ,0,0
 0.00000 0.03000 0.00000 0.00000 0.03000 0.00000  100000 0.03000 0.00000
Bank Sta=0,100000
XS Rating Curve= 0 ,0
Exp/Cntr=0,0

Type RM Length L Ch R = 1 ,930     ,10,10,10
#Sta/Elev= 4
 0.00000  4.9812 0.00000-0.01880  100000-0.01880  100000  4.9812
#Mann= 3 ,0,0
 0.00000 0.03000 0.00000 0.00000 0.03000 0.00000  100000 0.03000 0.00000
Bank Sta=0,100000
XS Rating Curve= 0 ,0
Exp/Cntr=0,0

Type RM Length L Ch R = 1 ,920     ,10,10,10
#Sta/Elev= 4
 0.00000 4.97753 0.00000-0.02247  100000-0.02247  100000 4.97753
#Mann= 3 ,0,0
 0.00000 0.03000 0.00000 0.00000 0.03000 0.00000  100000 0.03000 0.00000
Bank Sta=0,100000
XS Rating Curve= 0 ,0
Exp/Cntr=0,0

Type RM Length L Ch R = 1 ,910     ,10,10,10
#Sta/Elev= 4
 0.00000 4.97355 0.00000-0.02645  100000-0.02645  100000 4.97355
#Mann= 3 ,0,0
 0.00000 0.03000 0.00000 0.00000 0.03000 0.00000  100000 0.03000 0.00000
Bank Sta=0,100000
XS Rating Curve= 0 ,0
Exp/Cntr=0,0

Type RM Length L Ch R = 1 ,900     ,10,10,10
#Sta/Elev= 4
 0.00000 4.96923 0.00000-0.03077  100000-0.03077  100000 4.96923
#Mann= 3 ,0,0
 0.00000 0.03000 0.00000 0.00000 0.03000 0.00000  100000 0.03000 0.00000
Bank Sta=0,100000
XS Rating Curve= 0 ,0
Exp/Cntr=0,0

Type RM Length L Ch R = 1 ,890     ,10,10,10
#Sta/Elev= 4
 0.00000 4.96455 0.00000-0.03545  100000-0.03545  100000 4.96455
#Mann= 3 ,0,0
 0.00000 0.03000 0.00000 0.00000 0.03000 0.00000  100000 0.03000 0.00000
Bank Sta=0,100000
XS Rating Curve= 0 ,0
Exp/Cntr=0,0

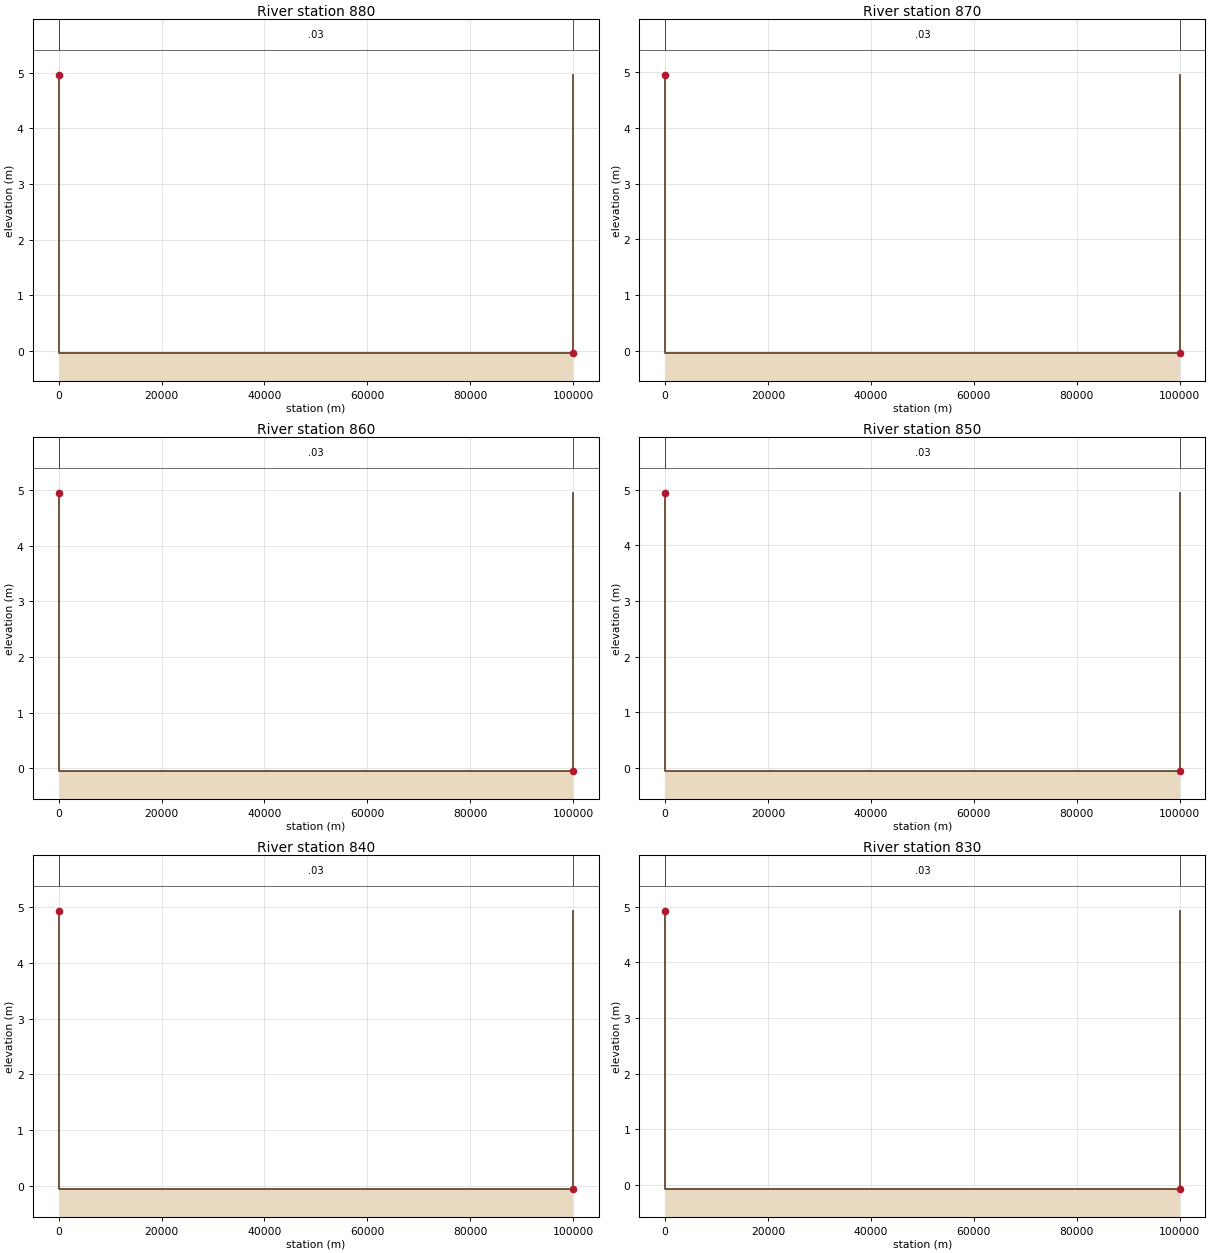
Type RM Length L Ch R = 1 ,880     ,10,10,10
#Sta/Elev= 4
 0.00000 4.95948 0.00000-0.04052  100000-0.04052  100000 4.95948
#Mann= 3 ,0,0
 0.00000 0.03000 0.00000 0.00000 0.03000 0.00000  100000 0.03000 0.00000
Bank Sta=0,100000
XS Rating Curve= 0 ,0
Exp/Cntr=0,0

Type RM Length L Ch R = 1 ,870     ,10,10,10
#Sta/Elev= 4
 0.00000 4.95401 0.00000-0.04599  100000-0.04599  100000 4.95401
#Mann= 3 ,0,0
 0.00000 0.03000 0.00000 0.00000 0.03000 0.00000  100000 0.03000 0.00000
Bank Sta=0,100000
XS Rating Curve= 0 ,0
Exp/Cntr=0,0

Type RM Length L Ch R = 1 ,860     ,10,10,10
#Sta/Elev= 4
 0.00000 4.94811 0.00000-0.05189  100000-0.05189  100000 4.94811
#Mann= 3 ,0,0
 0.00000 0.03000 0.00000 0.00000 0.03000 0.00000  100000 0.03000 0.00000
Bank Sta=0,100000
XS Rating Curve= 0 ,0
Exp/Cntr=0,0

Type RM Length L Ch R = 1 ,850     ,10,10,10
#Sta/Elev= 4
 0.00000 4.94176 0.00000-0.05824  100000-0.05824  100000 4.94176
#Mann= 3 ,0,0
 0.00000 0.03000 0.00000 0.00000 0.03000 0.00000  100000 0.03000 0.00000
Bank Sta=0,100000
XS Rating Curve= 0 ,0
Exp/Cntr=0,0

Type RM Length L Ch R = 1 ,840     ,10,10,10
#Sta/Elev= 4
 0.00000 4.93495 0.00000-0.06505  100000-0.06505  100000 4.93495
#Mann= 3 ,0,0
 0.00000 0.03000 0.00000 0.00000 0.03000 0.00000  100000 0.03000 0.00000
Bank Sta=0,100000
XS Rating Curve= 0 ,0
Exp/Cntr=0,0

Type RM Length L Ch R = 1 ,830     ,10,10,10
#Sta/Elev= 4
 0.00000 4.92765 0.00000-0.07235  100000-0.07235  100000 4.92765
#Mann= 3 ,0,0
 0.00000 0.03000 0.00000 0.00000 0.03000 0.00000  100000 0.03000 0.00000
Bank Sta=0,100000
XS Rating Curve= 0 ,0
Exp/Cntr=0,0

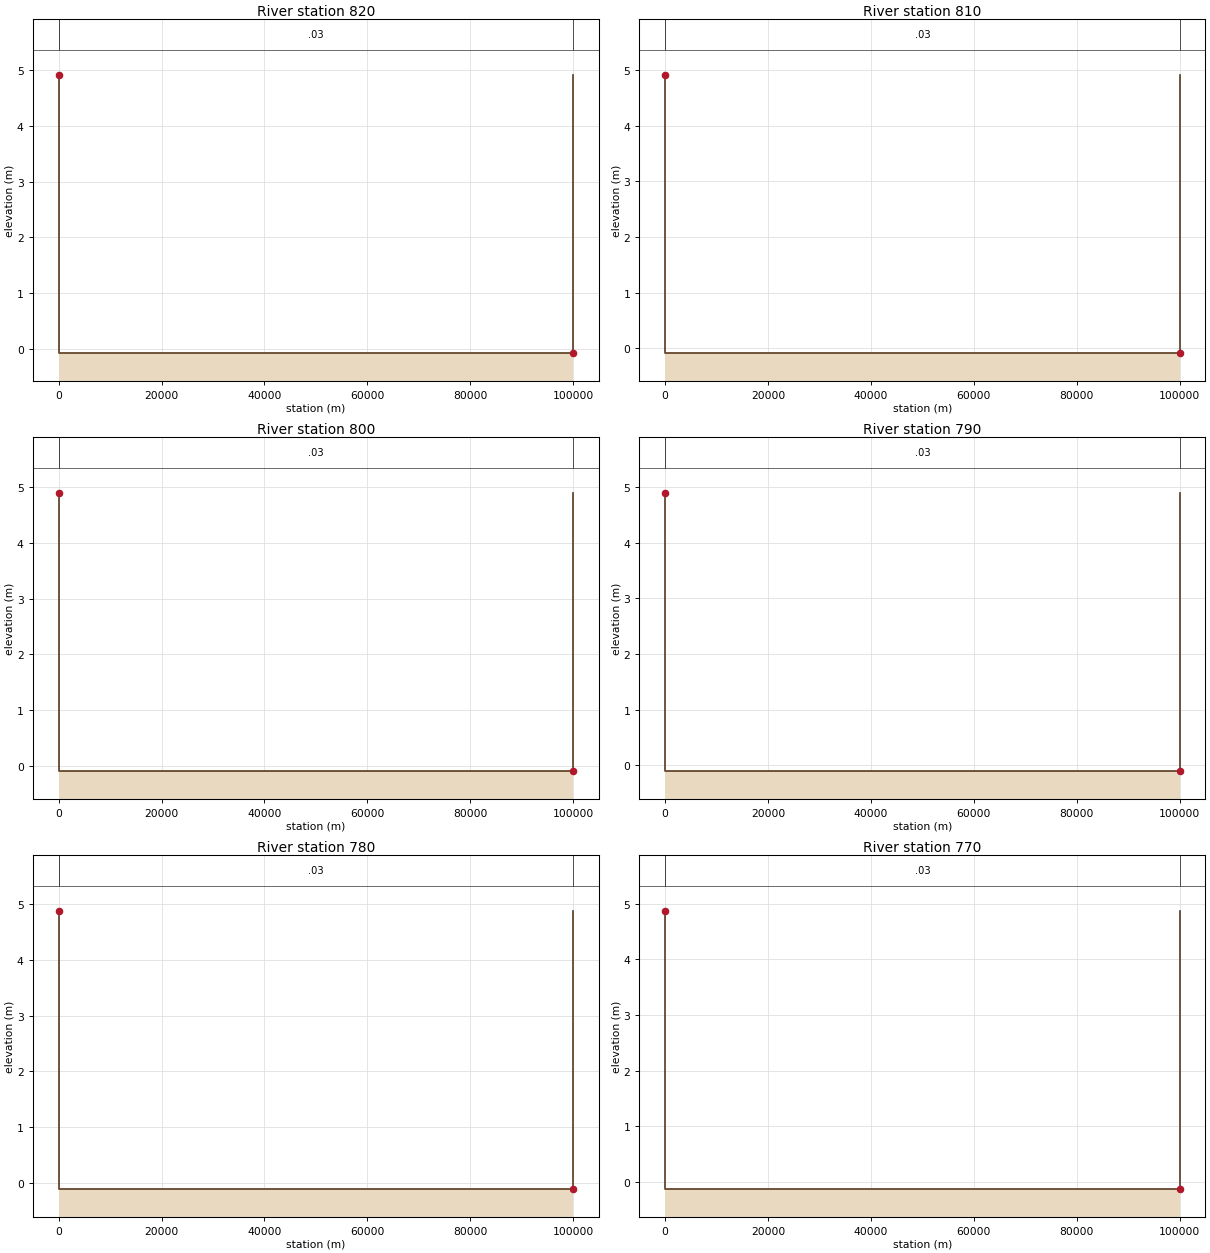
Type RM Length L Ch R = 1 ,820     ,10,10,10
#Sta/Elev= 4
 0.00000 4.91986 0.00000-0.08014  100000-0.08014  100000 4.91986
#Mann= 3 ,0,0
 0.00000 0.03000 0.00000 0.00000 0.03000 0.00000  100000 0.03000 0.00000
Bank Sta=0,100000
XS Rating Curve= 0 ,0
Exp/Cntr=0,0

Type RM Length L Ch R = 1 ,810     ,10,10,10
#Sta/Elev= 4
 0.00000 4.91158 0.00000-0.08842  100000-0.08842  100000 4.91158
#Mann= 3 ,0,0
 0.00000 0.03000 0.00000 0.00000 0.03000 0.00000  100000 0.03000 0.00000
Bank Sta=0,100000
XS Rating Curve= 0 ,0
Exp/Cntr=0,0

Type RM Length L Ch R = 1 ,800     ,10,10,10
#Sta/Elev= 4
 0.00000 4.90278 0.00000-0.09722  100000-0.09722  100000 4.90278
#Mann= 3 ,0,0
 0.00000 0.03000 0.00000 0.00000 0.03000 0.00000  100000 0.03000 0.00000
Bank Sta=0,100000
XS Rating Curve= 0 ,0
Exp/Cntr=0,0

Type RM Length L Ch R = 1 ,790     ,10,10,10
#Sta/Elev= 4
 0.00000 4.89349 0.00000-0.10651  100000-0.10651  100000 4.89349
#Mann= 3 ,0,0
 0.00000 0.03000 0.00000 0.00000 0.03000 0.00000  100000 0.03000 0.00000
Bank Sta=0,100000
XS Rating Curve= 0 ,0
Exp/Cntr=0,0

Type RM Length L Ch R = 1 ,780     ,10,10,10
#Sta/Elev= 4
 0.00000 4.88369 0.00000-0.11631  100000-0.11631  100000 4.88369
#Mann= 3 ,0,0
 0.00000 0.03000 0.00000 0.00000 0.03000 0.00000  100000 0.03000 0.00000
Bank Sta=0,100000
XS Rating Curve= 0 ,0
Exp/Cntr=0,0

Type RM Length L Ch R = 1 ,770     ,10,10,10
#Sta/Elev= 4
 0.00000 4.87342 0.00000-0.12658  100000-0.12658  100000 4.87342
#Mann= 3 ,0,0
 0.00000 0.03000 0.00000 0.00000 0.03000 0.00000  100000 0.03000 0.00000
Bank Sta=0,100000
XS Rating Curve= 0 ,0
Exp/Cntr=0,0

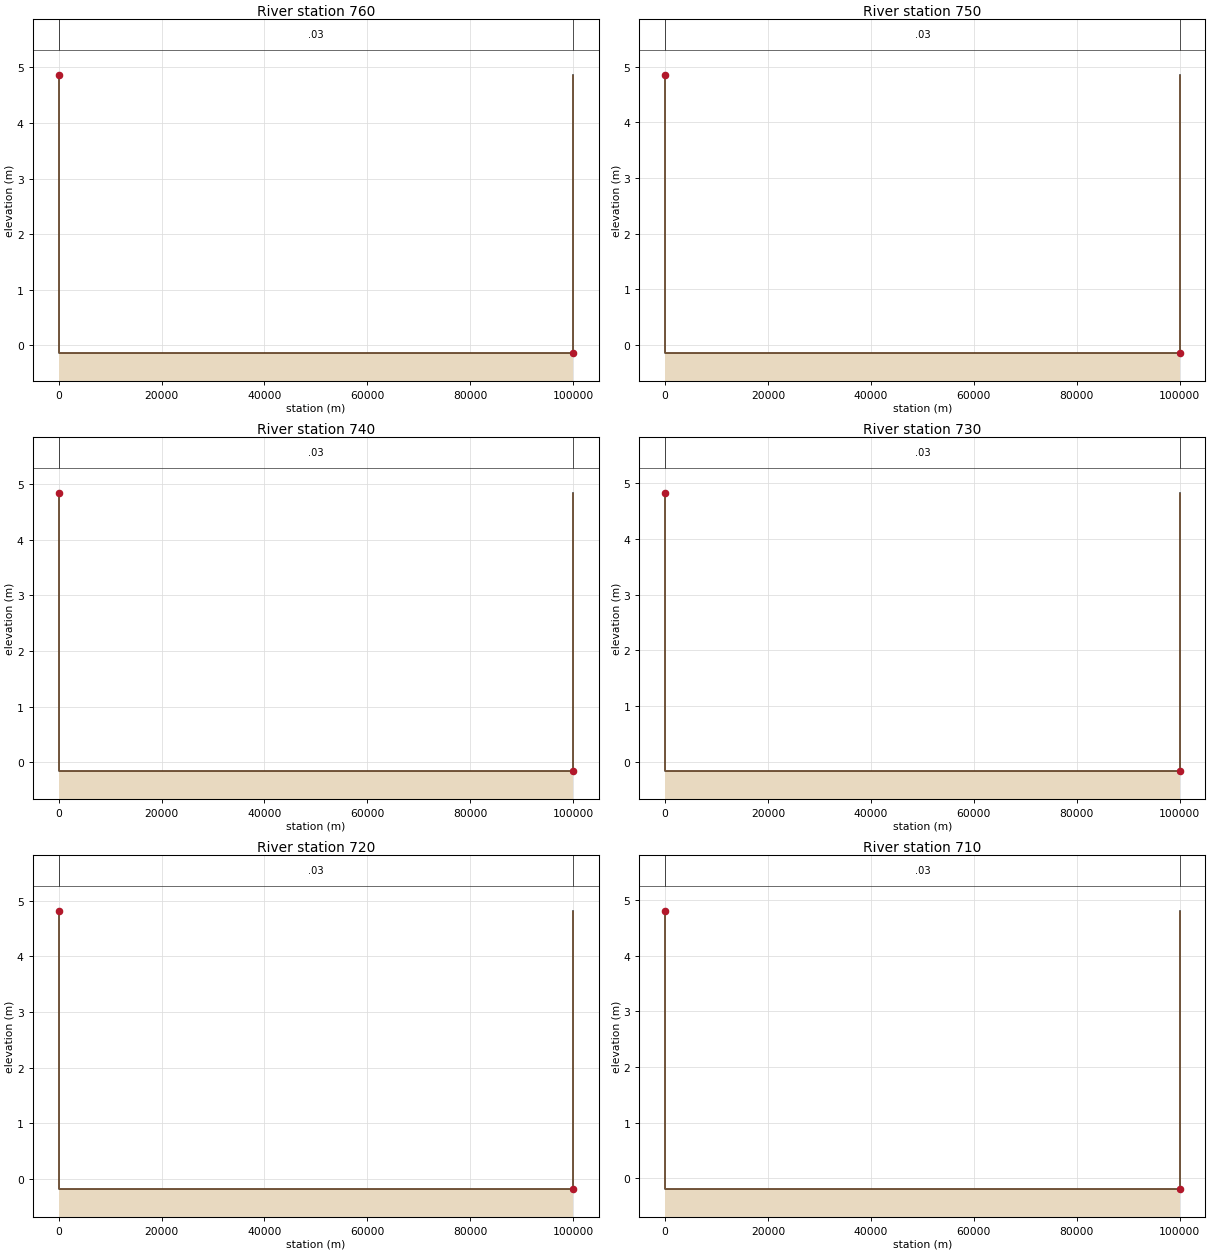
Type RM Length L Ch R = 1 ,760     ,10,10,10
#Sta/Elev= 4
 0.00000 4.86267 0.00000-0.13733  100000-0.13733  100000 4.86267
#Mann= 3 ,0,0
 0.00000 0.03000 0.00000 0.00000 0.03000 0.00000  100000 0.03000 0.00000
Bank Sta=0,100000
XS Rating Curve= 0 ,0
Exp/Cntr=0,0

Type RM Length L Ch R = 1 ,750     ,10,10,10
#Sta/Elev= 4
 0.00000 4.85148 0.00000-0.14852  100000-0.14852  100000 4.85148
#Mann= 3 ,0,0
 0.00000 0.03000 0.00000 0.00000 0.03000 0.00000  100000 0.03000 0.00000
Bank Sta=0,100000
XS Rating Curve= 0 ,0
Exp/Cntr=0,0

Type RM Length L Ch R = 1 ,740     ,10,10,10
#Sta/Elev= 4
 0.00000 4.83988 0.00000-0.16012  100000-0.16012  100000 4.83988
#Mann= 3 ,0,0
 0.00000 0.03000 0.00000 0.00000 0.03000 0.00000  100000 0.03000 0.00000
Bank Sta=0,100000
XS Rating Curve= 0 ,0
Exp/Cntr=0,0

Type RM Length L Ch R = 1 ,730     ,10,10,10
#Sta/Elev= 4
 0.00000  4.8279 0.00000-0.17210  100000-0.17210  100000  4.8279
#Mann= 3 ,0,0
 0.00000 0.03000 0.00000 0.00000 0.03000 0.00000  100000 0.03000 0.00000
Bank Sta=0,100000
XS Rating Curve= 0 ,0
Exp/Cntr=0,0

Type RM Length L Ch R = 1 ,720     ,10,10,10
#Sta/Elev= 4
 0.00000 4.81559 0.00000-0.18441  100000-0.18441  100000 4.81559
#Mann= 3 ,0,0
 0.00000 0.03000 0.00000 0.00000 0.03000 0.00000  100000 0.03000 0.00000
Bank Sta=0,100000
XS Rating Curve= 0 ,0
Exp/Cntr=0,0

Type RM Length L Ch R = 1 ,710     ,10,10,10
#Sta/Elev= 4
 0.00000 4.80301 0.00000-0.19699  100000-0.19699  100000 4.80301
#Mann= 3 ,0,0
 0.00000 0.03000 0.00000 0.00000 0.03000 0.00000  100000 0.03000 0.00000
Bank Sta=0,100000
XS Rating Curve= 0 ,0
Exp/Cntr=0,0

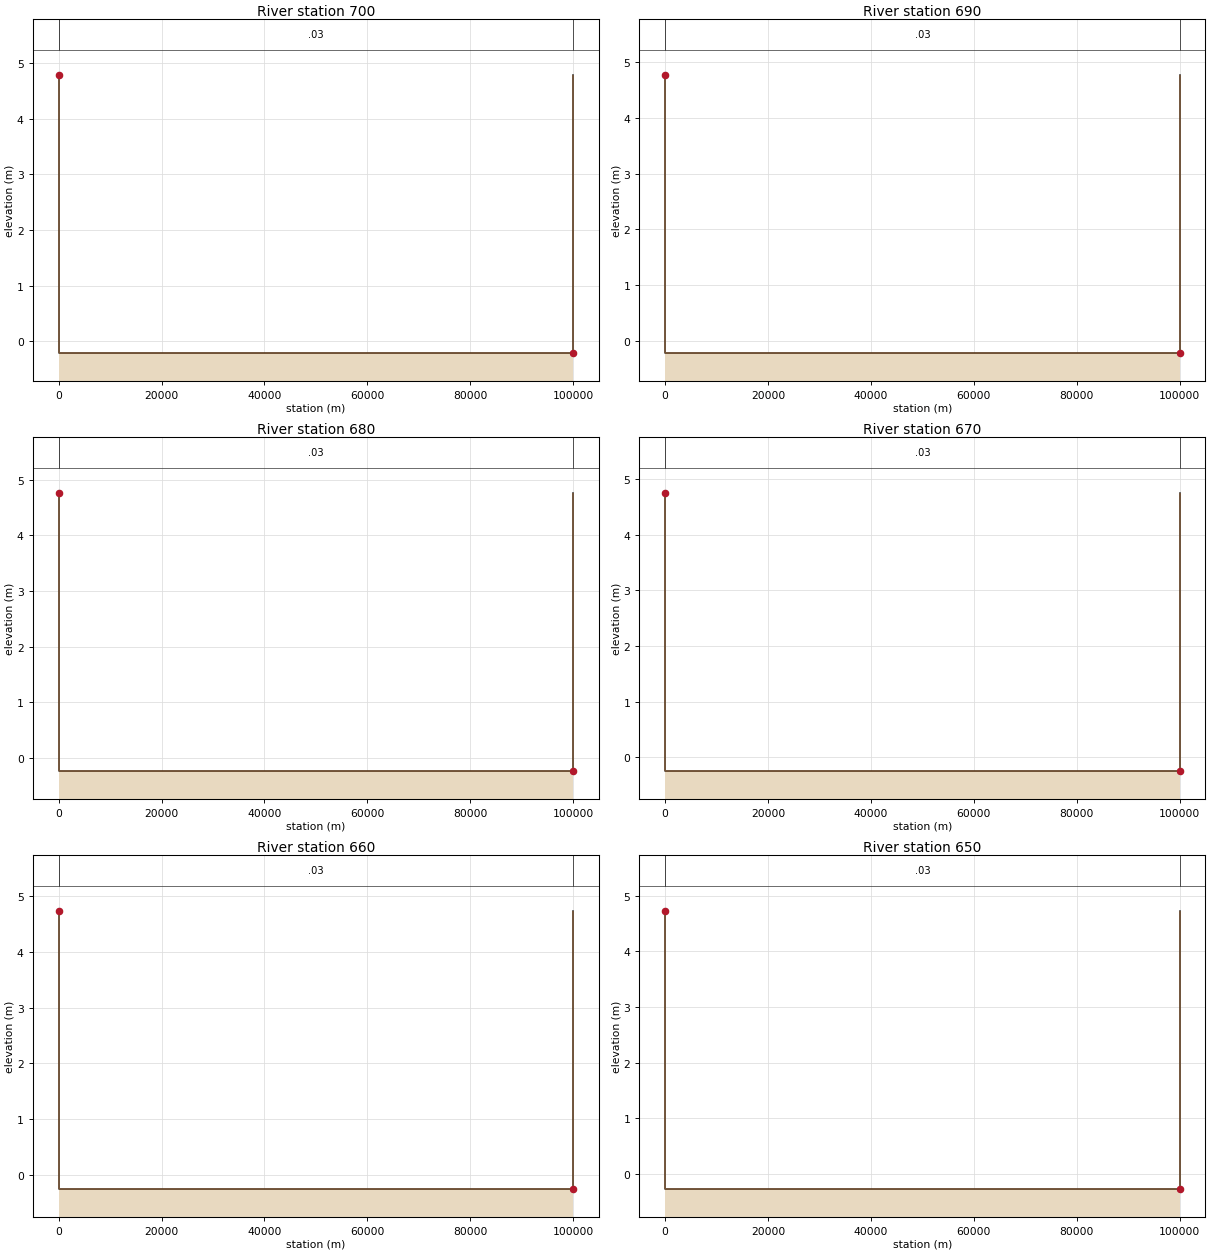
Type RM Length L Ch R = 1 ,700     ,10,10,10
#Sta/Elev= 4
 0.00000  4.7902 0.00000-0.20980  100000-0.20980  100000  4.7902
#Mann= 3 ,0,0
 0.00000 0.03000 0.00000 0.00000 0.03000 0.00000  100000 0.03000 0.00000
Bank Sta=0,100000
XS Rating Curve= 0 ,0
Exp/Cntr=0,0

Type RM Length L Ch R = 1 ,690     ,10,10,10
#Sta/Elev= 4
 0.00000 4.77723 0.00000-0.22277  100000-0.22277  100000 4.77723
#Mann= 3 ,0,0
 0.00000 0.03000 0.00000 0.00000 0.03000 0.00000  100000 0.03000 0.00000
Bank Sta=0,100000
XS Rating Curve= 0 ,0
Exp/Cntr=0,0

Type RM Length L Ch R = 1 ,680     ,10,10,10
#Sta/Elev= 4
 0.00000 4.76418 0.00000-0.23582  100000-0.23582  100000 4.76418
#Mann= 3 ,0,0
 0.00000 0.03000 0.00000 0.00000 0.03000 0.00000  100000 0.03000 0.00000
Bank Sta=0,100000
XS Rating Curve= 0 ,0
Exp/Cntr=0,0

Type RM Length L Ch R = 1 ,670     ,10,10,10
#Sta/Elev= 4
 0.00000 4.75112 0.00000-0.24888  100000-0.24888  100000 4.75112
#Mann= 3 ,0,0
 0.00000 0.03000 0.00000 0.00000 0.03000 0.00000  100000 0.03000 0.00000
Bank Sta=0,100000
XS Rating Curve= 0 ,0
Exp/Cntr=0,0

Type RM Length L Ch R = 1 ,660     ,10,10,10
#Sta/Elev= 4
 0.00000 4.73814 0.00000-0.26186  100000-0.26186  100000 4.73814
#Mann= 3 ,0,0
 0.00000 0.03000 0.00000 0.00000 0.03000 0.00000  100000 0.03000 0.00000
Bank Sta=0,100000
XS Rating Curve= 0 ,0
Exp/Cntr=0,0

Type RM Length L Ch R = 1 ,650     ,10,10,10
#Sta/Elev= 4
 0.00000  4.7253 0.00000-0.27470  100000-0.27470  100000  4.7253
#Mann= 3 ,0,0
 0.00000 0.03000 0.00000 0.00000 0.03000 0.00000  100000 0.03000 0.00000
Bank Sta=0,100000
XS Rating Curve= 0 ,0
Exp/Cntr=0,0

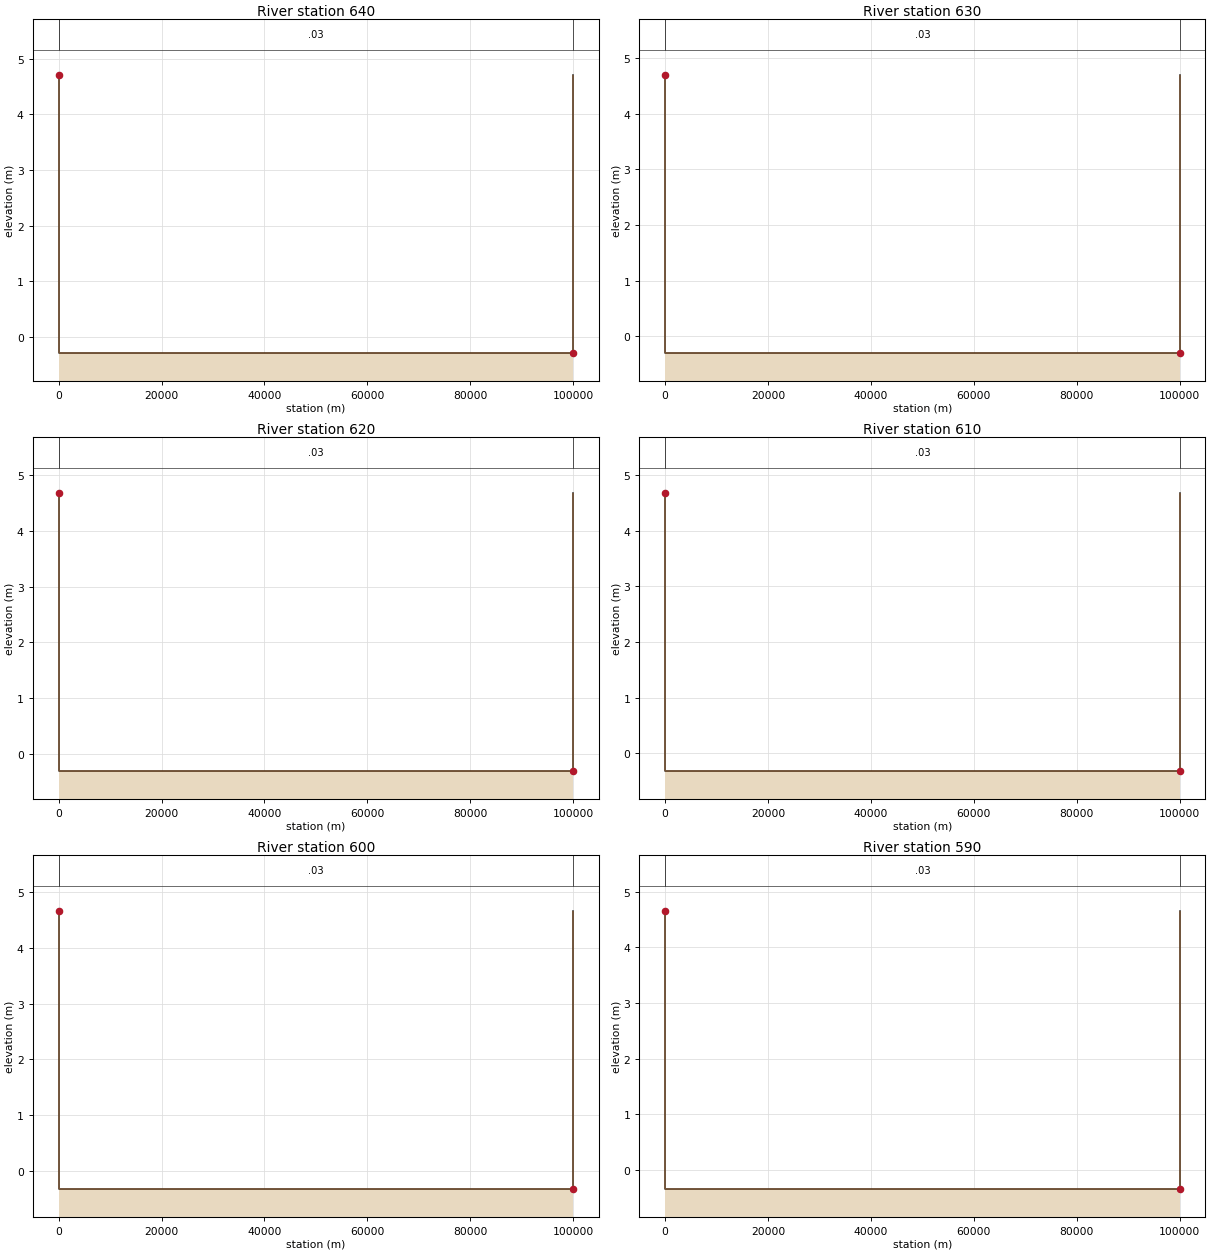
Type RM Length L Ch R = 1 ,640     ,10,10,10
#Sta/Elev= 4
 0.00000 4.71271 0.00000-0.28729  100000-0.28729  100000 4.71271
#Mann= 3 ,0,0
 0.00000 0.03000 0.00000 0.00000 0.03000 0.00000  100000 0.03000 0.00000
Bank Sta=0,100000
XS Rating Curve= 0 ,0
Exp/Cntr=0,0

Type RM Length L Ch R = 1 ,630     ,10,10,10
#Sta/Elev= 4
 0.00000 4.70046 0.00000-0.29954  100000-0.29954  100000 4.70046
#Mann= 3 ,0,0
 0.00000 0.03000 0.00000 0.00000 0.03000 0.00000  100000 0.03000 0.00000
Bank Sta=0,100000
XS Rating Curve= 0 ,0
Exp/Cntr=0,0

Type RM Length L Ch R = 1 ,620     ,10,10,10
#Sta/Elev= 4
 0.00000 4.68863 0.00000-0.31137  100000-0.31137  100000 4.68863
#Mann= 3 ,0,0
 0.00000 0.03000 0.00000 0.00000 0.03000 0.00000  100000 0.03000 0.00000
Bank Sta=0,100000
XS Rating Curve= 0 ,0
Exp/Cntr=0,0

Type RM Length L Ch R = 1 ,610     ,10,10,10
#Sta/Elev= 4
 0.00000 4.67732 0.00000-0.32268  100000-0.32268  100000 4.67732
#Mann= 3 ,0,0
 0.00000 0.03000 0.00000 0.00000 0.03000 0.00000  100000 0.03000 0.00000
Bank Sta=0,100000
XS Rating Curve= 0 ,0
Exp/Cntr=0,0

Type RM Length L Ch R = 1 ,600     ,10,10,10
#Sta/Elev= 4
 0.00000 4.66661 0.00000-0.33339  100000-0.33339  100000 4.66661
#Mann= 3 ,0,0
 0.00000 0.03000 0.00000 0.00000 0.03000 0.00000  100000 0.03000 0.00000
Bank Sta=0,100000
XS Rating Curve= 0 ,0
Exp/Cntr=0,0

Type RM Length L Ch R = 1 ,590     ,10,10,10
#Sta/Elev= 4
 0.00000  4.6566 0.00000-0.34340  100000-0.34340  100000  4.6566
#Mann= 3 ,0,0
 0.00000 0.03000 0.00000 0.00000 0.03000 0.00000  100000 0.03000 0.00000
Bank Sta=0,100000
XS Rating Curve= 0 ,0
Exp/Cntr=0,0

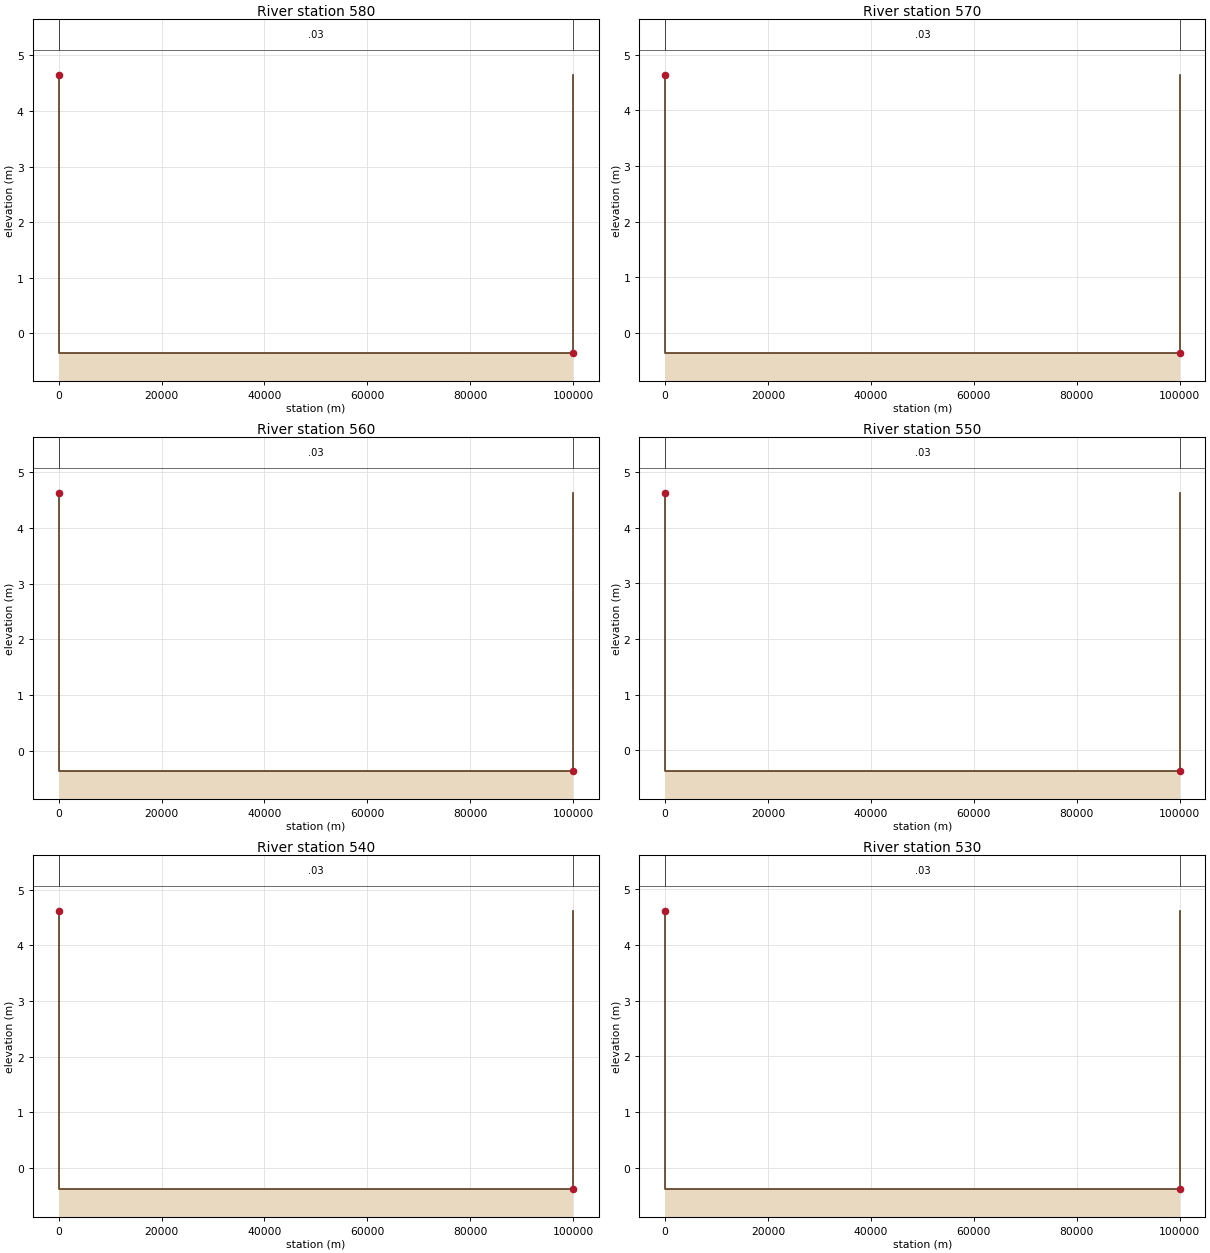
Type RM Length L Ch R = 1 ,580     ,10,10,10
#Sta/Elev= 4
 0.00000 4.64736 0.00000-0.35264  100000-0.35264  100000 4.64736
#Mann= 3 ,0,0
 0.00000 0.03000 0.00000 0.00000 0.03000 0.00000  100000 0.03000 0.00000
Bank Sta=0,100000
XS Rating Curve= 0 ,0
Exp/Cntr=0,0

Type RM Length L Ch R = 1 ,570     ,10,10,10
#Sta/Elev= 4
 0.00000 4.63898 0.00000-0.36102  100000-0.36102  100000 4.63898
#Mann= 3 ,0,0
 0.00000 0.03000 0.00000 0.00000 0.03000 0.00000  100000 0.03000 0.00000
Bank Sta=0,100000
XS Rating Curve= 0 ,0
Exp/Cntr=0,0

Type RM Length L Ch R = 1 ,560     ,10,10,10
#Sta/Elev= 4
 0.00000 4.63153 0.00000-0.36847  100000-0.36847  100000 4.63153
#Mann= 3 ,0,0
 0.00000 0.03000 0.00000 0.00000 0.03000 0.00000  100000 0.03000 0.00000
Bank Sta=0,100000
XS Rating Curve= 0 ,0
Exp/Cntr=0,0

Type RM Length L Ch R = 1 ,550     ,10,10,10
#Sta/Elev= 4
 0.00000 4.62506 0.00000-0.37494  100000-0.37494  100000 4.62506
#Mann= 3 ,0,0
 0.00000 0.03000 0.00000 0.00000 0.03000 0.00000  100000 0.03000 0.00000
Bank Sta=0,100000
XS Rating Curve= 0 ,0
Exp/Cntr=0,0

Type RM Length L Ch R = 1 ,540     ,10,10,10
#Sta/Elev= 4
 0.00000 4.61965 0.00000-0.38035  100000-0.38035  100000 4.61965
#Mann= 3 ,0,0
 0.00000 0.03000 0.00000 0.00000 0.03000 0.00000  100000 0.03000 0.00000
Bank Sta=0,100000
XS Rating Curve= 0 ,0
Exp/Cntr=0,0

Type RM Length L Ch R = 1 ,530     ,10,10,10
#Sta/Elev= 4
 0.00000 4.61534 0.00000-0.38466  100000-0.38466  100000 4.61534
#Mann= 3 ,0,0
 0.00000 0.03000 0.00000 0.00000 0.03000 0.00000  100000 0.03000 0.00000
Bank Sta=0,100000
XS Rating Curve= 0 ,0
Exp/Cntr=0,0

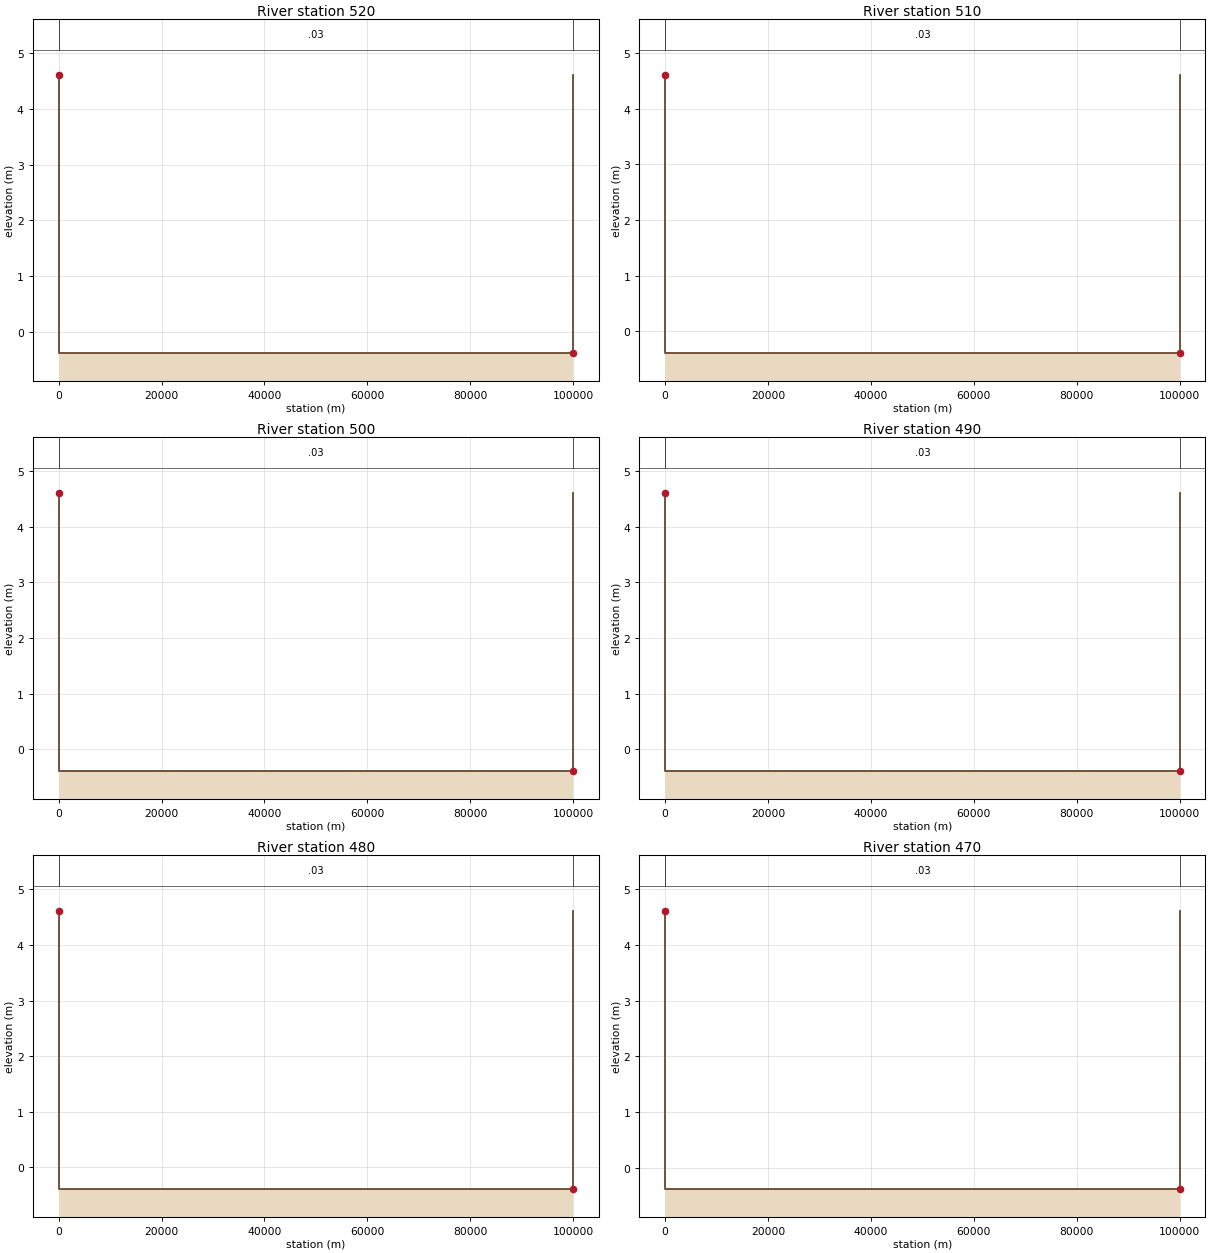
Type RM Length L Ch R = 1 ,520     ,10,10,10
#Sta/Elev= 4
 0.00000 4.61215 0.00000-0.38785  100000-0.38785  100000 4.61215
#Mann= 3 ,0,0
 0.00000 0.03000 0.00000 0.00000 0.03000 0.00000  100000 0.03000 0.00000
Bank Sta=0,100000
XS Rating Curve= 0 ,0
Exp/Cntr=0,0

Type RM Length L Ch R = 1 ,510     ,10,10,10
#Sta/Elev= 4
 0.00000 4.61013 0.00000-0.38987  100000-0.38987  100000 4.61013
#Mann= 3 ,0,0
 0.00000 0.03000 0.00000 0.00000 0.03000 0.00000  100000 0.03000 0.00000
Bank Sta=0,100000
XS Rating Curve= 0 ,0
Exp/Cntr=0,0

Type RM Length L Ch R = 1 ,500     ,10,10,10
#Sta/Elev= 4
 0.00000 4.60929 0.00000-0.39071  100000-0.39071  100000 4.60929
#Mann= 3 ,0,0
 0.00000 0.03000 0.00000 0.00000 0.03000 0.00000  100000 0.03000 0.00000
Bank Sta=0,100000
XS Rating Curve= 0 ,0
Exp/Cntr=0,0

Type RM Length L Ch R = 1 ,490     ,10,10,10
#Sta/Elev= 4
 0.00000 4.60963 0.00000-0.39037  100000-0.39037  100000 4.60963
#Mann= 3 ,0,0
 0.00000 0.03000 0.00000 0.00000 0.03000 0.00000  100000 0.03000 0.00000
Bank Sta=0,100000
XS Rating Curve= 0 ,0
Exp/Cntr=0,0

Type RM Length L Ch R = 1 ,480     ,10,10,10
#Sta/Elev= 4
 0.00000 4.61114 0.00000-0.38886  100000-0.38886  100000 4.61114
#Mann= 3 ,0,0
 0.00000 0.03000 0.00000 0.00000 0.03000 0.00000  100000 0.03000 0.00000
Bank Sta=0,100000
XS Rating Curve= 0 ,0
Exp/Cntr=0,0

Type RM Length L Ch R = 1 ,470     ,10,10,10
#Sta/Elev= 4
 0.00000 4.61381 0.00000-0.38619  100000-0.38619  100000 4.61381
#Mann= 3 ,0,0
 0.00000 0.03000 0.00000 0.00000 0.03000 0.00000  100000 0.03000 0.00000
Bank Sta=0,100000
XS Rating Curve= 0 ,0
Exp/Cntr=0,0