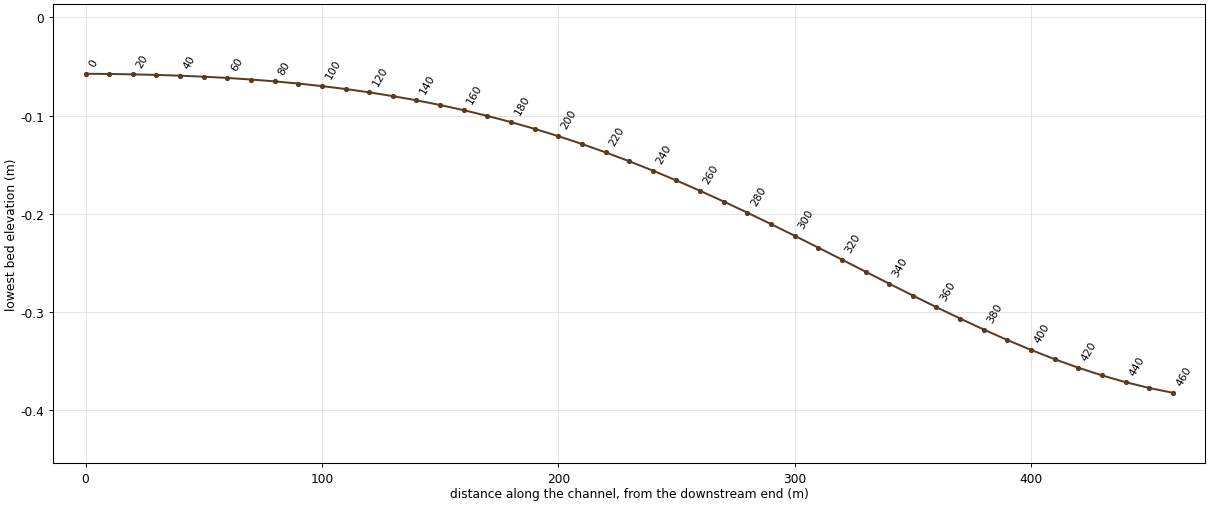
HEC-RAS study macdonald.prj: A1F-001 MacDonald backwater dx=10 m

--- macdonald.g01 (geometry) --- (continued)

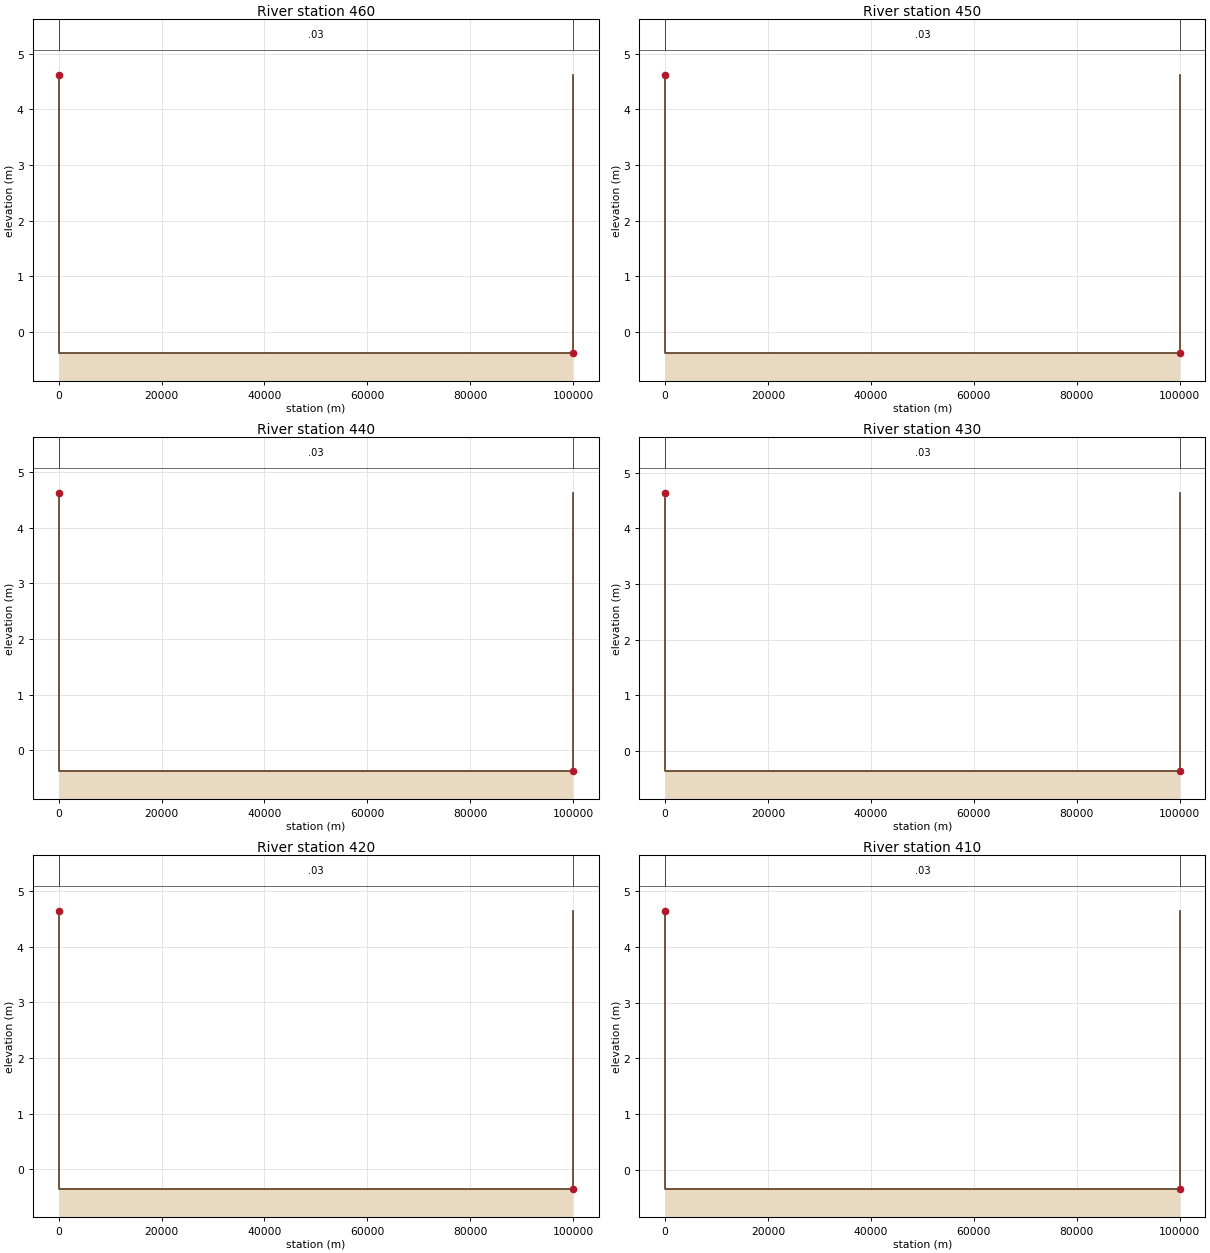
Type RM Length L Ch R = 1 ,460     ,10,10,10
#Sta/Elev= 4
 0.00000 4.61761 0.00000-0.38239  100000-0.38239  100000 4.61761
#Mann= 3 ,0,0
 0.00000 0.03000 0.00000 0.00000 0.03000 0.00000  100000 0.03000 0.00000
Bank Sta=0,100000
XS Rating Curve= 0 ,0
Exp/Cntr=0,0

Type RM Length L Ch R = 1 ,450     ,10,10,10
#Sta/Elev= 4
 0.00000  4.6225 0.00000-0.37750  100000-0.37750  100000  4.6225
#Mann= 3 ,0,0
 0.00000 0.03000 0.00000 0.00000 0.03000 0.00000  100000 0.03000 0.00000
Bank Sta=0,100000
XS Rating Curve= 0 ,0
Exp/Cntr=0,0

Type RM Length L Ch R = 1 ,440     ,10,10,10
#Sta/Elev= 4
 0.00000 4.62843 0.00000-0.37157  100000-0.37157  100000 4.62843
#Mann= 3 ,0,0
 0.00000 0.03000 0.00000 0.00000 0.03000 0.00000  100000 0.03000 0.00000
Bank Sta=0,100000
XS Rating Curve= 0 ,0
Exp/Cntr=0,0

Type RM Length L Ch R = 1 ,430     ,10,10,10
#Sta/Elev= 4
 0.00000 4.63534 0.00000-0.36466  100000-0.36466  100000 4.63534
#Mann= 3 ,0,0
 0.00000 0.03000 0.00000 0.00000 0.03000 0.00000  100000 0.03000 0.00000
Bank Sta=0,100000
XS Rating Curve= 0 ,0
Exp/Cntr=0,0

Type RM Length L Ch R = 1 ,420     ,10,10,10
#Sta/Elev= 4
 0.00000 4.64317 0.00000-0.35683  100000-0.35683  100000 4.64317
#Mann= 3 ,0,0
 0.00000 0.03000 0.00000 0.00000 0.03000 0.00000  100000 0.03000 0.00000
Bank Sta=0,100000
XS Rating Curve= 0 ,0
Exp/Cntr=0,0

Type RM Length L Ch R = 1 ,410     ,10,10,10
#Sta/Elev= 4
 0.00000 4.65183 0.00000-0.34817  100000-0.34817  100000 4.65183
#Mann= 3 ,0,0
 0.00000 0.03000 0.00000 0.00000 0.03000 0.00000  100000 0.03000 0.00000
Bank Sta=0,100000
XS Rating Curve= 0 ,0
Exp/Cntr=0,0

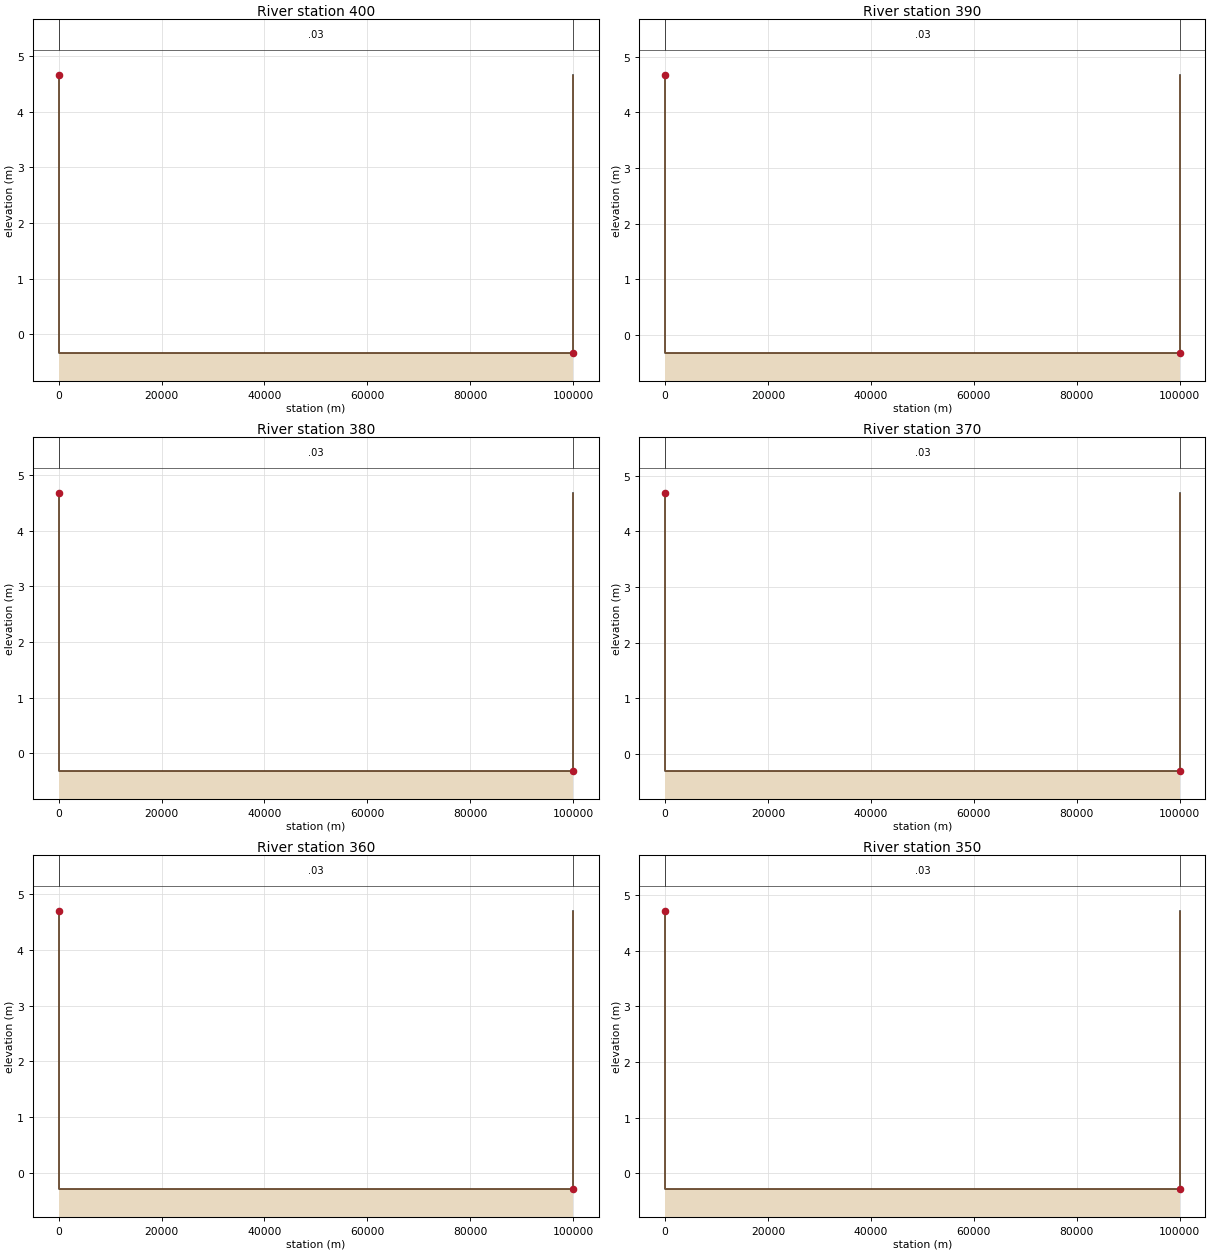
Type RM Length L Ch R = 1 ,400     ,10,10,10
#Sta/Elev= 4
 0.00000 4.66126 0.00000-0.33874  100000-0.33874  100000 4.66126
#Mann= 3 ,0,0
 0.00000 0.03000 0.00000 0.00000 0.03000 0.00000  100000 0.03000 0.00000
Bank Sta=0,100000
XS Rating Curve= 0 ,0
Exp/Cntr=0,0

Type RM Length L Ch R = 1 ,390     ,10,10,10
#Sta/Elev= 4
 0.00000 4.67136 0.00000-0.32864  100000-0.32864  100000 4.67136
#Mann= 3 ,0,0
 0.00000 0.03000 0.00000 0.00000 0.03000 0.00000  100000 0.03000 0.00000
Bank Sta=0,100000
XS Rating Curve= 0 ,0
Exp/Cntr=0,0

Type RM Length L Ch R = 1 ,380     ,10,10,10
#Sta/Elev= 4
 0.00000 4.68204 0.00000-0.31796  100000-0.31796  100000 4.68204
#Mann= 3 ,0,0
 0.00000 0.03000 0.00000 0.00000 0.03000 0.00000  100000 0.03000 0.00000
Bank Sta=0,100000
XS Rating Curve= 0 ,0
Exp/Cntr=0,0

Type RM Length L Ch R = 1 ,370     ,10,10,10
#Sta/Elev= 4
 0.00000 4.69322 0.00000-0.30678  100000-0.30678  100000 4.69322
#Mann= 3 ,0,0
 0.00000 0.03000 0.00000 0.00000 0.03000 0.00000  100000 0.03000 0.00000
Bank Sta=0,100000
XS Rating Curve= 0 ,0
Exp/Cntr=0,0

Type RM Length L Ch R = 1 ,360     ,10,10,10
#Sta/Elev= 4
 0.00000 4.70479 0.00000-0.29521  100000-0.29521  100000 4.70479
#Mann= 3 ,0,0
 0.00000 0.03000 0.00000 0.00000 0.03000 0.00000  100000 0.03000 0.00000
Bank Sta=0,100000
XS Rating Curve= 0 ,0
Exp/Cntr=0,0

Type RM Length L Ch R = 1 ,350     ,10,10,10
#Sta/Elev= 4
 0.00000 4.71668 0.00000-0.28332  100000-0.28332  100000 4.71668
#Mann= 3 ,0,0
 0.00000 0.03000 0.00000 0.00000 0.03000 0.00000  100000 0.03000 0.00000
Bank Sta=0,100000
XS Rating Curve= 0 ,0
Exp/Cntr=0,0

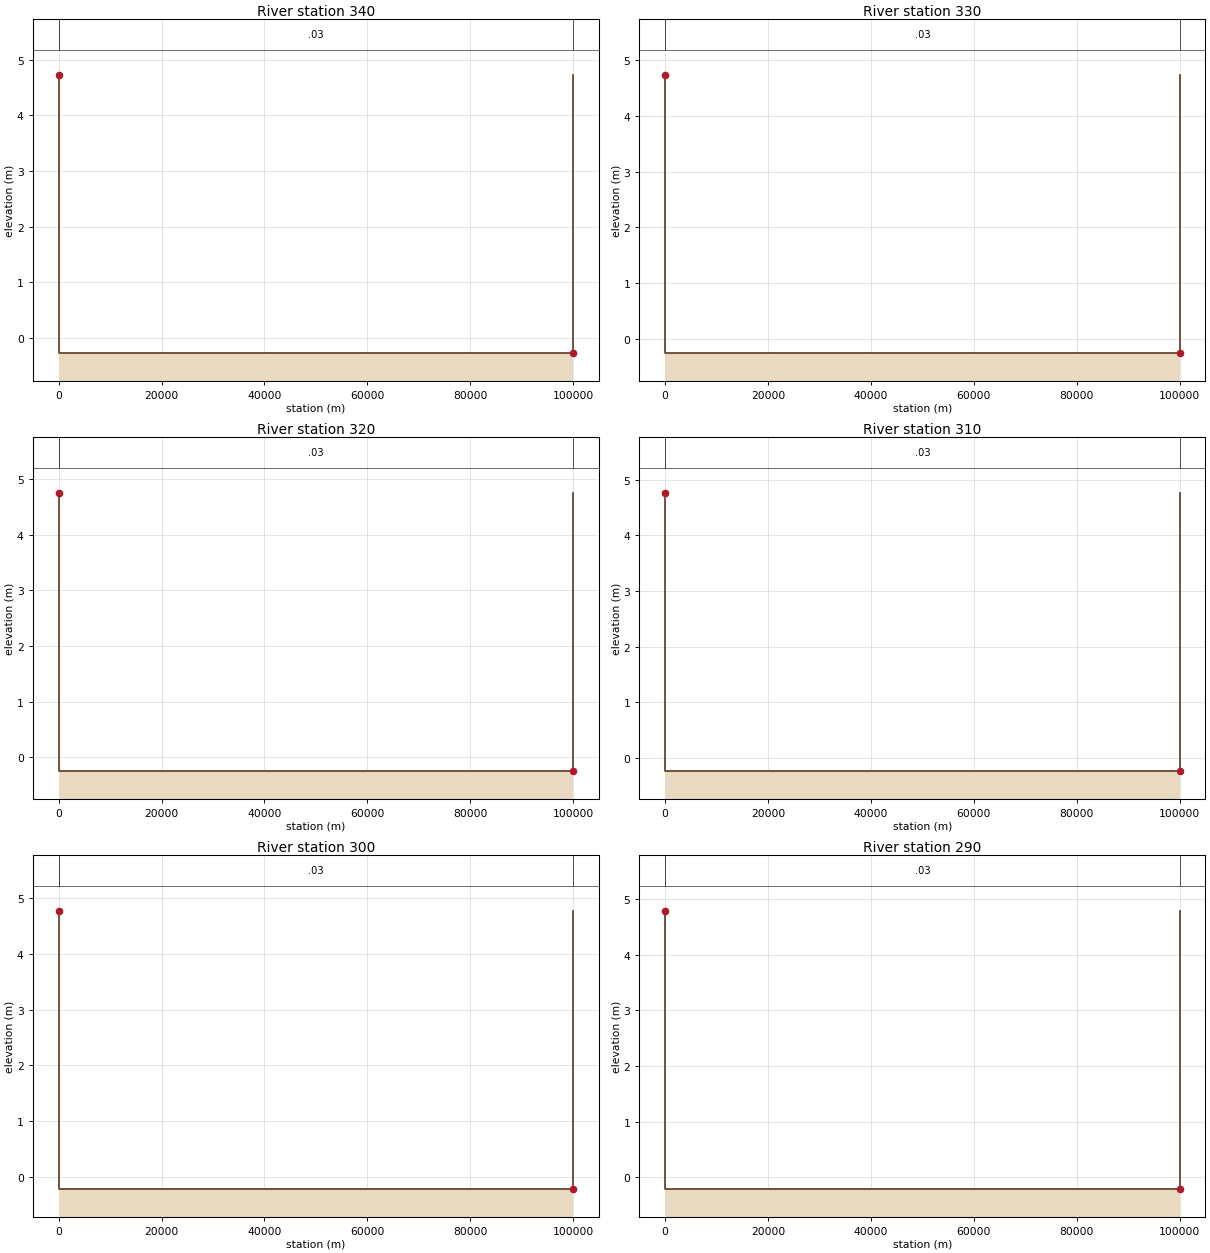
Type RM Length L Ch R = 1 ,340     ,10,10,10
#Sta/Elev= 4
 0.00000 4.72878 0.00000-0.27122  100000-0.27122  100000 4.72878
#Mann= 3 ,0,0
 0.00000 0.03000 0.00000 0.00000 0.03000 0.00000  100000 0.03000 0.00000
Bank Sta=0,100000
XS Rating Curve= 0 ,0
Exp/Cntr=0,0

Type RM Length L Ch R = 1 ,330     ,10,10,10
#Sta/Elev= 4
 0.00000   4.741 0.00000-0.25900  100000-0.25900  100000   4.741
#Mann= 3 ,0,0
 0.00000 0.03000 0.00000 0.00000 0.03000 0.00000  100000 0.03000 0.00000
Bank Sta=0,100000
XS Rating Curve= 0 ,0
Exp/Cntr=0,0

Type RM Length L Ch R = 1 ,320     ,10,10,10
#Sta/Elev= 4
 0.00000 4.75326 0.00000-0.24674  100000-0.24674  100000 4.75326
#Mann= 3 ,0,0
 0.00000 0.03000 0.00000 0.00000 0.03000 0.00000  100000 0.03000 0.00000
Bank Sta=0,100000
XS Rating Curve= 0 ,0
Exp/Cntr=0,0

Type RM Length L Ch R = 1 ,310     ,10,10,10
#Sta/Elev= 4
 0.00000 4.76547 0.00000-0.23453  100000-0.23453  100000 4.76547
#Mann= 3 ,0,0
 0.00000 0.03000 0.00000 0.00000 0.03000 0.00000  100000 0.03000 0.00000
Bank Sta=0,100000
XS Rating Curve= 0 ,0
Exp/Cntr=0,0

Type RM Length L Ch R = 1 ,300     ,10,10,10
#Sta/Elev= 4
 0.00000 4.77756 0.00000-0.22244  100000-0.22244  100000 4.77756
#Mann= 3 ,0,0
 0.00000 0.03000 0.00000 0.00000 0.03000 0.00000  100000 0.03000 0.00000
Bank Sta=0,100000
XS Rating Curve= 0 ,0
Exp/Cntr=0,0

Type RM Length L Ch R = 1 ,290     ,10,10,10
#Sta/Elev= 4
 0.00000 4.78945 0.00000-0.21055  100000-0.21055  100000 4.78945
#Mann= 3 ,0,0
 0.00000 0.03000 0.00000 0.00000 0.03000 0.00000  100000 0.03000 0.00000
Bank Sta=0,100000
XS Rating Curve= 0 ,0
Exp/Cntr=0,0

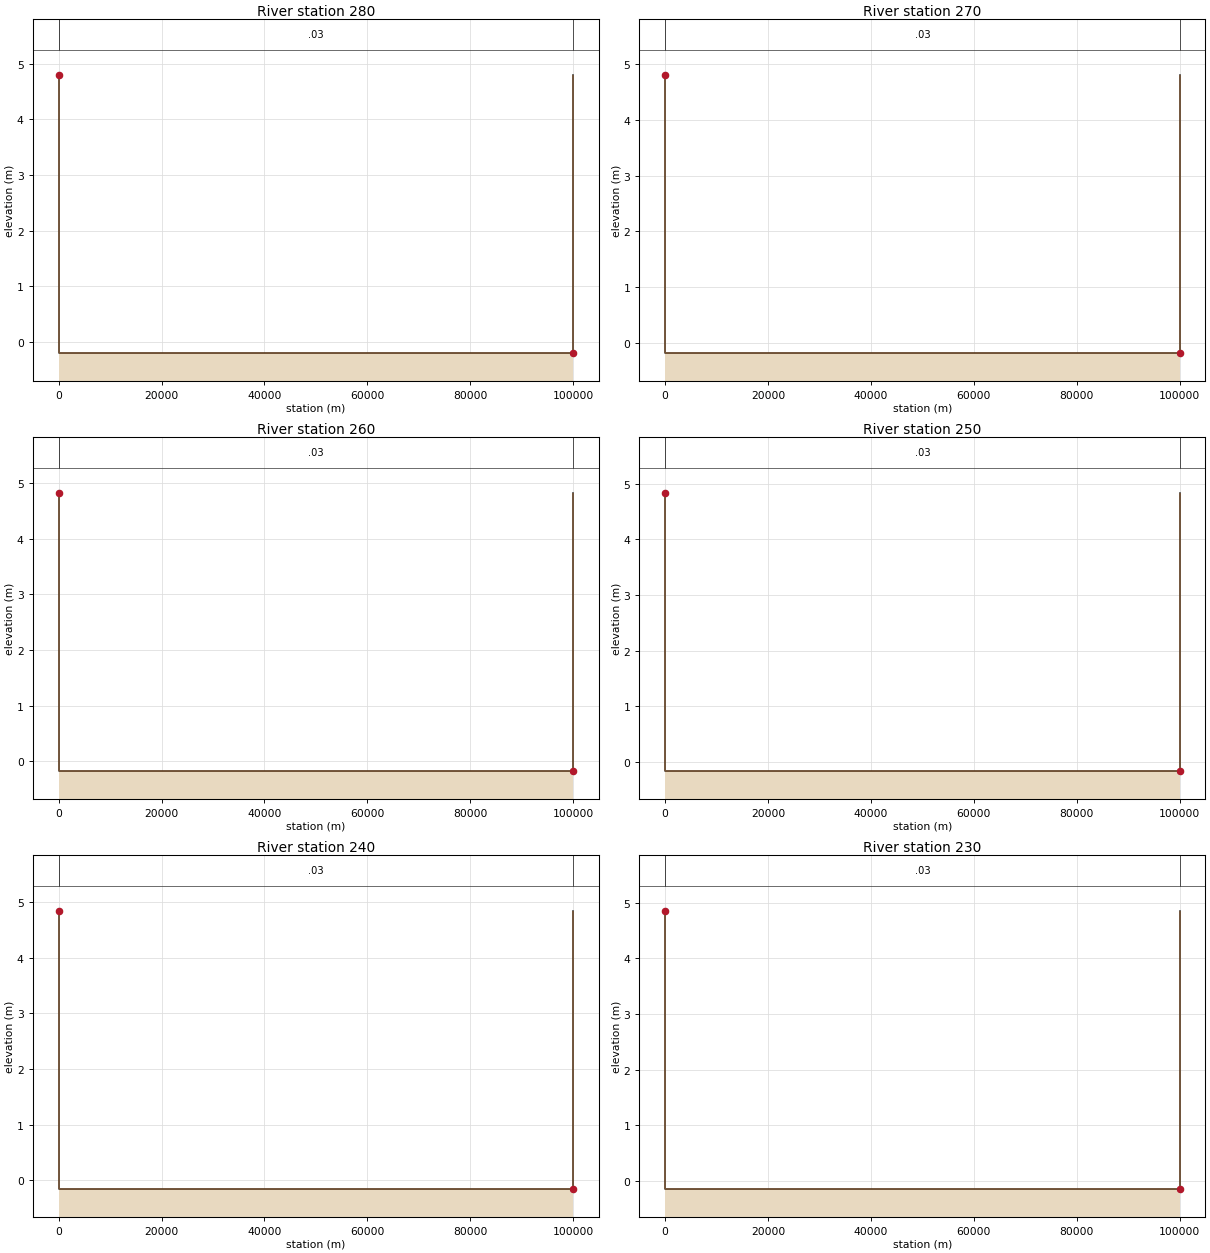
Type RM Length L Ch R = 1 ,280     ,10,10,10
#Sta/Elev= 4
 0.00000 4.80108 0.00000-0.19892  100000-0.19892  100000 4.80108
#Mann= 3 ,0,0
 0.00000 0.03000 0.00000 0.00000 0.03000 0.00000  100000 0.03000 0.00000
Bank Sta=0,100000
XS Rating Curve= 0 ,0
Exp/Cntr=0,0

Type RM Length L Ch R = 1 ,270     ,10,10,10
#Sta/Elev= 4
 0.00000 4.81239 0.00000-0.18761  100000-0.18761  100000 4.81239
#Mann= 3 ,0,0
 0.00000 0.03000 0.00000 0.00000 0.03000 0.00000  100000 0.03000 0.00000
Bank Sta=0,100000
XS Rating Curve= 0 ,0
Exp/Cntr=0,0

Type RM Length L Ch R = 1 ,260     ,10,10,10
#Sta/Elev= 4
 0.00000 4.82333 0.00000-0.17667  100000-0.17667  100000 4.82333
#Mann= 3 ,0,0
 0.00000 0.03000 0.00000 0.00000 0.03000 0.00000  100000 0.03000 0.00000
Bank Sta=0,100000
XS Rating Curve= 0 ,0
Exp/Cntr=0,0

Type RM Length L Ch R = 1 ,250     ,10,10,10
#Sta/Elev= 4
 0.00000 4.83384 0.00000-0.16616  100000-0.16616  100000 4.83384
#Mann= 3 ,0,0
 0.00000 0.03000 0.00000 0.00000 0.03000 0.00000  100000 0.03000 0.00000
Bank Sta=0,100000
XS Rating Curve= 0 ,0
Exp/Cntr=0,0

Type RM Length L Ch R = 1 ,240     ,10,10,10
#Sta/Elev= 4
 0.00000  4.8439 0.00000-0.15610  100000-0.15610  100000  4.8439
#Mann= 3 ,0,0
 0.00000 0.03000 0.00000 0.00000 0.03000 0.00000  100000 0.03000 0.00000
Bank Sta=0,100000
XS Rating Curve= 0 ,0
Exp/Cntr=0,0

Type RM Length L Ch R = 1 ,230     ,10,10,10
#Sta/Elev= 4
 0.00000 4.85346 0.00000-0.14654  100000-0.14654  100000 4.85346
#Mann= 3 ,0,0
 0.00000 0.03000 0.00000 0.00000 0.03000 0.00000  100000 0.03000 0.00000
Bank Sta=0,100000
XS Rating Curve= 0 ,0
Exp/Cntr=0,0

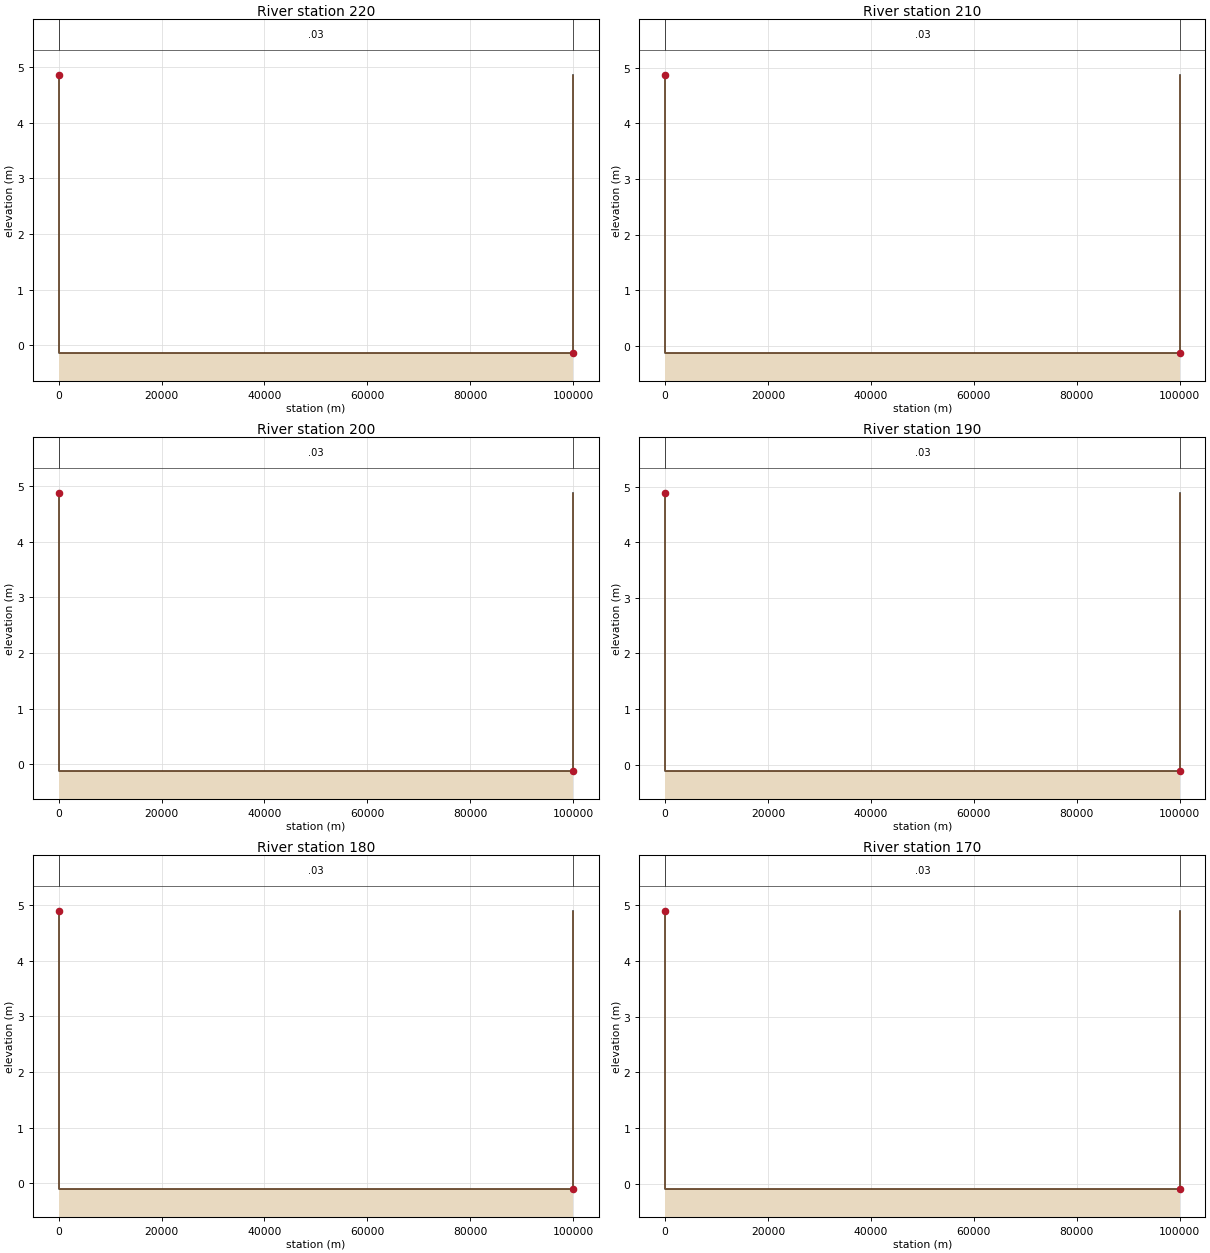
Type RM Length L Ch R = 1 ,220     ,10,10,10
#Sta/Elev= 4
 0.00000 4.86251 0.00000-0.13749  100000-0.13749  100000 4.86251
#Mann= 3 ,0,0
 0.00000 0.03000 0.00000 0.00000 0.03000 0.00000  100000 0.03000 0.00000
Bank Sta=0,100000
XS Rating Curve= 0 ,0
Exp/Cntr=0,0

Type RM Length L Ch R = 1 ,210     ,10,10,10
#Sta/Elev= 4
 0.00000 4.87103 0.00000-0.12897  100000-0.12897  100000 4.87103
#Mann= 3 ,0,0
 0.00000 0.03000 0.00000 0.00000 0.03000 0.00000  100000 0.03000 0.00000
Bank Sta=0,100000
XS Rating Curve= 0 ,0
Exp/Cntr=0,0

Type RM Length L Ch R = 1 ,200     ,10,10,10
#Sta/Elev= 4
 0.00000 4.87901 0.00000-0.12099  100000-0.12099  100000 4.87901
#Mann= 3 ,0,0
 0.00000 0.03000 0.00000 0.00000 0.03000 0.00000  100000 0.03000 0.00000
Bank Sta=0,100000
XS Rating Curve= 0 ,0
Exp/Cntr=0,0

Type RM Length L Ch R = 1 ,190     ,10,10,10
#Sta/Elev= 4
 0.00000 4.88643 0.00000-0.11357  100000-0.11357  100000 4.88643
#Mann= 3 ,0,0
 0.00000 0.03000 0.00000 0.00000 0.03000 0.00000  100000 0.03000 0.00000
Bank Sta=0,100000
XS Rating Curve= 0 ,0
Exp/Cntr=0,0

Type RM Length L Ch R = 1 ,180     ,10,10,10
#Sta/Elev= 4
 0.00000 4.89331 0.00000-0.10669  100000-0.10669  100000 4.89331
#Mann= 3 ,0,0
 0.00000 0.03000 0.00000 0.00000 0.03000 0.00000  100000 0.03000 0.00000
Bank Sta=0,100000
XS Rating Curve= 0 ,0
Exp/Cntr=0,0

Type RM Length L Ch R = 1 ,170     ,10,10,10
#Sta/Elev= 4
 0.00000 4.89964 0.00000-0.10036  100000-0.10036  100000 4.89964
#Mann= 3 ,0,0
 0.00000 0.03000 0.00000 0.00000 0.03000 0.00000  100000 0.03000 0.00000
Bank Sta=0,100000
XS Rating Curve= 0 ,0
Exp/Cntr=0,0

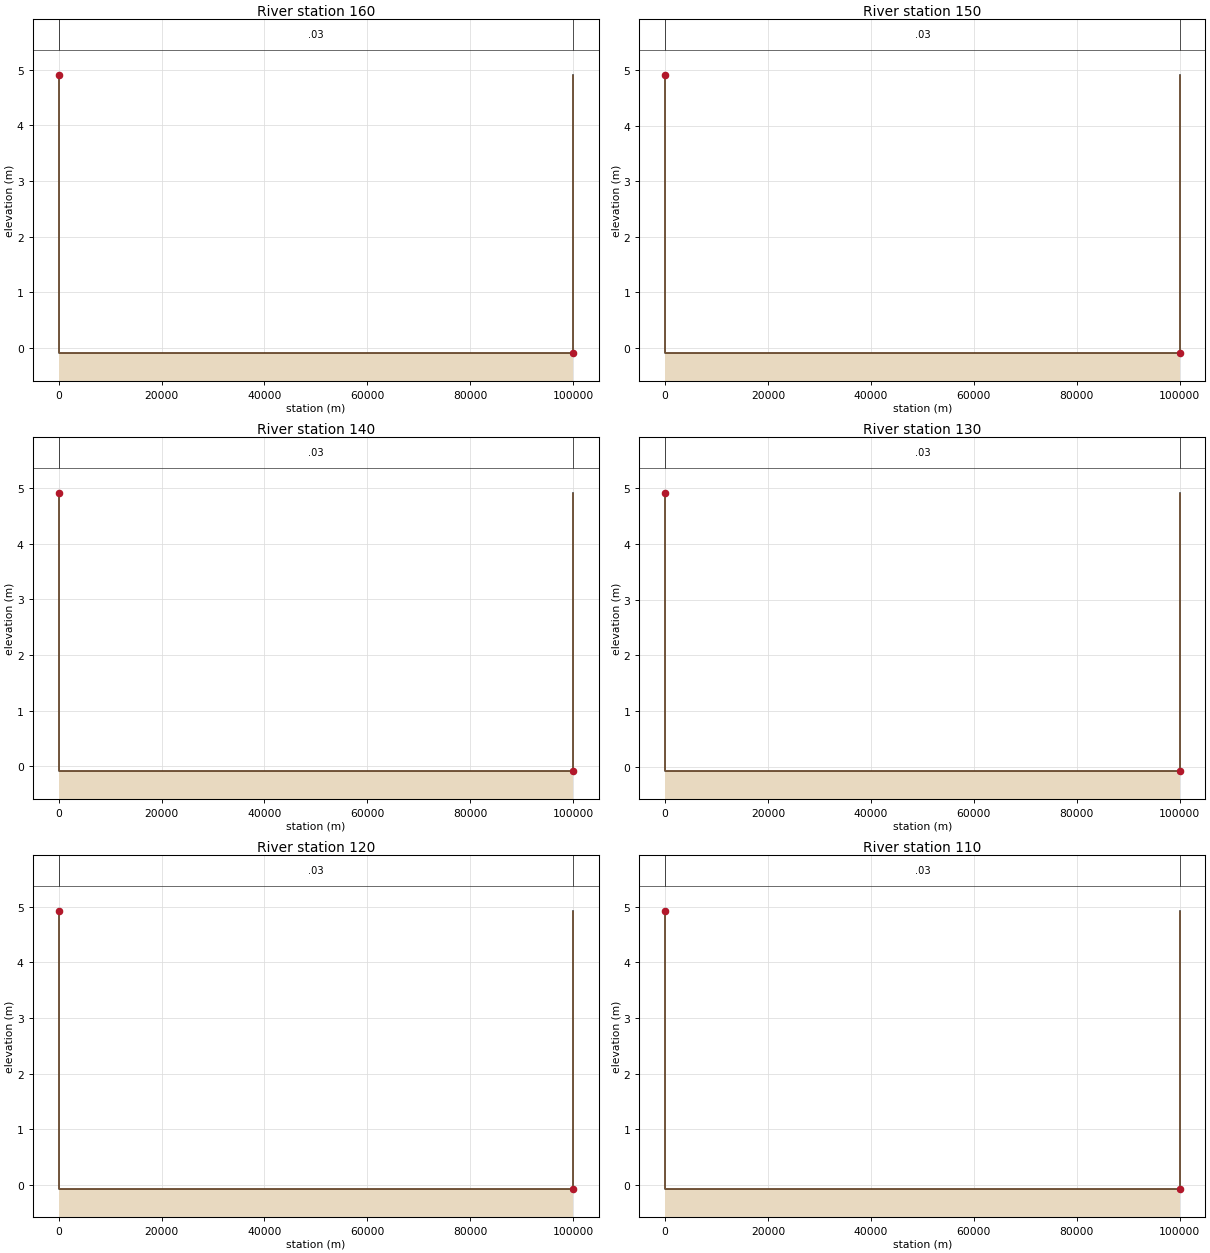
Type RM Length L Ch R = 1 ,160     ,10,10,10
#Sta/Elev= 4
 0.00000 4.90544 0.00000-0.09456  100000-0.09456  100000 4.90544
#Mann= 3 ,0,0
 0.00000 0.03000 0.00000 0.00000 0.03000 0.00000  100000 0.03000 0.00000
Bank Sta=0,100000
XS Rating Curve= 0 ,0
Exp/Cntr=0,0

Type RM Length L Ch R = 1 ,150     ,10,10,10
#Sta/Elev= 4
 0.00000 4.91072 0.00000-0.08928  100000-0.08928  100000 4.91072
#Mann= 3 ,0,0
 0.00000 0.03000 0.00000 0.00000 0.03000 0.00000  100000 0.03000 0.00000
Bank Sta=0,100000
XS Rating Curve= 0 ,0
Exp/Cntr=0,0

Type RM Length L Ch R = 1 ,140     ,10,10,10
#Sta/Elev= 4
 0.00000  4.9155 0.00000-0.08450  100000-0.08450  100000  4.9155
#Mann= 3 ,0,0
 0.00000 0.03000 0.00000 0.00000 0.03000 0.00000  100000 0.03000 0.00000
Bank Sta=0,100000
XS Rating Curve= 0 ,0
Exp/Cntr=0,0

Type RM Length L Ch R = 1 ,130     ,10,10,10
#Sta/Elev= 4
 0.00000 4.91979 0.00000-0.08021  100000-0.08021  100000 4.91979
#Mann= 3 ,0,0
 0.00000 0.03000 0.00000 0.00000 0.03000 0.00000  100000 0.03000 0.00000
Bank Sta=0,100000
XS Rating Curve= 0 ,0
Exp/Cntr=0,0

Type RM Length L Ch R = 1 ,120     ,10,10,10
#Sta/Elev= 4
 0.00000 4.92362 0.00000-0.07638  100000-0.07638  100000 4.92362
#Mann= 3 ,0,0
 0.00000 0.03000 0.00000 0.00000 0.03000 0.00000  100000 0.03000 0.00000
Bank Sta=0,100000
XS Rating Curve= 0 ,0
Exp/Cntr=0,0

Type RM Length L Ch R = 1 ,110     ,10,10,10
#Sta/Elev= 4
 0.00000 4.92701 0.00000-0.07299  100000-0.07299  100000 4.92701
#Mann= 3 ,0,0
 0.00000 0.03000 0.00000 0.00000 0.03000 0.00000  100000 0.03000 0.00000
Bank Sta=0,100000
XS Rating Curve= 0 ,0
Exp/Cntr=0,0

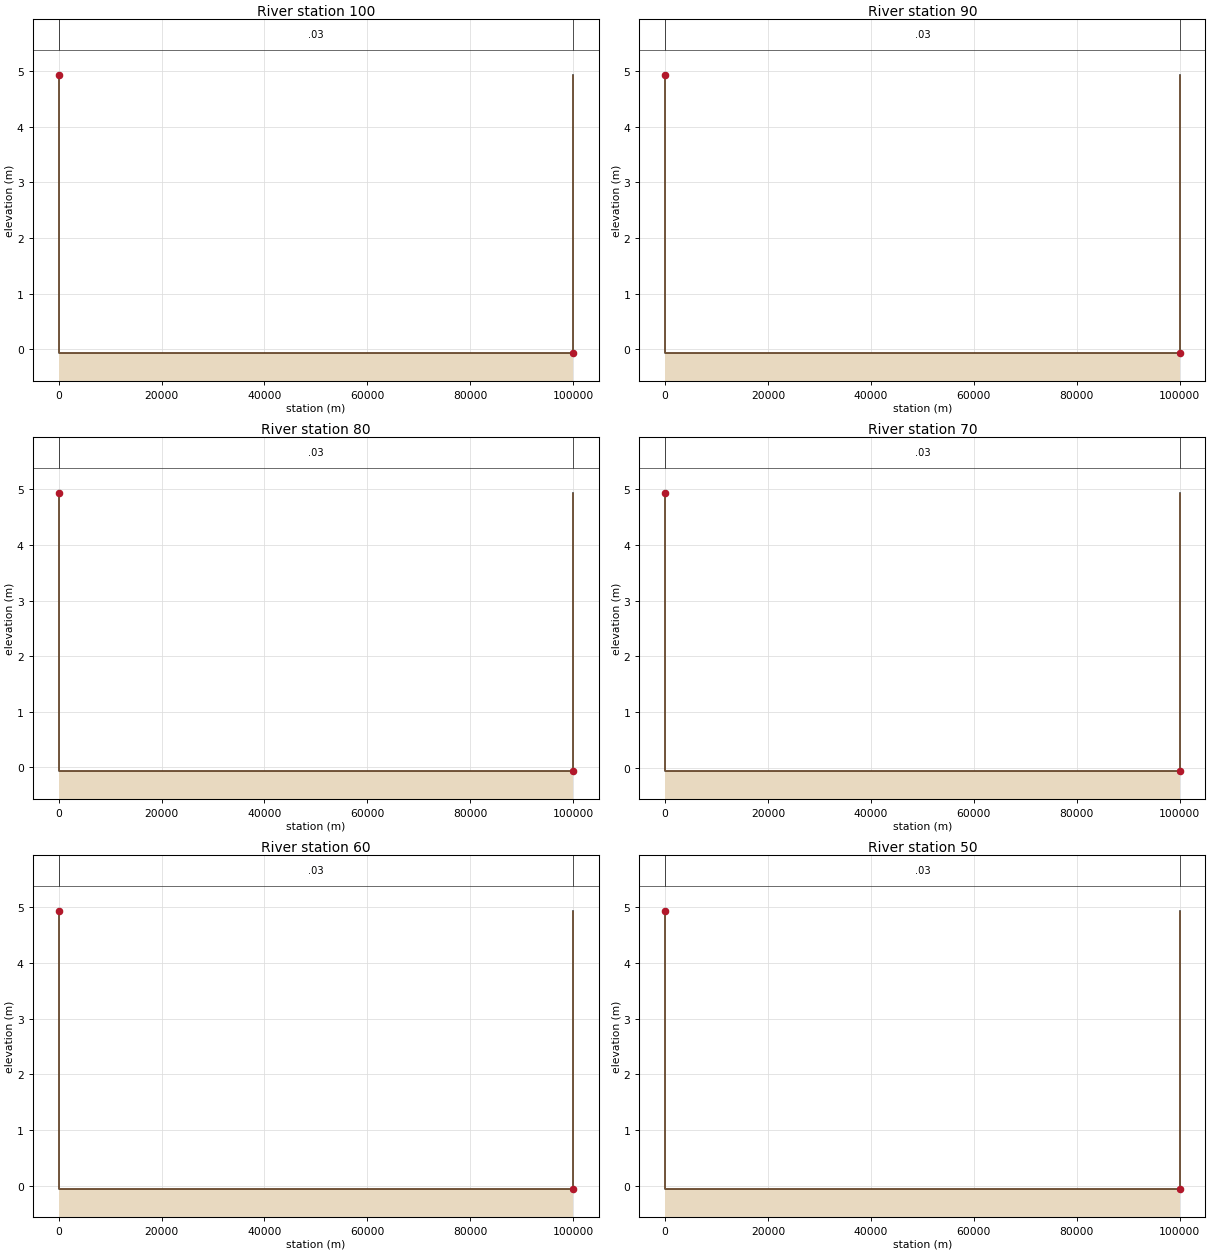
Type RM Length L Ch R = 1 ,100     ,10,10,10
#Sta/Elev= 4
 0.00000 4.92998 0.00000-0.07002  100000-0.07002  100000 4.92998
#Mann= 3 ,0,0
 0.00000 0.03000 0.00000 0.00000 0.03000 0.00000  100000 0.03000 0.00000
Bank Sta=0,100000
XS Rating Curve= 0 ,0
Exp/Cntr=0,0

Type RM Length L Ch R = 1 ,90      ,10,10,10
#Sta/Elev= 4
 0.00000 4.93257 0.00000-0.06743  100000-0.06743  100000 4.93257
#Mann= 3 ,0,0
 0.00000 0.03000 0.00000 0.00000 0.03000 0.00000  100000 0.03000 0.00000
Bank Sta=0,100000
XS Rating Curve= 0 ,0
Exp/Cntr=0,0

Type RM Length L Ch R = 1 ,80      ,10,10,10
#Sta/Elev= 4
 0.00000 4.93479 0.00000-0.06521  100000-0.06521  100000 4.93479
#Mann= 3 ,0,0
 0.00000 0.03000 0.00000 0.00000 0.03000 0.00000  100000 0.03000 0.00000
Bank Sta=0,100000
XS Rating Curve= 0 ,0
Exp/Cntr=0,0

Type RM Length L Ch R = 1 ,70      ,10,10,10
#Sta/Elev= 4
 0.00000 4.93668 0.00000-0.06332  100000-0.06332  100000 4.93668
#Mann= 3 ,0,0
 0.00000 0.03000 0.00000 0.00000 0.03000 0.00000  100000 0.03000 0.00000
Bank Sta=0,100000
XS Rating Curve= 0 ,0
Exp/Cntr=0,0

Type RM Length L Ch R = 1 ,60      ,10,10,10
#Sta/Elev= 4
 0.00000 4.93826 0.00000-0.06174  100000-0.06174  100000 4.93826
#Mann= 3 ,0,0
 0.00000 0.03000 0.00000 0.00000 0.03000 0.00000  100000 0.03000 0.00000
Bank Sta=0,100000
XS Rating Curve= 0 ,0
Exp/Cntr=0,0

Type RM Length L Ch R = 1 ,50      ,10,10,10
#Sta/Elev= 4
 0.00000 4.93955 0.00000-0.06045  100000-0.06045  100000 4.93955
#Mann= 3 ,0,0
 0.00000 0.03000 0.00000 0.00000 0.03000 0.00000  100000 0.03000 0.00000
Bank Sta=0,100000
XS Rating Curve= 0 ,0
Exp/Cntr=0,0

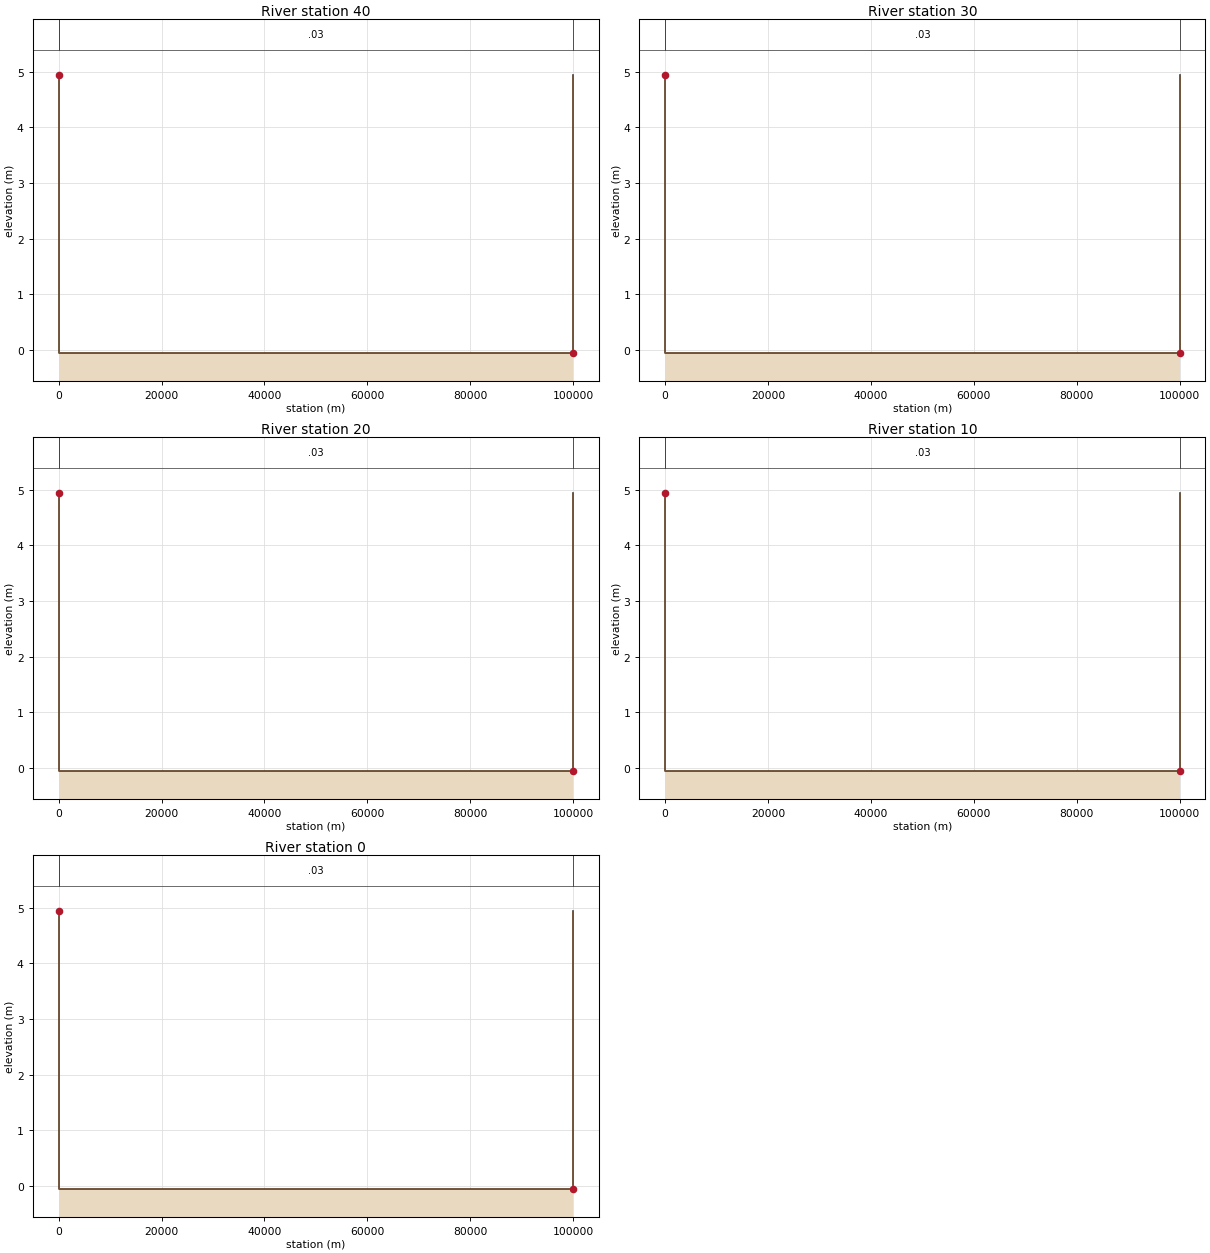
Type RM Length L Ch R = 1 ,40      ,10,10,10
#Sta/Elev= 4
 0.00000 4.94058 0.00000-0.05942  100000-0.05942  100000 4.94058
#Mann= 3 ,0,0
 0.00000 0.03000 0.00000 0.00000 0.03000 0.00000  100000 0.03000 0.00000
Bank Sta=0,100000
XS Rating Curve= 0 ,0
Exp/Cntr=0,0

Type RM Length L Ch R = 1 ,30      ,10,10,10
#Sta/Elev= 4
 0.00000 4.94137 0.00000-0.05863  100000-0.05863  100000 4.94137
#Mann= 3 ,0,0
 0.00000 0.03000 0.00000 0.00000 0.03000 0.00000  100000 0.03000 0.00000
Bank Sta=0,100000
XS Rating Curve= 0 ,0
Exp/Cntr=0,0

Type RM Length L Ch R = 1 ,20      ,10,10,10
#Sta/Elev= 4
 0.00000 4.94195 0.00000-0.05805  100000-0.05805  100000 4.94195
#Mann= 3 ,0,0
 0.00000 0.03000 0.00000 0.00000 0.03000 0.00000  100000 0.03000 0.00000
Bank Sta=0,100000
XS Rating Curve= 0 ,0
Exp/Cntr=0,0

Type RM Length L Ch R = 1 ,10      ,10,10,10
#Sta/Elev= 4
 0.00000 4.94233 0.00000-0.05767  100000-0.05767  100000 4.94233
#Mann= 3 ,0,0
 0.00000 0.03000 0.00000 0.00000 0.03000 0.00000  100000 0.03000 0.00000
Bank Sta=0,100000
XS Rating Curve= 0 ,0
Exp/Cntr=0,0

Type RM Length L Ch R = 1 ,0       ,0,0,0
#Sta/Elev= 4
 0.00000 4.94254 0.00000-0.05746  100000-0.05746  100000 4.94254
#Mann= 3 ,0,0
 0.00000 0.03000 0.00000 0.00000 0.03000 0.00000  100000 0.03000 0.00000
Bank Sta=0,100000
XS Rating Curve= 0 ,0
Exp/Cntr=0,0