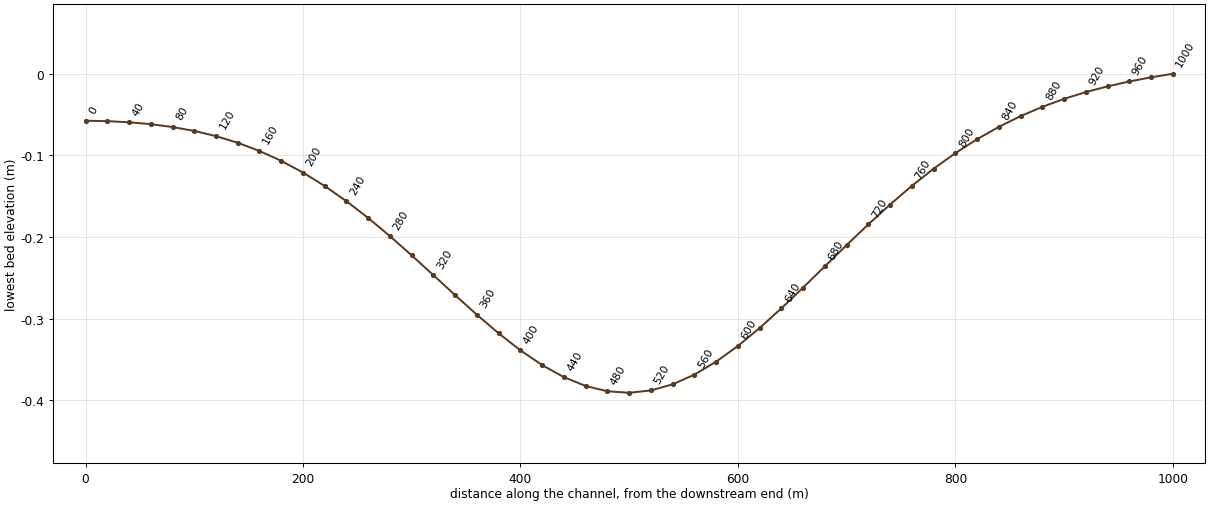
--- macdonald.prj (project) ---

Proj Title=A1F-001 MacDonald backwater dx=20 m
Current Plan=p01
Default Exp/Contr=0,0
SI Units
Geom File=g01
Flow File=f01
Plan File=p01
Y Axis Title=Elevation
X Axis Title(PF)=Main Channel Distance
X Axis Title(XS)=Station
BEGIN DESCRIPTION:
A1F-001 MacDonald backwater dx=20 m
END DESCRIPTION:

--- macdonald.p01 (plan) ---

Plan Title=A1F-001 MacDonald backwater dx=20 m
Program Version=6.60
Short Identifier=dx20
Geom File=g01
Flow File=f01
Subcritical Flow
K Sum by GR= 0
Std Step Tol= .00001
Critical Tol= .00001
Num of Std Step Trials= 40
Max Error Tol= .3
Flow Tol Ratio= .001
Log Output Level= 0
Friction Slope Method= 1

--- macdonald.f01 (steady flow) ---

Flow Title=A1F-001 MacDonald backwater dx=20 m
Program Version=6.60
Number of Profiles= 1
Profile Names=PF 1
River Rch & RM=Channel,Main            ,1000
   20000
Boundary for River Rch & Prof#=Channel,Main            , 1
Up Type= 0
Dn Type= 1
Dn Known WS=0.690867

--- macdonald.g01 (geometry) ---

Geom Title=A1F-001 MacDonald backwater dx=20 m
Program Version=6.60

River Reach=Channel         ,Main
Reach XY= 2
          0.5000          1.0000          0.5000          0.0000

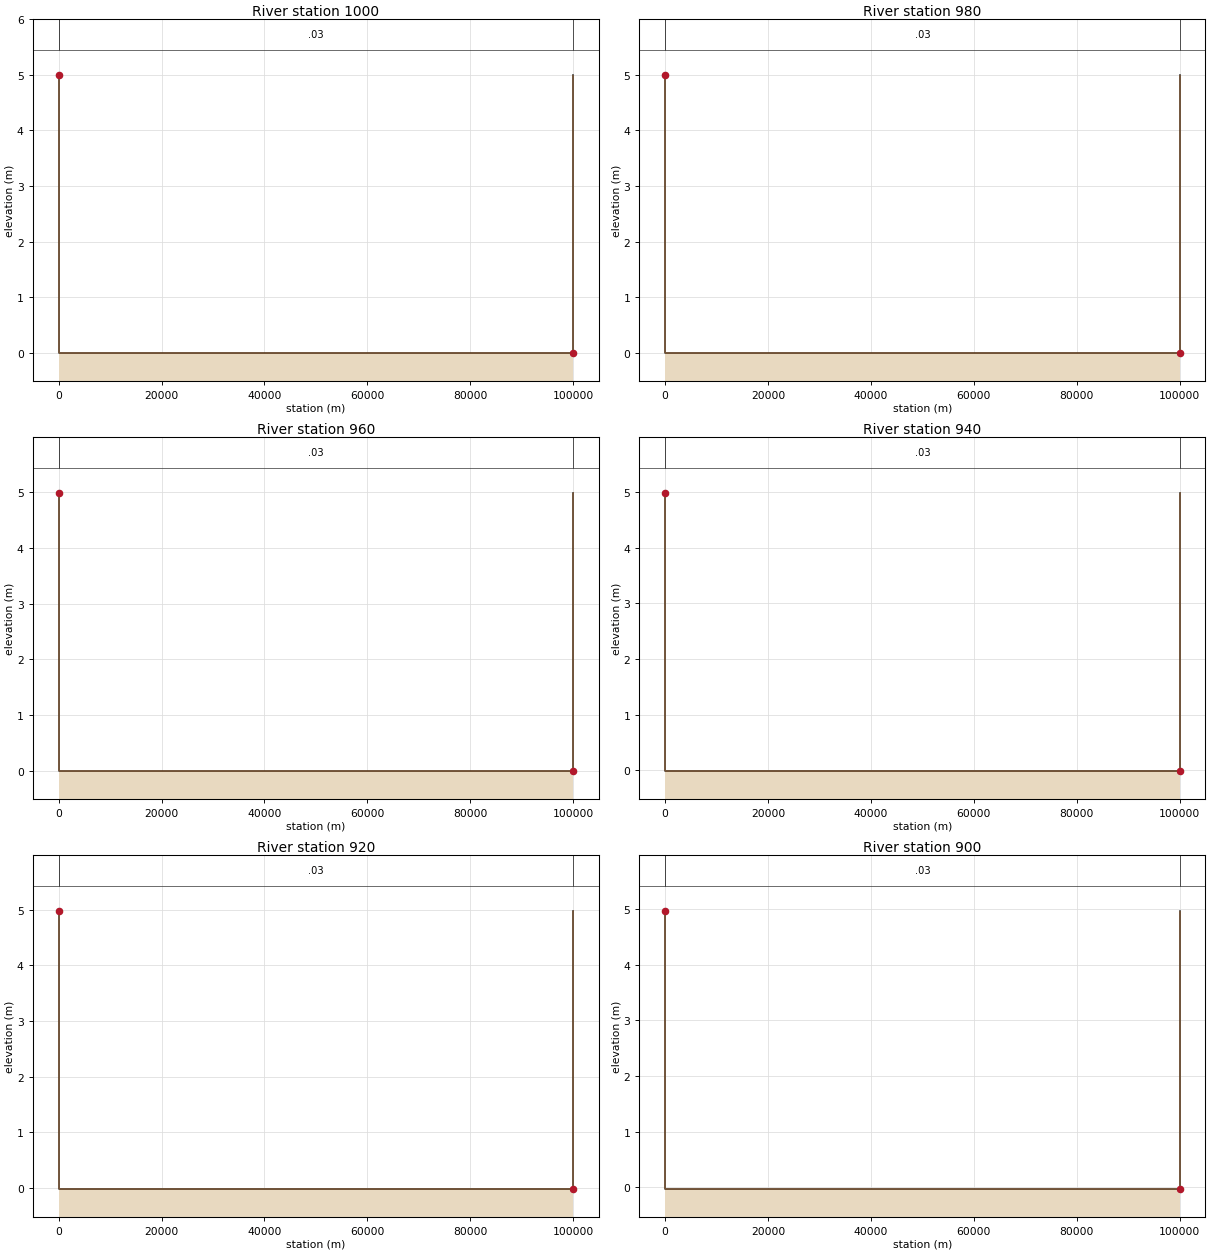
Type RM Length L Ch R = 1 ,1000    ,20,20,20
#Sta/Elev= 4
 0.00000       5 0.00000 0.00000  100000 0.00000  100000       5
#Mann= 3 ,0,0
 0.00000 0.03000 0.00000 0.00000 0.03000 0.00000  100000 0.03000 0.00000
Bank Sta=0,100000
XS Rating Curve= 0 ,0
Exp/Cntr=0,0

Type RM Length L Ch R = 1 ,980     ,20,20,20
#Sta/Elev= 4
 0.00000 4.99564 0.00000-0.00436  100000-0.00436  100000 4.99564
#Mann= 3 ,0,0
 0.00000 0.03000 0.00000 0.00000 0.03000 0.00000  100000 0.03000 0.00000
Bank Sta=0,100000
XS Rating Curve= 0 ,0
Exp/Cntr=0,0

Type RM Length L Ch R = 1 ,960     ,20,20,20
#Sta/Elev= 4
 0.00000 4.99055 0.00000-0.00945  100000-0.00945  100000 4.99055
#Mann= 3 ,0,0
 0.00000 0.03000 0.00000 0.00000 0.03000 0.00000  100000 0.03000 0.00000
Bank Sta=0,100000
XS Rating Curve= 0 ,0
Exp/Cntr=0,0

Type RM Length L Ch R = 1 ,940     ,20,20,20
#Sta/Elev= 4
 0.00000 4.98457 0.00000-0.01543  100000-0.01543  100000 4.98457
#Mann= 3 ,0,0
 0.00000 0.03000 0.00000 0.00000 0.03000 0.00000  100000 0.03000 0.00000
Bank Sta=0,100000
XS Rating Curve= 0 ,0
Exp/Cntr=0,0

Type RM Length L Ch R = 1 ,920     ,20,20,20
#Sta/Elev= 4
 0.00000 4.97753 0.00000-0.02247  100000-0.02247  100000 4.97753
#Mann= 3 ,0,0
 0.00000 0.03000 0.00000 0.00000 0.03000 0.00000  100000 0.03000 0.00000
Bank Sta=0,100000
XS Rating Curve= 0 ,0
Exp/Cntr=0,0

Type RM Length L Ch R = 1 ,900     ,20,20,20
#Sta/Elev= 4
 0.00000 4.96923 0.00000-0.03077  100000-0.03077  100000 4.96923
#Mann= 3 ,0,0
 0.00000 0.03000 0.00000 0.00000 0.03000 0.00000  100000 0.03000 0.00000
Bank Sta=0,100000
XS Rating Curve= 0 ,0
Exp/Cntr=0,0

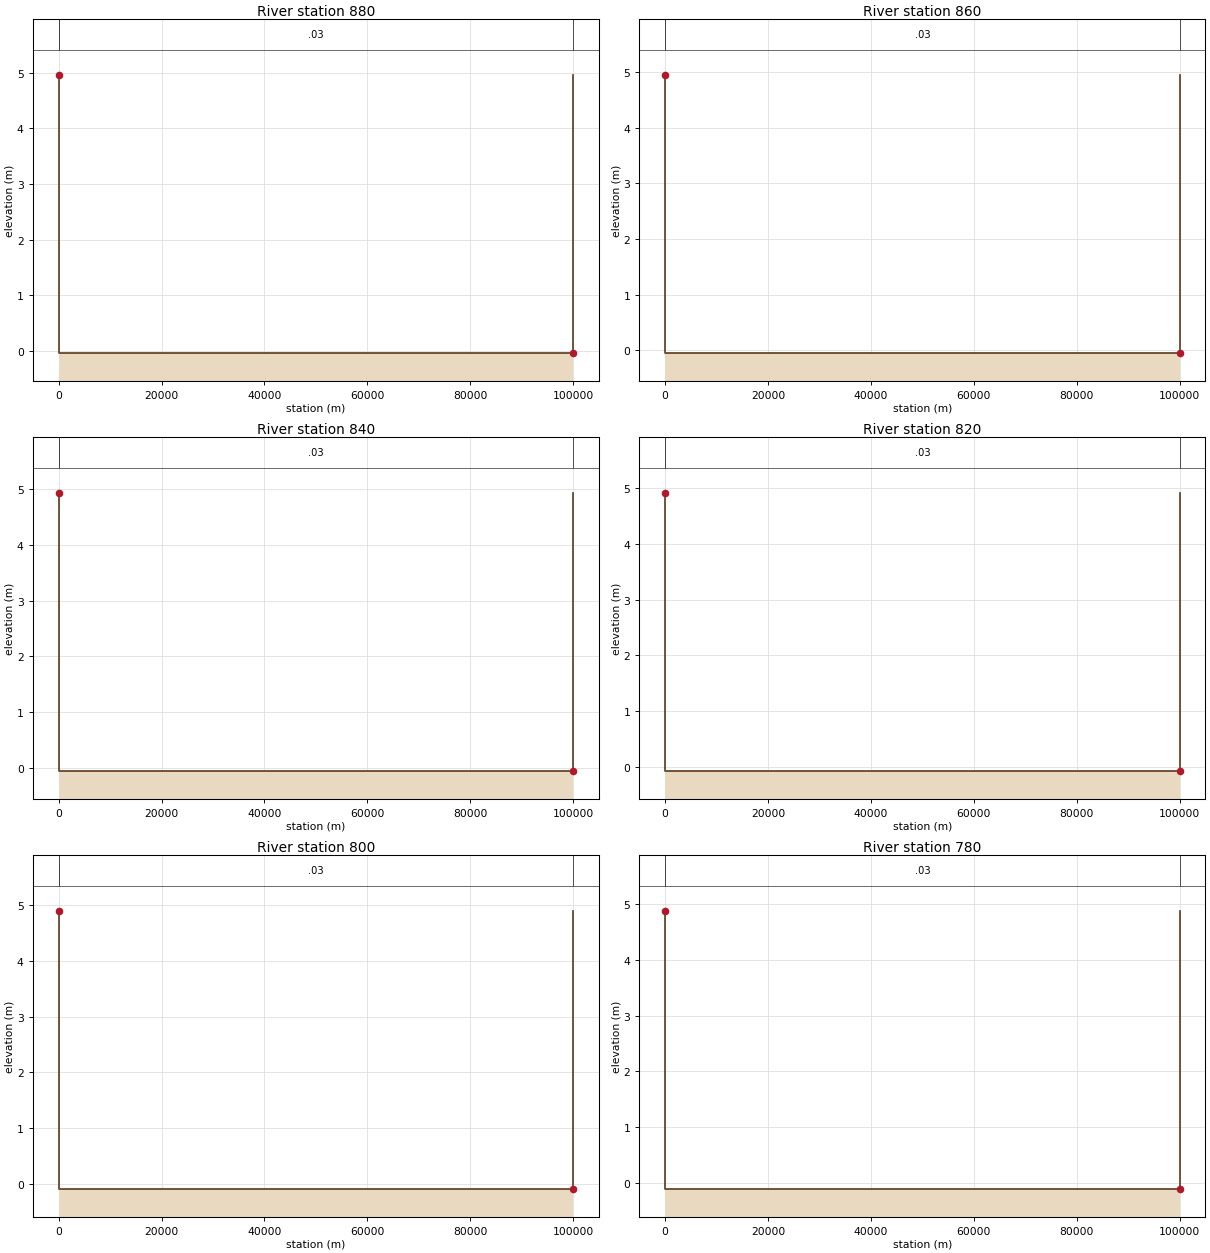
Type RM Length L Ch R = 1 ,880     ,20,20,20
#Sta/Elev= 4
 0.00000 4.95948 0.00000-0.04052  100000-0.04052  100000 4.95948
#Mann= 3 ,0,0
 0.00000 0.03000 0.00000 0.00000 0.03000 0.00000  100000 0.03000 0.00000
Bank Sta=0,100000
XS Rating Curve= 0 ,0
Exp/Cntr=0,0

Type RM Length L Ch R = 1 ,860     ,20,20,20
#Sta/Elev= 4
 0.00000 4.94811 0.00000-0.05189  100000-0.05189  100000 4.94811
#Mann= 3 ,0,0
 0.00000 0.03000 0.00000 0.00000 0.03000 0.00000  100000 0.03000 0.00000
Bank Sta=0,100000
XS Rating Curve= 0 ,0
Exp/Cntr=0,0

Type RM Length L Ch R = 1 ,840     ,20,20,20
#Sta/Elev= 4
 0.00000 4.93495 0.00000-0.06505  100000-0.06505  100000 4.93495
#Mann= 3 ,0,0
 0.00000 0.03000 0.00000 0.00000 0.03000 0.00000  100000 0.03000 0.00000
Bank Sta=0,100000
XS Rating Curve= 0 ,0
Exp/Cntr=0,0

Type RM Length L Ch R = 1 ,820     ,20,20,20
#Sta/Elev= 4
 0.00000 4.91986 0.00000-0.08014  100000-0.08014  100000 4.91986
#Mann= 3 ,0,0
 0.00000 0.03000 0.00000 0.00000 0.03000 0.00000  100000 0.03000 0.00000
Bank Sta=0,100000
XS Rating Curve= 0 ,0
Exp/Cntr=0,0

Type RM Length L Ch R = 1 ,800     ,20,20,20
#Sta/Elev= 4
 0.00000 4.90278 0.00000-0.09722  100000-0.09722  100000 4.90278
#Mann= 3 ,0,0
 0.00000 0.03000 0.00000 0.00000 0.03000 0.00000  100000 0.03000 0.00000
Bank Sta=0,100000
XS Rating Curve= 0 ,0
Exp/Cntr=0,0

Type RM Length L Ch R = 1 ,780     ,20,20,20
#Sta/Elev= 4
 0.00000 4.88369 0.00000-0.11631  100000-0.11631  100000 4.88369
#Mann= 3 ,0,0
 0.00000 0.03000 0.00000 0.00000 0.03000 0.00000  100000 0.03000 0.00000
Bank Sta=0,100000
XS Rating Curve= 0 ,0
Exp/Cntr=0,0

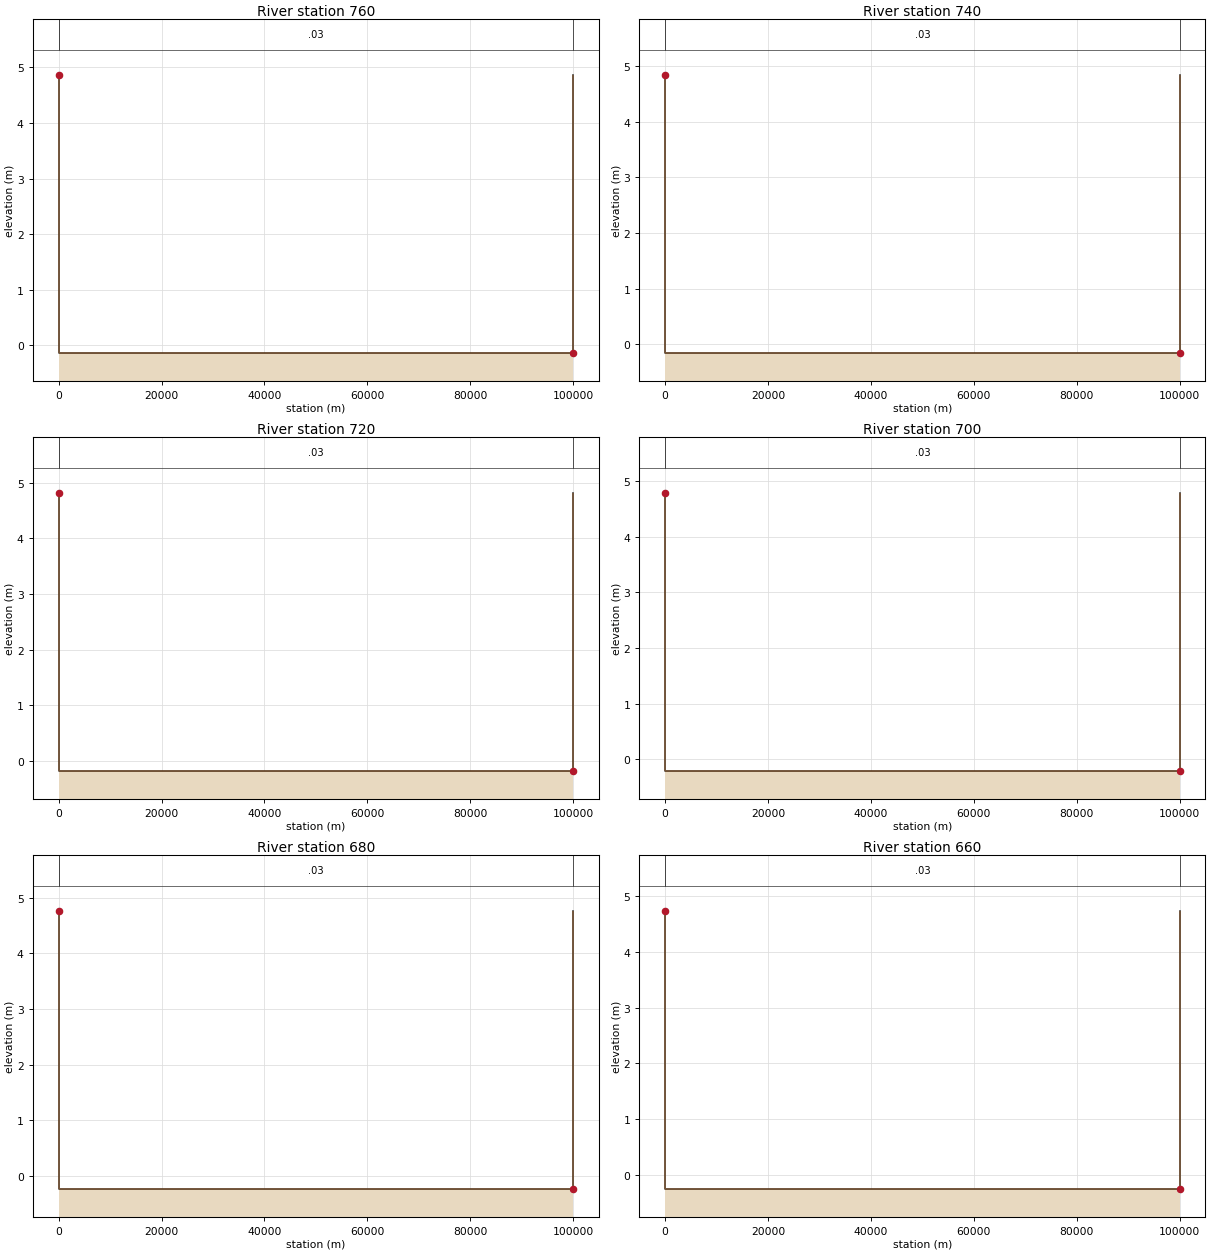
Type RM Length L Ch R = 1 ,760     ,20,20,20
#Sta/Elev= 4
 0.00000 4.86267 0.00000-0.13733  100000-0.13733  100000 4.86267
#Mann= 3 ,0,0
 0.00000 0.03000 0.00000 0.00000 0.03000 0.00000  100000 0.03000 0.00000
Bank Sta=0,100000
XS Rating Curve= 0 ,0
Exp/Cntr=0,0

Type RM Length L Ch R = 1 ,740     ,20,20,20
#Sta/Elev= 4
 0.00000 4.83988 0.00000-0.16012  100000-0.16012  100000 4.83988
#Mann= 3 ,0,0
 0.00000 0.03000 0.00000 0.00000 0.03000 0.00000  100000 0.03000 0.00000
Bank Sta=0,100000
XS Rating Curve= 0 ,0
Exp/Cntr=0,0

Type RM Length L Ch R = 1 ,720     ,20,20,20
#Sta/Elev= 4
 0.00000 4.81559 0.00000-0.18441  100000-0.18441  100000 4.81559
#Mann= 3 ,0,0
 0.00000 0.03000 0.00000 0.00000 0.03000 0.00000  100000 0.03000 0.00000
Bank Sta=0,100000
XS Rating Curve= 0 ,0
Exp/Cntr=0,0

Type RM Length L Ch R = 1 ,700     ,20,20,20
#Sta/Elev= 4
 0.00000  4.7902 0.00000-0.20980  100000-0.20980  100000  4.7902
#Mann= 3 ,0,0
 0.00000 0.03000 0.00000 0.00000 0.03000 0.00000  100000 0.03000 0.00000
Bank Sta=0,100000
XS Rating Curve= 0 ,0
Exp/Cntr=0,0

Type RM Length L Ch R = 1 ,680     ,20,20,20
#Sta/Elev= 4
 0.00000 4.76418 0.00000-0.23582  100000-0.23582  100000 4.76418
#Mann= 3 ,0,0
 0.00000 0.03000 0.00000 0.00000 0.03000 0.00000  100000 0.03000 0.00000
Bank Sta=0,100000
XS Rating Curve= 0 ,0
Exp/Cntr=0,0

Type RM Length L Ch R = 1 ,660     ,20,20,20
#Sta/Elev= 4
 0.00000 4.73814 0.00000-0.26186  100000-0.26186  100000 4.73814
#Mann= 3 ,0,0
 0.00000 0.03000 0.00000 0.00000 0.03000 0.00000  100000 0.03000 0.00000
Bank Sta=0,100000
XS Rating Curve= 0 ,0
Exp/Cntr=0,0

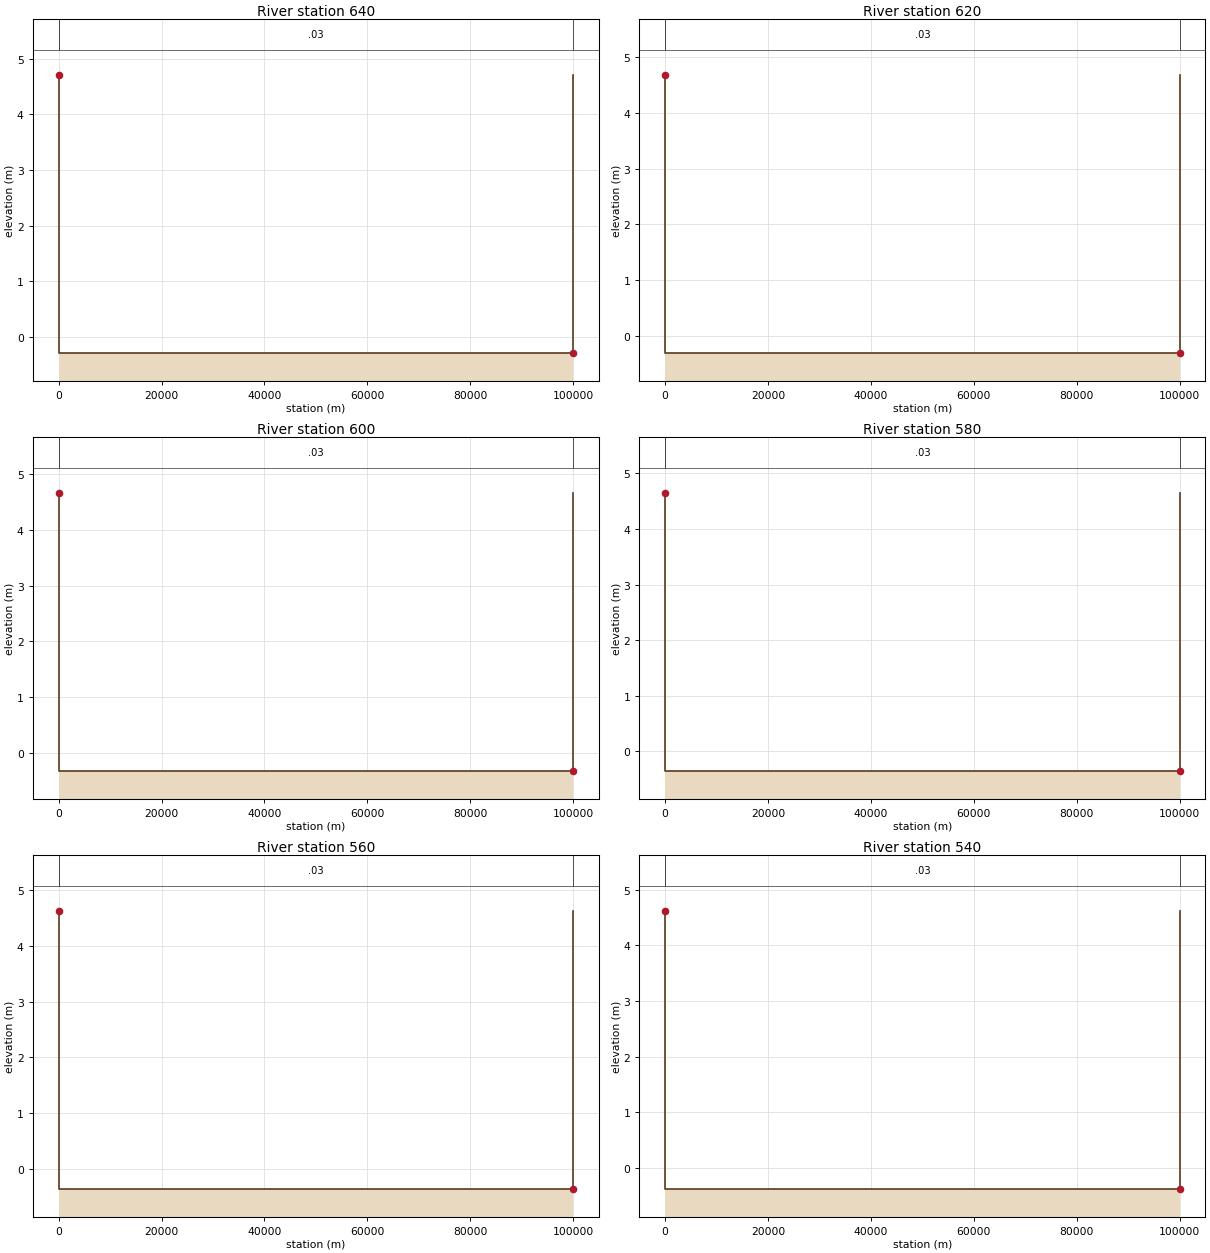
Type RM Length L Ch R = 1 ,640     ,20,20,20
#Sta/Elev= 4
 0.00000 4.71271 0.00000-0.28729  100000-0.28729  100000 4.71271
#Mann= 3 ,0,0
 0.00000 0.03000 0.00000 0.00000 0.03000 0.00000  100000 0.03000 0.00000
Bank Sta=0,100000
XS Rating Curve= 0 ,0
Exp/Cntr=0,0

Type RM Length L Ch R = 1 ,620     ,20,20,20
#Sta/Elev= 4
 0.00000 4.68863 0.00000-0.31137  100000-0.31137  100000 4.68863
#Mann= 3 ,0,0
 0.00000 0.03000 0.00000 0.00000 0.03000 0.00000  100000 0.03000 0.00000
Bank Sta=0,100000
XS Rating Curve= 0 ,0
Exp/Cntr=0,0

Type RM Length L Ch R = 1 ,600     ,20,20,20
#Sta/Elev= 4
 0.00000 4.66661 0.00000-0.33339  100000-0.33339  100000 4.66661
#Mann= 3 ,0,0
 0.00000 0.03000 0.00000 0.00000 0.03000 0.00000  100000 0.03000 0.00000
Bank Sta=0,100000
XS Rating Curve= 0 ,0
Exp/Cntr=0,0

Type RM Length L Ch R = 1 ,580     ,20,20,20
#Sta/Elev= 4
 0.00000 4.64736 0.00000-0.35264  100000-0.35264  100000 4.64736
#Mann= 3 ,0,0
 0.00000 0.03000 0.00000 0.00000 0.03000 0.00000  100000 0.03000 0.00000
Bank Sta=0,100000
XS Rating Curve= 0 ,0
Exp/Cntr=0,0

Type RM Length L Ch R = 1 ,560     ,20,20,20
#Sta/Elev= 4
 0.00000 4.63153 0.00000-0.36847  100000-0.36847  100000 4.63153
#Mann= 3 ,0,0
 0.00000 0.03000 0.00000 0.00000 0.03000 0.00000  100000 0.03000 0.00000
Bank Sta=0,100000
XS Rating Curve= 0 ,0
Exp/Cntr=0,0

Type RM Length L Ch R = 1 ,540     ,20,20,20
#Sta/Elev= 4
 0.00000 4.61965 0.00000-0.38035  100000-0.38035  100000 4.61965
#Mann= 3 ,0,0
 0.00000 0.03000 0.00000 0.00000 0.03000 0.00000  100000 0.03000 0.00000
Bank Sta=0,100000
XS Rating Curve= 0 ,0
Exp/Cntr=0,0

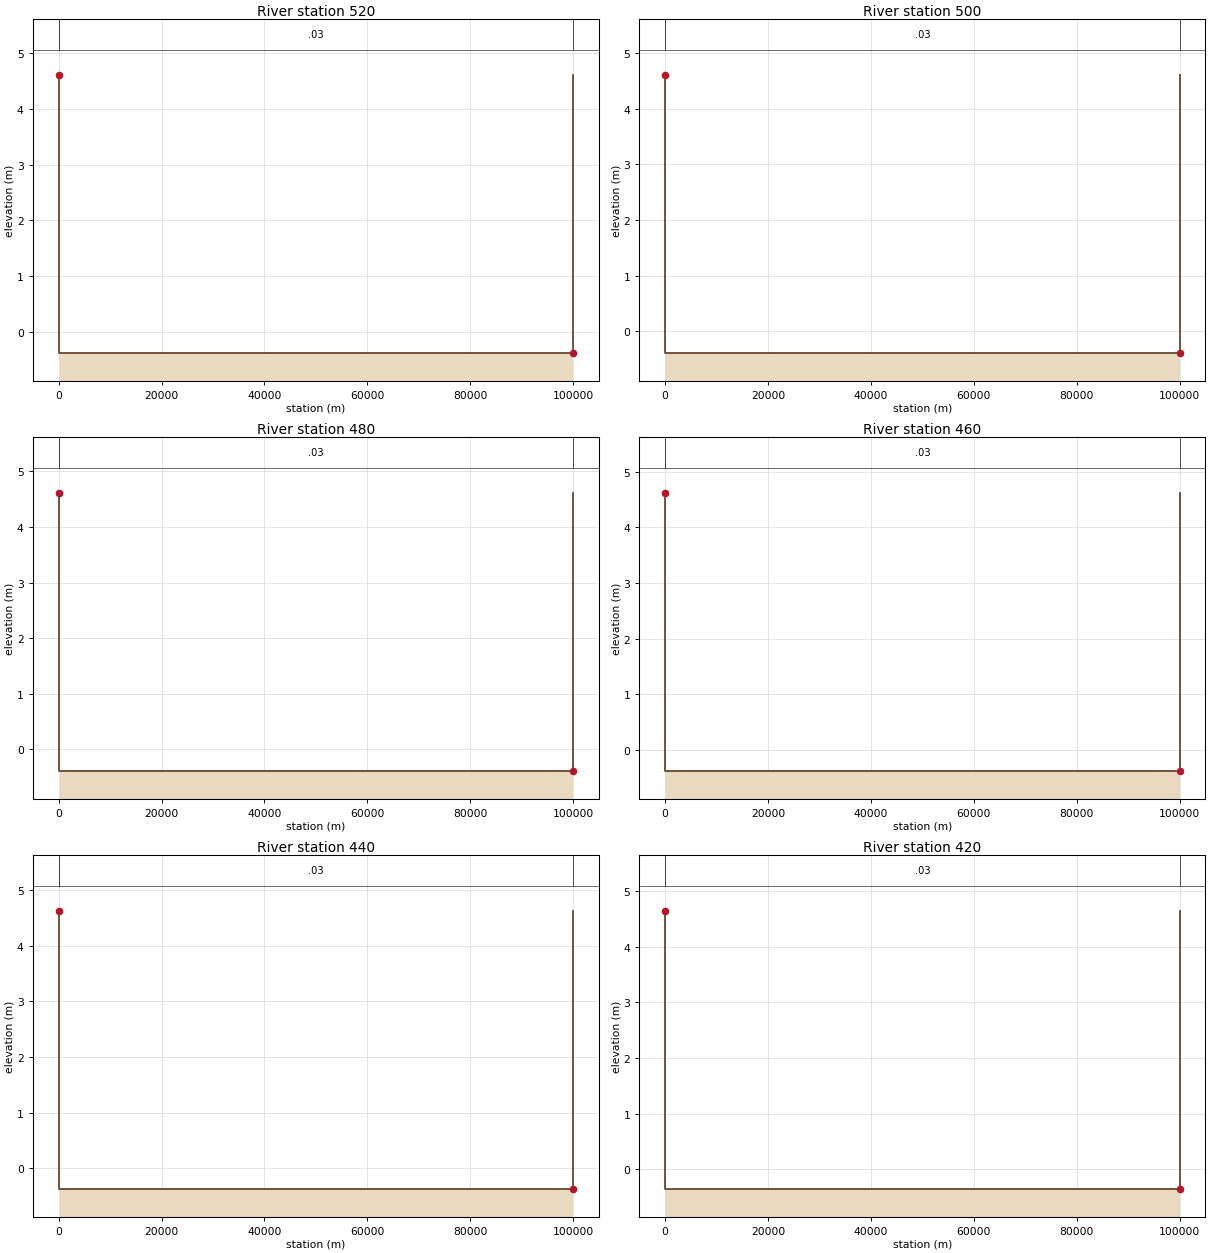
Type RM Length L Ch R = 1 ,520     ,20,20,20
#Sta/Elev= 4
 0.00000 4.61215 0.00000-0.38785  100000-0.38785  100000 4.61215
#Mann= 3 ,0,0
 0.00000 0.03000 0.00000 0.00000 0.03000 0.00000  100000 0.03000 0.00000
Bank Sta=0,100000
XS Rating Curve= 0 ,0
Exp/Cntr=0,0

Type RM Length L Ch R = 1 ,500     ,20,20,20
#Sta/Elev= 4
 0.00000 4.60929 0.00000-0.39071  100000-0.39071  100000 4.60929
#Mann= 3 ,0,0
 0.00000 0.03000 0.00000 0.00000 0.03000 0.00000  100000 0.03000 0.00000
Bank Sta=0,100000
XS Rating Curve= 0 ,0
Exp/Cntr=0,0

Type RM Length L Ch R = 1 ,480     ,20,20,20
#Sta/Elev= 4
 0.00000 4.61114 0.00000-0.38886  100000-0.38886  100000 4.61114
#Mann= 3 ,0,0
 0.00000 0.03000 0.00000 0.00000 0.03000 0.00000  100000 0.03000 0.00000
Bank Sta=0,100000
XS Rating Curve= 0 ,0
Exp/Cntr=0,0

Type RM Length L Ch R = 1 ,460     ,20,20,20
#Sta/Elev= 4
 0.00000 4.61761 0.00000-0.38239  100000-0.38239  100000 4.61761
#Mann= 3 ,0,0
 0.00000 0.03000 0.00000 0.00000 0.03000 0.00000  100000 0.03000 0.00000
Bank Sta=0,100000
XS Rating Curve= 0 ,0
Exp/Cntr=0,0

Type RM Length L Ch R = 1 ,440     ,20,20,20
#Sta/Elev= 4
 0.00000 4.62843 0.00000-0.37157  100000-0.37157  100000 4.62843
#Mann= 3 ,0,0
 0.00000 0.03000 0.00000 0.00000 0.03000 0.00000  100000 0.03000 0.00000
Bank Sta=0,100000
XS Rating Curve= 0 ,0
Exp/Cntr=0,0

Type RM Length L Ch R = 1 ,420     ,20,20,20
#Sta/Elev= 4
 0.00000 4.64317 0.00000-0.35683  100000-0.35683  100000 4.64317
#Mann= 3 ,0,0
 0.00000 0.03000 0.00000 0.00000 0.03000 0.00000  100000 0.03000 0.00000
Bank Sta=0,100000
XS Rating Curve= 0 ,0
Exp/Cntr=0,0

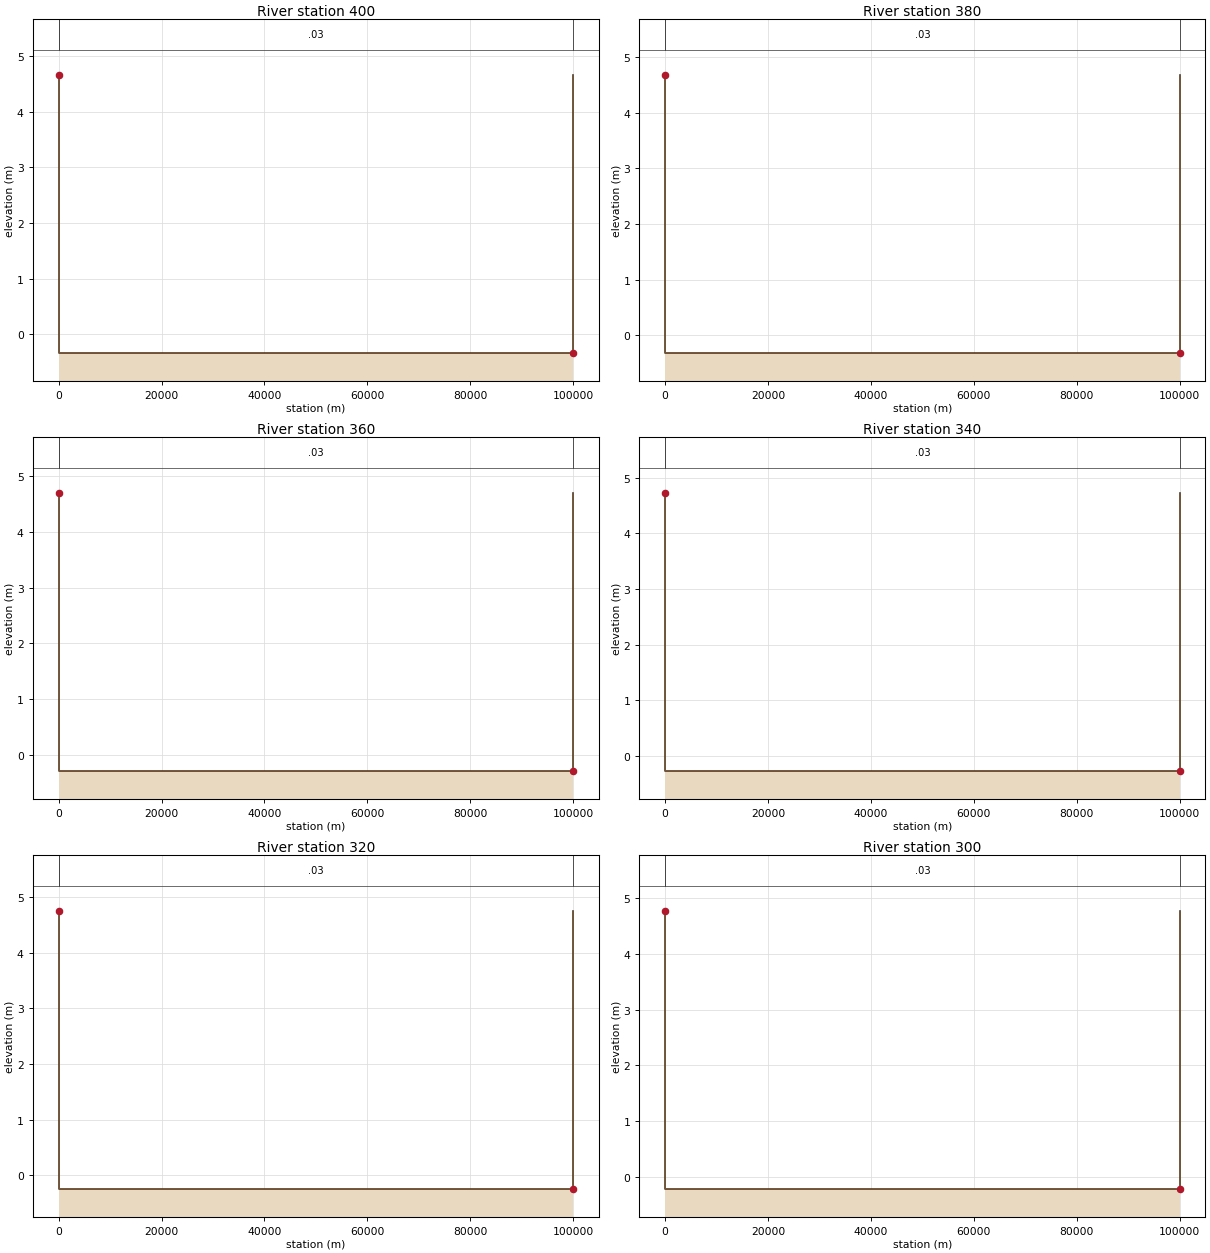
Type RM Length L Ch R = 1 ,400     ,20,20,20
#Sta/Elev= 4
 0.00000 4.66126 0.00000-0.33874  100000-0.33874  100000 4.66126
#Mann= 3 ,0,0
 0.00000 0.03000 0.00000 0.00000 0.03000 0.00000  100000 0.03000 0.00000
Bank Sta=0,100000
XS Rating Curve= 0 ,0
Exp/Cntr=0,0

Type RM Length L Ch R = 1 ,380     ,20,20,20
#Sta/Elev= 4
 0.00000 4.68204 0.00000-0.31796  100000-0.31796  100000 4.68204
#Mann= 3 ,0,0
 0.00000 0.03000 0.00000 0.00000 0.03000 0.00000  100000 0.03000 0.00000
Bank Sta=0,100000
XS Rating Curve= 0 ,0
Exp/Cntr=0,0

Type RM Length L Ch R = 1 ,360     ,20,20,20
#Sta/Elev= 4
 0.00000 4.70479 0.00000-0.29521  100000-0.29521  100000 4.70479
#Mann= 3 ,0,0
 0.00000 0.03000 0.00000 0.00000 0.03000 0.00000  100000 0.03000 0.00000
Bank Sta=0,100000
XS Rating Curve= 0 ,0
Exp/Cntr=0,0

Type RM Length L Ch R = 1 ,340     ,20,20,20
#Sta/Elev= 4
 0.00000 4.72878 0.00000-0.27122  100000-0.27122  100000 4.72878
#Mann= 3 ,0,0
 0.00000 0.03000 0.00000 0.00000 0.03000 0.00000  100000 0.03000 0.00000
Bank Sta=0,100000
XS Rating Curve= 0 ,0
Exp/Cntr=0,0

Type RM Length L Ch R = 1 ,320     ,20,20,20
#Sta/Elev= 4
 0.00000 4.75326 0.00000-0.24674  100000-0.24674  100000 4.75326
#Mann= 3 ,0,0
 0.00000 0.03000 0.00000 0.00000 0.03000 0.00000  100000 0.03000 0.00000
Bank Sta=0,100000
XS Rating Curve= 0 ,0
Exp/Cntr=0,0

Type RM Length L Ch R = 1 ,300     ,20,20,20
#Sta/Elev= 4
 0.00000 4.77756 0.00000-0.22244  100000-0.22244  100000 4.77756
#Mann= 3 ,0,0
 0.00000 0.03000 0.00000 0.00000 0.03000 0.00000  100000 0.03000 0.00000
Bank Sta=0,100000
XS Rating Curve= 0 ,0
Exp/Cntr=0,0

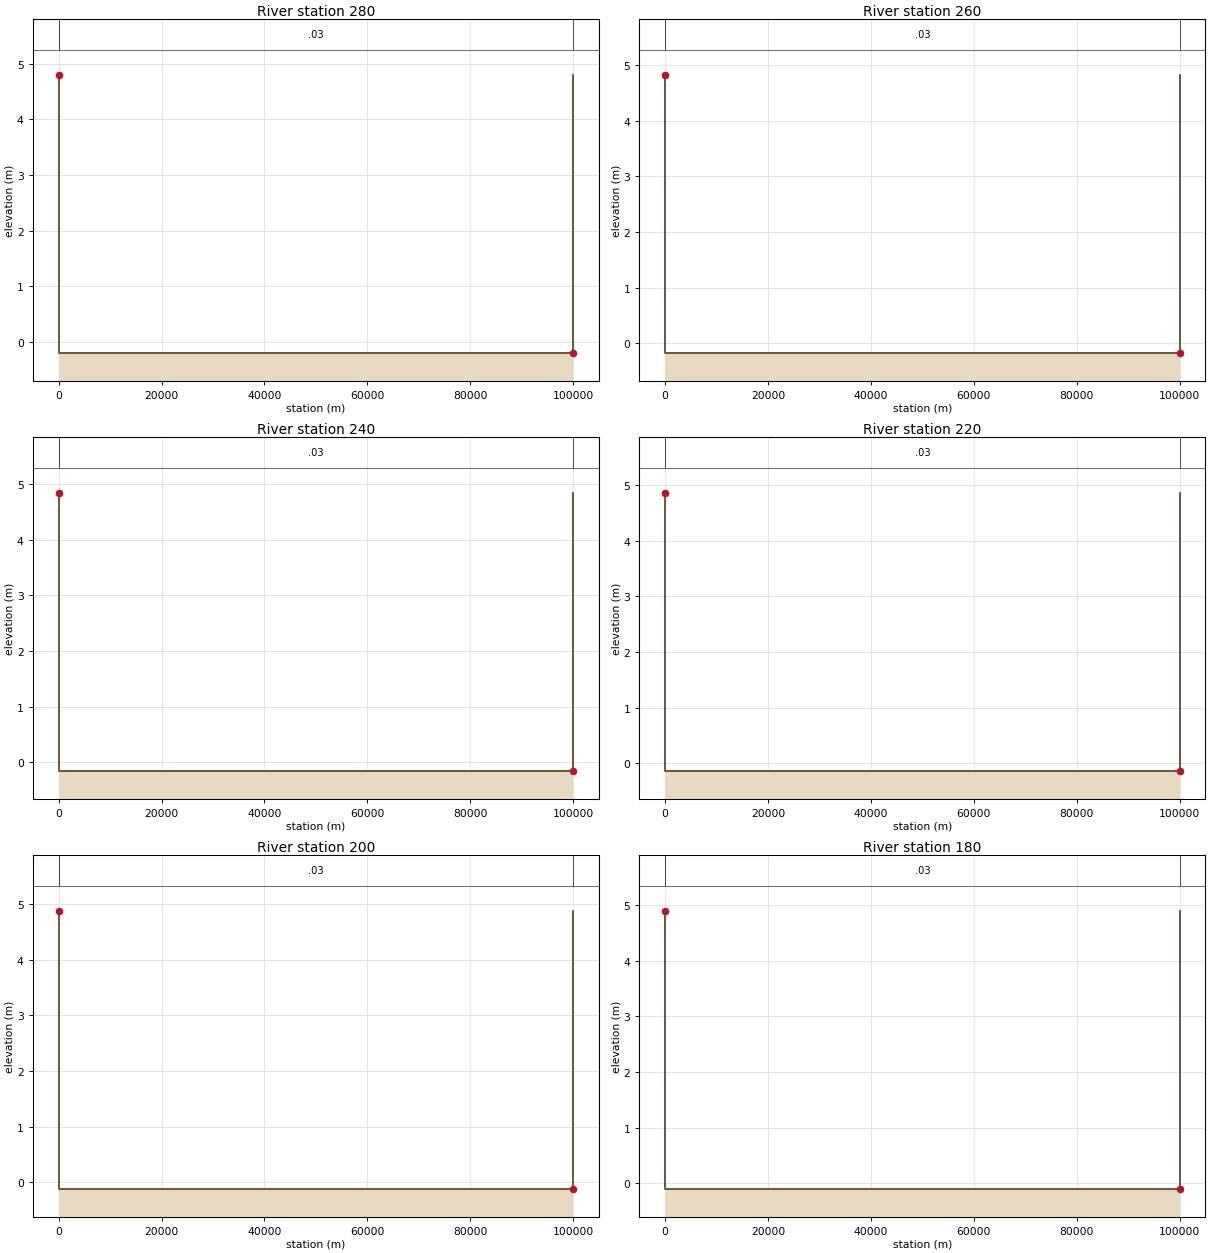
Type RM Length L Ch R = 1 ,280     ,20,20,20
#Sta/Elev= 4
 0.00000 4.80108 0.00000-0.19892  100000-0.19892  100000 4.80108
#Mann= 3 ,0,0
 0.00000 0.03000 0.00000 0.00000 0.03000 0.00000  100000 0.03000 0.00000
Bank Sta=0,100000
XS Rating Curve= 0 ,0
Exp/Cntr=0,0

Type RM Length L Ch R = 1 ,260     ,20,20,20
#Sta/Elev= 4
 0.00000 4.82333 0.00000-0.17667  100000-0.17667  100000 4.82333
#Mann= 3 ,0,0
 0.00000 0.03000 0.00000 0.00000 0.03000 0.00000  100000 0.03000 0.00000
Bank Sta=0,100000
XS Rating Curve= 0 ,0
Exp/Cntr=0,0

Type RM Length L Ch R = 1 ,240     ,20,20,20
#Sta/Elev= 4
 0.00000  4.8439 0.00000-0.15610  100000-0.15610  100000  4.8439
#Mann= 3 ,0,0
 0.00000 0.03000 0.00000 0.00000 0.03000 0.00000  100000 0.03000 0.00000
Bank Sta=0,100000
XS Rating Curve= 0 ,0
Exp/Cntr=0,0

Type RM Length L Ch R = 1 ,220     ,20,20,20
#Sta/Elev= 4
 0.00000 4.86251 0.00000-0.13749  100000-0.13749  100000 4.86251
#Mann= 3 ,0,0
 0.00000 0.03000 0.00000 0.00000 0.03000 0.00000  100000 0.03000 0.00000
Bank Sta=0,100000
XS Rating Curve= 0 ,0
Exp/Cntr=0,0

Type RM Length L Ch R = 1 ,200     ,20,20,20
#Sta/Elev= 4
 0.00000 4.87901 0.00000-0.12099  100000-0.12099  100000 4.87901
#Mann= 3 ,0,0
 0.00000 0.03000 0.00000 0.00000 0.03000 0.00000  100000 0.03000 0.00000
Bank Sta=0,100000
XS Rating Curve= 0 ,0
Exp/Cntr=0,0

Type RM Length L Ch R = 1 ,180     ,20,20,20
#Sta/Elev= 4
 0.00000 4.89331 0.00000-0.10669  100000-0.10669  100000 4.89331
#Mann= 3 ,0,0
 0.00000 0.03000 0.00000 0.00000 0.03000 0.00000  100000 0.03000 0.00000
Bank Sta=0,100000
XS Rating Curve= 0 ,0
Exp/Cntr=0,0

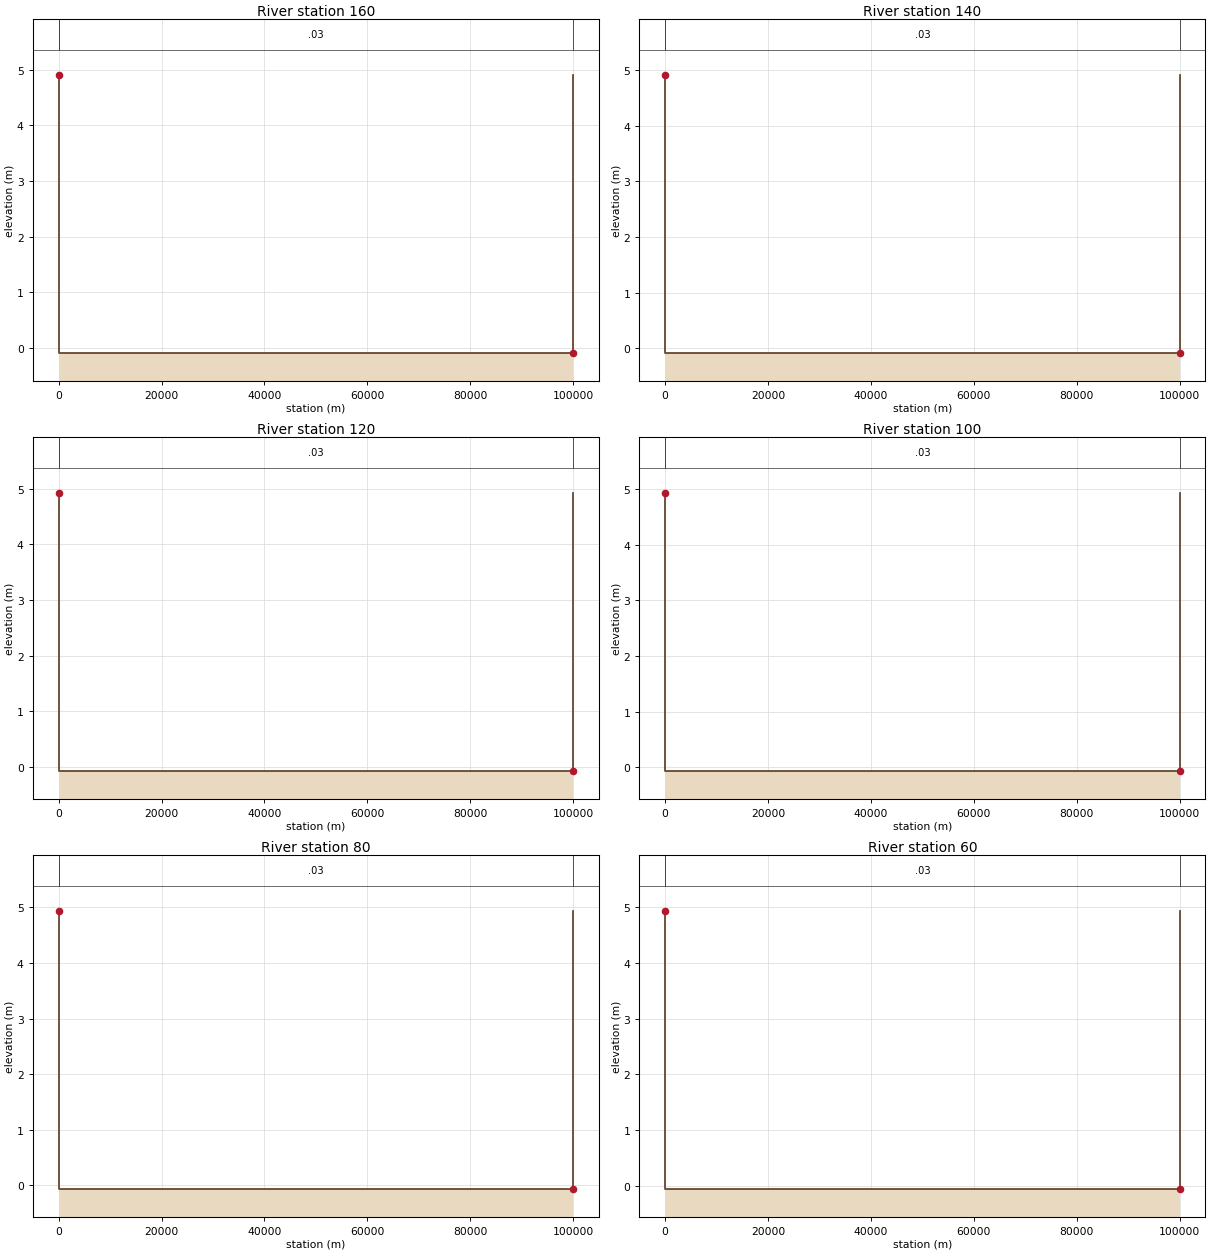
Type RM Length L Ch R = 1 ,160     ,20,20,20
#Sta/Elev= 4
 0.00000 4.90544 0.00000-0.09456  100000-0.09456  100000 4.90544
#Mann= 3 ,0,0
 0.00000 0.03000 0.00000 0.00000 0.03000 0.00000  100000 0.03000 0.00000
Bank Sta=0,100000
XS Rating Curve= 0 ,0
Exp/Cntr=0,0

Type RM Length L Ch R = 1 ,140     ,20,20,20
#Sta/Elev= 4
 0.00000  4.9155 0.00000-0.08450  100000-0.08450  100000  4.9155
#Mann= 3 ,0,0
 0.00000 0.03000 0.00000 0.00000 0.03000 0.00000  100000 0.03000 0.00000
Bank Sta=0,100000
XS Rating Curve= 0 ,0
Exp/Cntr=0,0

Type RM Length L Ch R = 1 ,120     ,20,20,20
#Sta/Elev= 4
 0.00000 4.92362 0.00000-0.07638  100000-0.07638  100000 4.92362
#Mann= 3 ,0,0
 0.00000 0.03000 0.00000 0.00000 0.03000 0.00000  100000 0.03000 0.00000
Bank Sta=0,100000
XS Rating Curve= 0 ,0
Exp/Cntr=0,0

Type RM Length L Ch R = 1 ,100     ,20,20,20
#Sta/Elev= 4
 0.00000 4.92998 0.00000-0.07002  100000-0.07002  100000 4.92998
#Mann= 3 ,0,0
 0.00000 0.03000 0.00000 0.00000 0.03000 0.00000  100000 0.03000 0.00000
Bank Sta=0,100000
XS Rating Curve= 0 ,0
Exp/Cntr=0,0

Type RM Length L Ch R = 1 ,80      ,20,20,20
#Sta/Elev= 4
 0.00000 4.93479 0.00000-0.06521  100000-0.06521  100000 4.93479
#Mann= 3 ,0,0
 0.00000 0.03000 0.00000 0.00000 0.03000 0.00000  100000 0.03000 0.00000
Bank Sta=0,100000
XS Rating Curve= 0 ,0
Exp/Cntr=0,0

Type RM Length L Ch R = 1 ,60      ,20,20,20
#Sta/Elev= 4
 0.00000 4.93826 0.00000-0.06174  100000-0.06174  100000 4.93826
#Mann= 3 ,0,0
 0.00000 0.03000 0.00000 0.00000 0.03000 0.00000  100000 0.03000 0.00000
Bank Sta=0,100000
XS Rating Curve= 0 ,0
Exp/Cntr=0,0

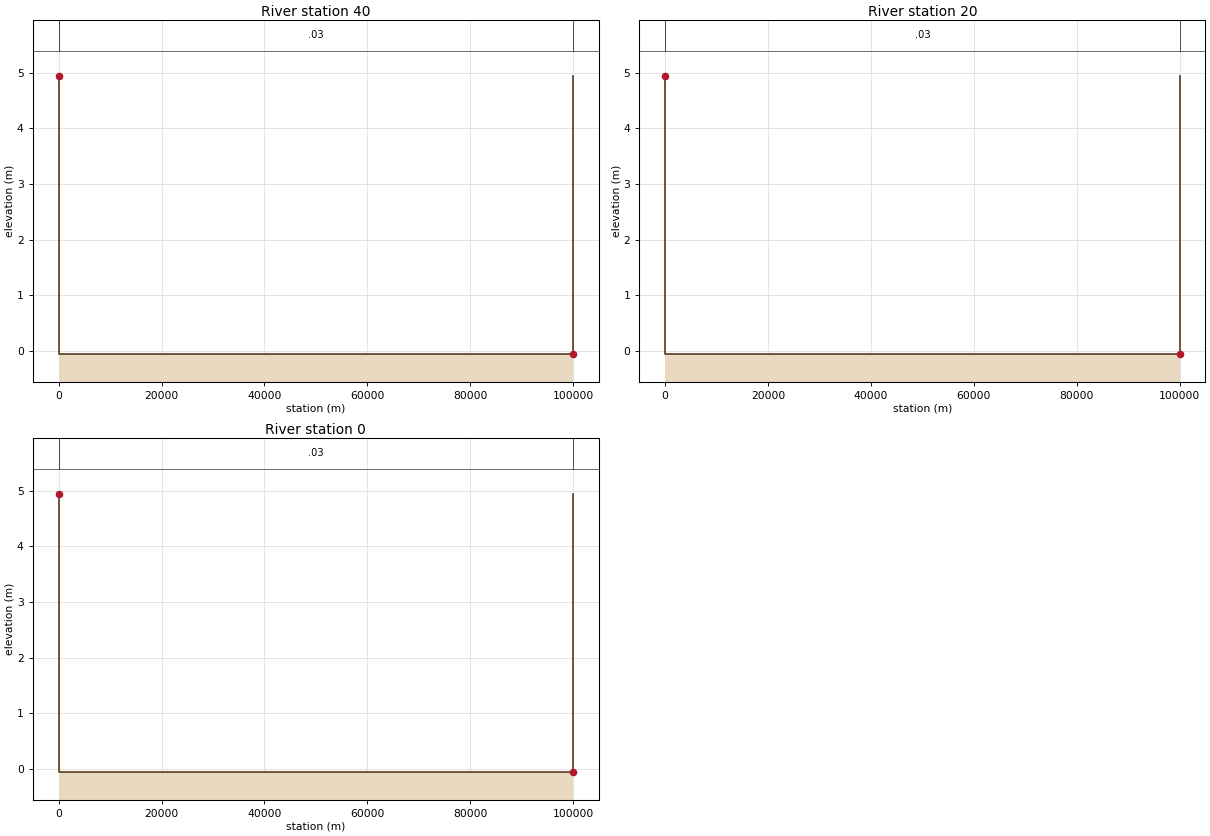
Type RM Length L Ch R = 1 ,40      ,20,20,20
#Sta/Elev= 4
 0.00000 4.94058 0.00000-0.05942  100000-0.05942  100000 4.94058
#Mann= 3 ,0,0
 0.00000 0.03000 0.00000 0.00000 0.03000 0.00000  100000 0.03000 0.00000
Bank Sta=0,100000
XS Rating Curve= 0 ,0
Exp/Cntr=0,0

Type RM Length L Ch R = 1 ,20      ,20,20,20
#Sta/Elev= 4
 0.00000 4.94195 0.00000-0.05805  100000-0.05805  100000 4.94195
#Mann= 3 ,0,0
 0.00000 0.03000 0.00000 0.00000 0.03000 0.00000  100000 0.03000 0.00000
Bank Sta=0,100000
XS Rating Curve= 0 ,0
Exp/Cntr=0,0

Type RM Length L Ch R = 1 ,0       ,0,0,0
#Sta/Elev= 4
 0.00000 4.94254 0.00000-0.05746  100000-0.05746  100000 4.94254
#Mann= 3 ,0,0
 0.00000 0.03000 0.00000 0.00000 0.03000 0.00000  100000 0.03000 0.00000
Bank Sta=0,100000
XS Rating Curve= 0 ,0
Exp/Cntr=0,0