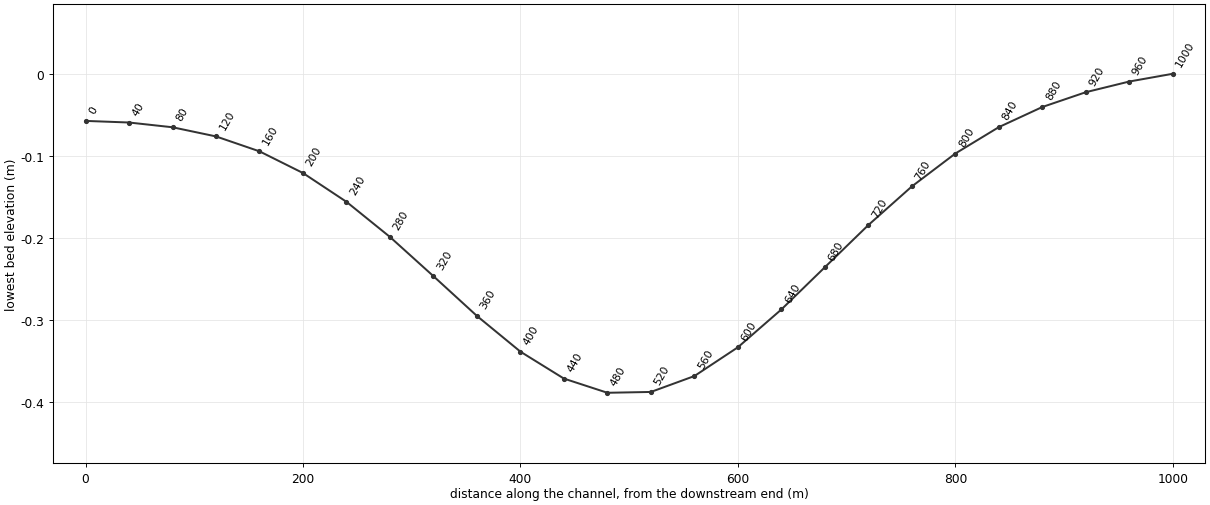
--- macdonald.prj (project) ---

Proj Title=A1F-001 MacDonald backwater dx=40 m
Current Plan=p01
Default Exp/Contr=0,0
SI Units
Geom File=g01
Flow File=f01
Plan File=p01
Y Axis Title=Elevation
X Axis Title(PF)=Main Channel Distance
X Axis Title(XS)=Station
BEGIN DESCRIPTION:
A1F-001 MacDonald backwater dx=40 m
END DESCRIPTION:

--- macdonald.p01 (plan) ---

Plan Title=A1F-001 MacDonald backwater dx=40 m
Program Version=6.60
Short Identifier=dx40
Geom File=g01
Flow File=f01
Subcritical Flow
K Sum by GR= 0
Std Step Tol= .00001
Critical Tol= .00001
Num of Std Step Trials= 40
Max Error Tol= .3
Flow Tol Ratio= .001
Log Output Level= 0
Friction Slope Method= 1

--- macdonald.f01 (steady flow) ---

Flow Title=A1F-001 MacDonald backwater dx=40 m
Program Version=6.60
Number of Profiles= 1
Profile Names=PF 1
River Rch & RM=Channel,Main            ,1000
   20000
Boundary for River Rch & Prof#=Channel,Main            , 1
Up Type= 0
Dn Type= 1
Dn Known WS=0.690867

--- macdonald.g01 (geometry) ---

Geom Title=A1F-001 MacDonald backwater dx=40 m
Program Version=6.60

River Reach=Channel         ,Main
Reach XY= 2
          0.5000          1.0000          0.5000          0.0000

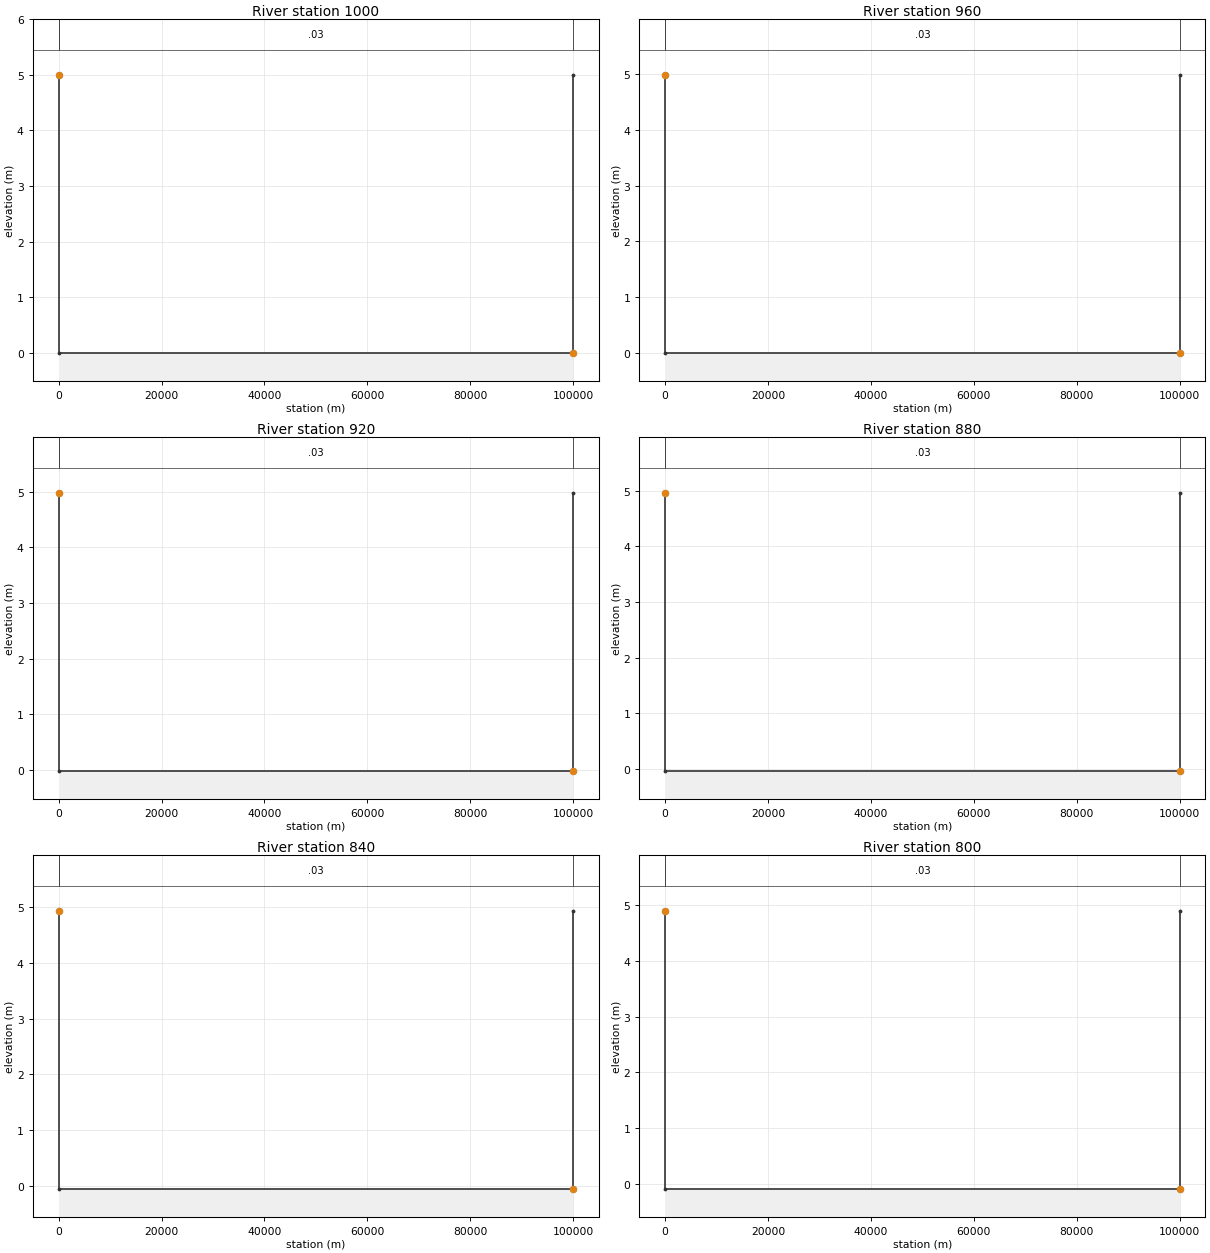
Type RM Length L Ch R = 1 ,1000    ,40,40,40
#Sta/Elev= 4
 0.00000       5 0.00000 0.00000  100000 0.00000  100000       5
#Mann= 3 ,0,0
 0.00000 0.03000 0.00000 0.00000 0.03000 0.00000  100000 0.03000 0.00000
Bank Sta=0,100000
XS Rating Curve= 0 ,0
Exp/Cntr=0,0

Type RM Length L Ch R = 1 ,960     ,40,40,40
#Sta/Elev= 4
 0.00000 4.99055 0.00000-0.00945  100000-0.00945  100000 4.99055
#Mann= 3 ,0,0
 0.00000 0.03000 0.00000 0.00000 0.03000 0.00000  100000 0.03000 0.00000
Bank Sta=0,100000
XS Rating Curve= 0 ,0
Exp/Cntr=0,0

Type RM Length L Ch R = 1 ,920     ,40,40,40
#Sta/Elev= 4
 0.00000 4.97753 0.00000-0.02247  100000-0.02247  100000 4.97753
#Mann= 3 ,0,0
 0.00000 0.03000 0.00000 0.00000 0.03000 0.00000  100000 0.03000 0.00000
Bank Sta=0,100000
XS Rating Curve= 0 ,0
Exp/Cntr=0,0

Type RM Length L Ch R = 1 ,880     ,40,40,40
#Sta/Elev= 4
 0.00000 4.95948 0.00000-0.04052  100000-0.04052  100000 4.95948
#Mann= 3 ,0,0
 0.00000 0.03000 0.00000 0.00000 0.03000 0.00000  100000 0.03000 0.00000
Bank Sta=0,100000
XS Rating Curve= 0 ,0
Exp/Cntr=0,0

Type RM Length L Ch R = 1 ,840     ,40,40,40
#Sta/Elev= 4
 0.00000 4.93495 0.00000-0.06505  100000-0.06505  100000 4.93495
#Mann= 3 ,0,0
 0.00000 0.03000 0.00000 0.00000 0.03000 0.00000  100000 0.03000 0.00000
Bank Sta=0,100000
XS Rating Curve= 0 ,0
Exp/Cntr=0,0

Type RM Length L Ch R = 1 ,800     ,40,40,40
#Sta/Elev= 4
 0.00000 4.90278 0.00000-0.09722  100000-0.09722  100000 4.90278
#Mann= 3 ,0,0
 0.00000 0.03000 0.00000 0.00000 0.03000 0.00000  100000 0.03000 0.00000
Bank Sta=0,100000
XS Rating Curve= 0 ,0
Exp/Cntr=0,0

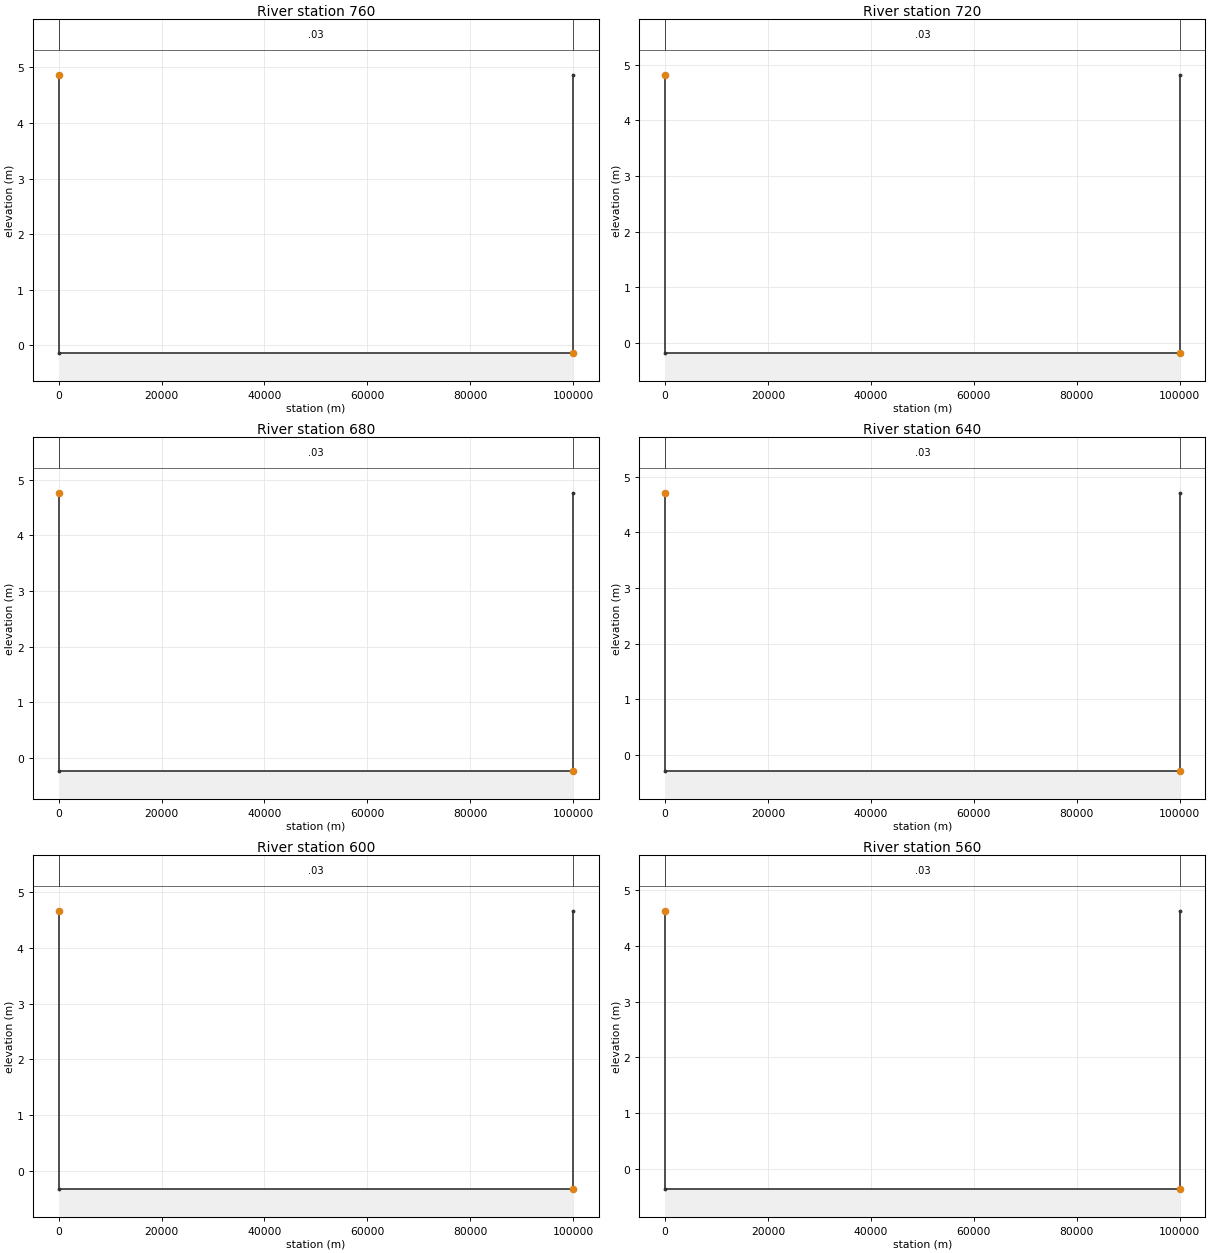
Type RM Length L Ch R = 1 ,760     ,40,40,40
#Sta/Elev= 4
 0.00000 4.86267 0.00000-0.13733  100000-0.13733  100000 4.86267
#Mann= 3 ,0,0
 0.00000 0.03000 0.00000 0.00000 0.03000 0.00000  100000 0.03000 0.00000
Bank Sta=0,100000
XS Rating Curve= 0 ,0
Exp/Cntr=0,0

Type RM Length L Ch R = 1 ,720     ,40,40,40
#Sta/Elev= 4
 0.00000 4.81559 0.00000-0.18441  100000-0.18441  100000 4.81559
#Mann= 3 ,0,0
 0.00000 0.03000 0.00000 0.00000 0.03000 0.00000  100000 0.03000 0.00000
Bank Sta=0,100000
XS Rating Curve= 0 ,0
Exp/Cntr=0,0

Type RM Length L Ch R = 1 ,680     ,40,40,40
#Sta/Elev= 4
 0.00000 4.76418 0.00000-0.23582  100000-0.23582  100000 4.76418
#Mann= 3 ,0,0
 0.00000 0.03000 0.00000 0.00000 0.03000 0.00000  100000 0.03000 0.00000
Bank Sta=0,100000
XS Rating Curve= 0 ,0
Exp/Cntr=0,0

Type RM Length L Ch R = 1 ,640     ,40,40,40
#Sta/Elev= 4
 0.00000 4.71271 0.00000-0.28729  100000-0.28729  100000 4.71271
#Mann= 3 ,0,0
 0.00000 0.03000 0.00000 0.00000 0.03000 0.00000  100000 0.03000 0.00000
Bank Sta=0,100000
XS Rating Curve= 0 ,0
Exp/Cntr=0,0

Type RM Length L Ch R = 1 ,600     ,40,40,40
#Sta/Elev= 4
 0.00000 4.66661 0.00000-0.33339  100000-0.33339  100000 4.66661
#Mann= 3 ,0,0
 0.00000 0.03000 0.00000 0.00000 0.03000 0.00000  100000 0.03000 0.00000
Bank Sta=0,100000
XS Rating Curve= 0 ,0
Exp/Cntr=0,0

Type RM Length L Ch R = 1 ,560     ,40,40,40
#Sta/Elev= 4
 0.00000 4.63153 0.00000-0.36847  100000-0.36847  100000 4.63153
#Mann= 3 ,0,0
 0.00000 0.03000 0.00000 0.00000 0.03000 0.00000  100000 0.03000 0.00000
Bank Sta=0,100000
XS Rating Curve= 0 ,0
Exp/Cntr=0,0

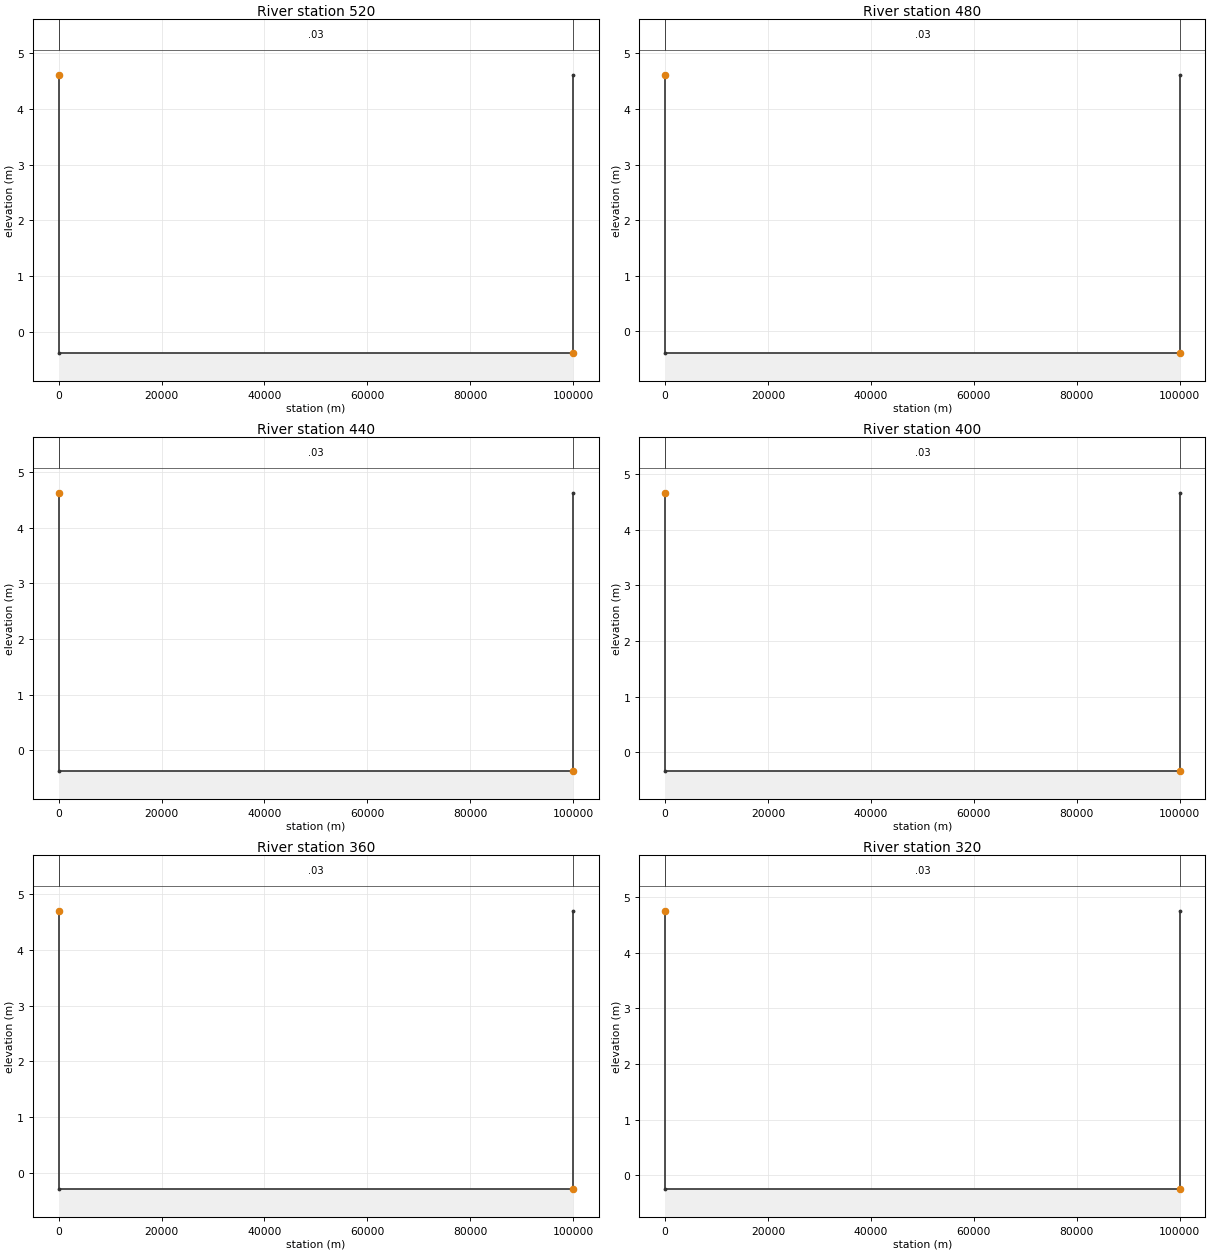
Type RM Length L Ch R = 1 ,520     ,40,40,40
#Sta/Elev= 4
 0.00000 4.61215 0.00000-0.38785  100000-0.38785  100000 4.61215
#Mann= 3 ,0,0
 0.00000 0.03000 0.00000 0.00000 0.03000 0.00000  100000 0.03000 0.00000
Bank Sta=0,100000
XS Rating Curve= 0 ,0
Exp/Cntr=0,0

Type RM Length L Ch R = 1 ,480     ,40,40,40
#Sta/Elev= 4
 0.00000 4.61114 0.00000-0.38886  100000-0.38886  100000 4.61114
#Mann= 3 ,0,0
 0.00000 0.03000 0.00000 0.00000 0.03000 0.00000  100000 0.03000 0.00000
Bank Sta=0,100000
XS Rating Curve= 0 ,0
Exp/Cntr=0,0

Type RM Length L Ch R = 1 ,440     ,40,40,40
#Sta/Elev= 4
 0.00000 4.62843 0.00000-0.37157  100000-0.37157  100000 4.62843
#Mann= 3 ,0,0
 0.00000 0.03000 0.00000 0.00000 0.03000 0.00000  100000 0.03000 0.00000
Bank Sta=0,100000
XS Rating Curve= 0 ,0
Exp/Cntr=0,0

Type RM Length L Ch R = 1 ,400     ,40,40,40
#Sta/Elev= 4
 0.00000 4.66126 0.00000-0.33874  100000-0.33874  100000 4.66126
#Mann= 3 ,0,0
 0.00000 0.03000 0.00000 0.00000 0.03000 0.00000  100000 0.03000 0.00000
Bank Sta=0,100000
XS Rating Curve= 0 ,0
Exp/Cntr=0,0

Type RM Length L Ch R = 1 ,360     ,40,40,40
#Sta/Elev= 4
 0.00000 4.70479 0.00000-0.29521  100000-0.29521  100000 4.70479
#Mann= 3 ,0,0
 0.00000 0.03000 0.00000 0.00000 0.03000 0.00000  100000 0.03000 0.00000
Bank Sta=0,100000
XS Rating Curve= 0 ,0
Exp/Cntr=0,0

Type RM Length L Ch R = 1 ,320     ,40,40,40
#Sta/Elev= 4
 0.00000 4.75326 0.00000-0.24674  100000-0.24674  100000 4.75326
#Mann= 3 ,0,0
 0.00000 0.03000 0.00000 0.00000 0.03000 0.00000  100000 0.03000 0.00000
Bank Sta=0,100000
XS Rating Curve= 0 ,0
Exp/Cntr=0,0

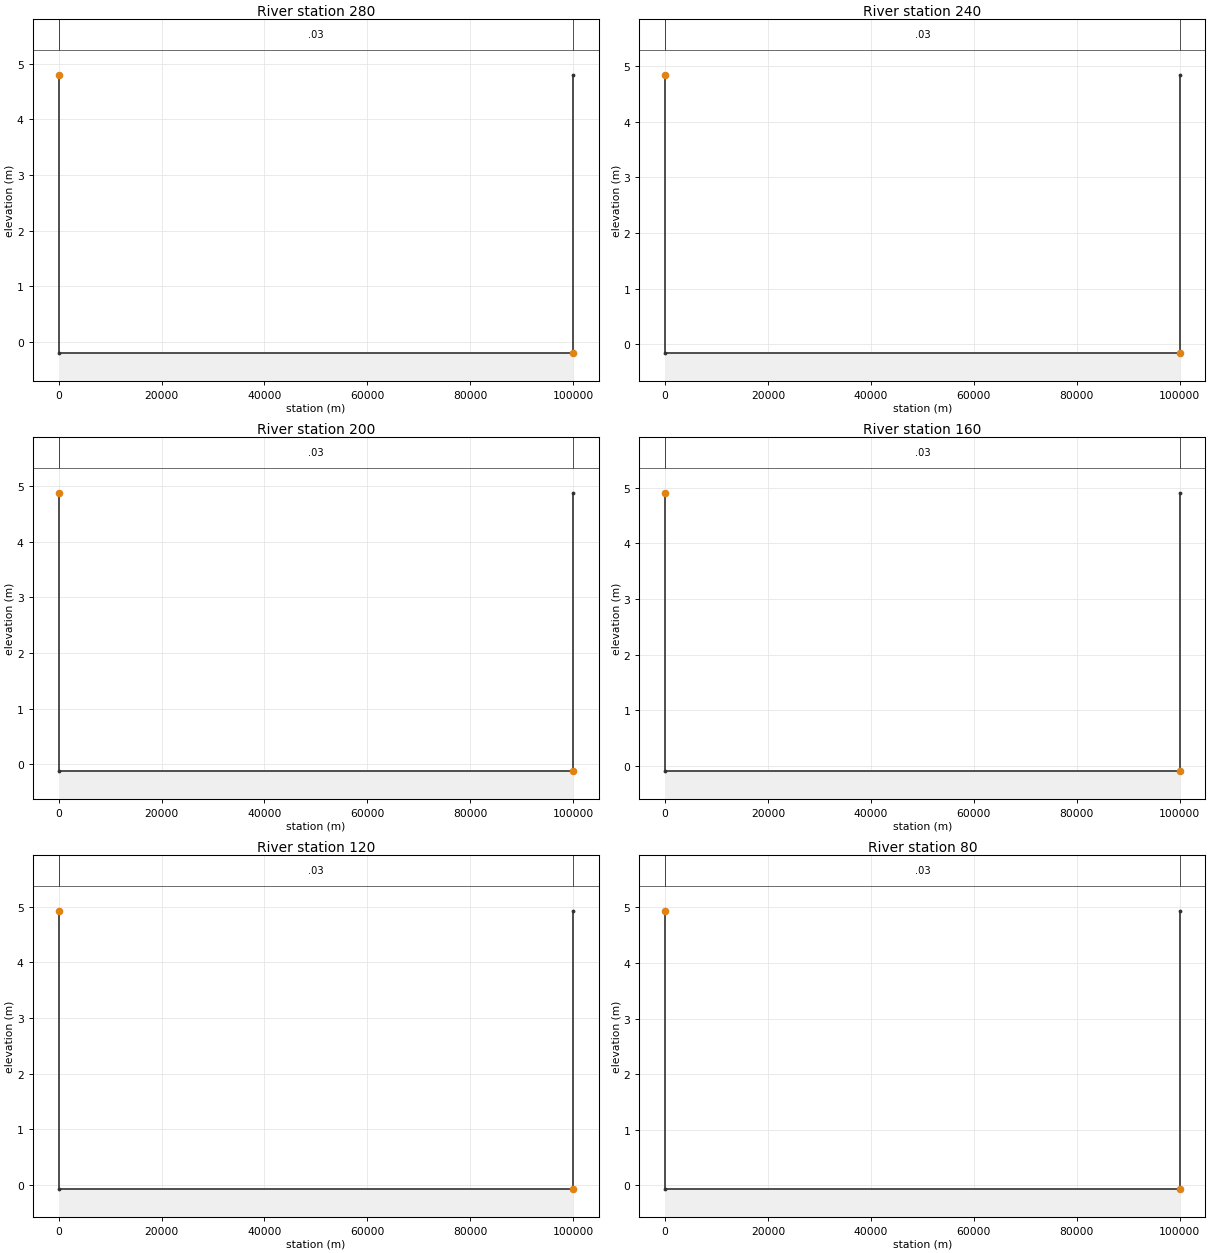
Type RM Length L Ch R = 1 ,280     ,40,40,40
#Sta/Elev= 4
 0.00000 4.80108 0.00000-0.19892  100000-0.19892  100000 4.80108
#Mann= 3 ,0,0
 0.00000 0.03000 0.00000 0.00000 0.03000 0.00000  100000 0.03000 0.00000
Bank Sta=0,100000
XS Rating Curve= 0 ,0
Exp/Cntr=0,0

Type RM Length L Ch R = 1 ,240     ,40,40,40
#Sta/Elev= 4
 0.00000  4.8439 0.00000-0.15610  100000-0.15610  100000  4.8439
#Mann= 3 ,0,0
 0.00000 0.03000 0.00000 0.00000 0.03000 0.00000  100000 0.03000 0.00000
Bank Sta=0,100000
XS Rating Curve= 0 ,0
Exp/Cntr=0,0

Type RM Length L Ch R = 1 ,200     ,40,40,40
#Sta/Elev= 4
 0.00000 4.87901 0.00000-0.12099  100000-0.12099  100000 4.87901
#Mann= 3 ,0,0
 0.00000 0.03000 0.00000 0.00000 0.03000 0.00000  100000 0.03000 0.00000
Bank Sta=0,100000
XS Rating Curve= 0 ,0
Exp/Cntr=0,0

Type RM Length L Ch R = 1 ,160     ,40,40,40
#Sta/Elev= 4
 0.00000 4.90544 0.00000-0.09456  100000-0.09456  100000 4.90544
#Mann= 3 ,0,0
 0.00000 0.03000 0.00000 0.00000 0.03000 0.00000  100000 0.03000 0.00000
Bank Sta=0,100000
XS Rating Curve= 0 ,0
Exp/Cntr=0,0

Type RM Length L Ch R = 1 ,120     ,40,40,40
#Sta/Elev= 4
 0.00000 4.92362 0.00000-0.07638  100000-0.07638  100000 4.92362
#Mann= 3 ,0,0
 0.00000 0.03000 0.00000 0.00000 0.03000 0.00000  100000 0.03000 0.00000
Bank Sta=0,100000
XS Rating Curve= 0 ,0
Exp/Cntr=0,0

Type RM Length L Ch R = 1 ,80      ,40,40,40
#Sta/Elev= 4
 0.00000 4.93479 0.00000-0.06521  100000-0.06521  100000 4.93479
#Mann= 3 ,0,0
 0.00000 0.03000 0.00000 0.00000 0.03000 0.00000  100000 0.03000 0.00000
Bank Sta=0,100000
XS Rating Curve= 0 ,0
Exp/Cntr=0,0

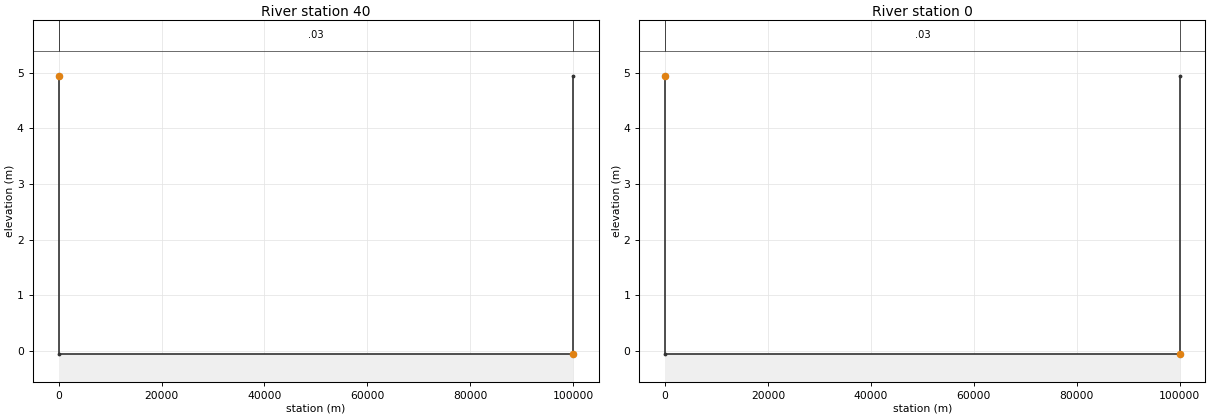
Type RM Length L Ch R = 1 ,40      ,40,40,40
#Sta/Elev= 4
 0.00000 4.94058 0.00000-0.05942  100000-0.05942  100000 4.94058
#Mann= 3 ,0,0
 0.00000 0.03000 0.00000 0.00000 0.03000 0.00000  100000 0.03000 0.00000
Bank Sta=0,100000
XS Rating Curve= 0 ,0
Exp/Cntr=0,0

Type RM Length L Ch R = 1 ,0       ,0,0,0
#Sta/Elev= 4
 0.00000 4.94254 0.00000-0.05746  100000-0.05746  100000 4.94254
#Mann= 3 ,0,0
 0.00000 0.03000 0.00000 0.00000 0.03000 0.00000  100000 0.03000 0.00000
Bank Sta=0,100000
XS Rating Curve= 0 ,0
Exp/Cntr=0,0