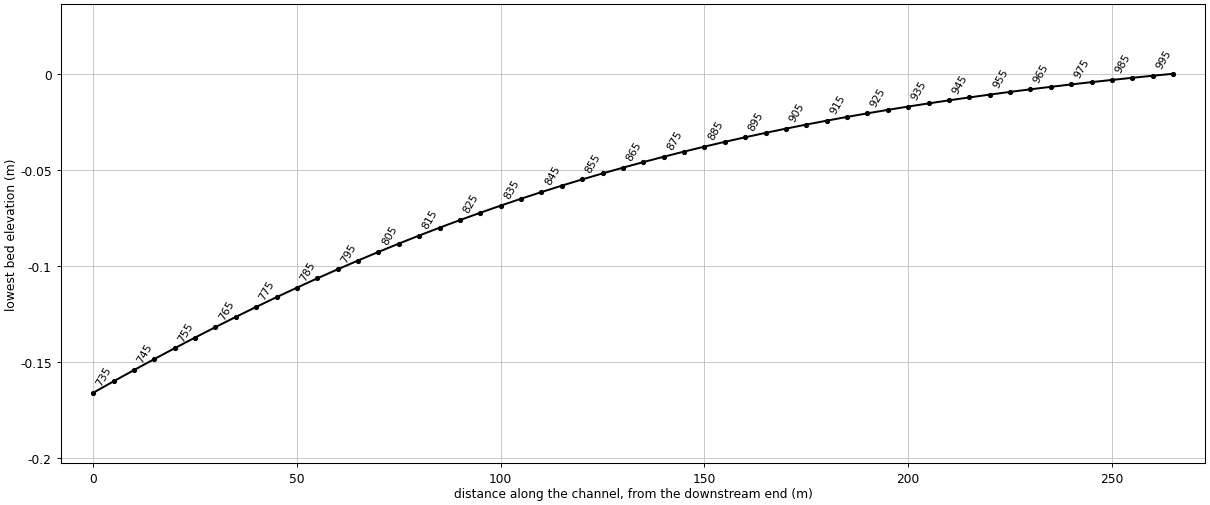
--- macdonald.prj (project) ---

Proj Title=A1F-001 MacDonald backwater dx=5 m
Current Plan=p01
Default Exp/Contr=0,0
SI Units
Geom File=g01
Flow File=f01
Plan File=p01
Y Axis Title=Elevation
X Axis Title(PF)=Main Channel Distance
X Axis Title(XS)=Station
BEGIN DESCRIPTION:
A1F-001 MacDonald backwater dx=5 m
END DESCRIPTION:

--- macdonald.p01 (plan) ---

Plan Title=A1F-001 MacDonald backwater dx=5 m
Program Version=6.60
Short Identifier=dx5
Geom File=g01
Flow File=f01
Subcritical Flow
K Sum by GR= 0
Std Step Tol= .00001
Critical Tol= .00001
Num of Std Step Trials= 40
Max Error Tol= .3
Flow Tol Ratio= .001
Log Output Level= 0
Friction Slope Method= 1

--- macdonald.f01 (steady flow) ---

Flow Title=A1F-001 MacDonald backwater dx=5 m
Program Version=6.60
Number of Profiles= 1
Profile Names=PF 1
River Rch & RM=Channel,Main            ,1000
   20000
Boundary for River Rch & Prof#=Channel,Main            , 1
Up Type= 0
Dn Type= 1
Dn Known WS=0.690867

--- macdonald.g01 (geometry) ---

Geom Title=A1F-001 MacDonald backwater dx=5 m
Program Version=6.60

River Reach=Channel         ,Main
Reach XY= 2
          0.5000          1.0000          0.5000          0.0000

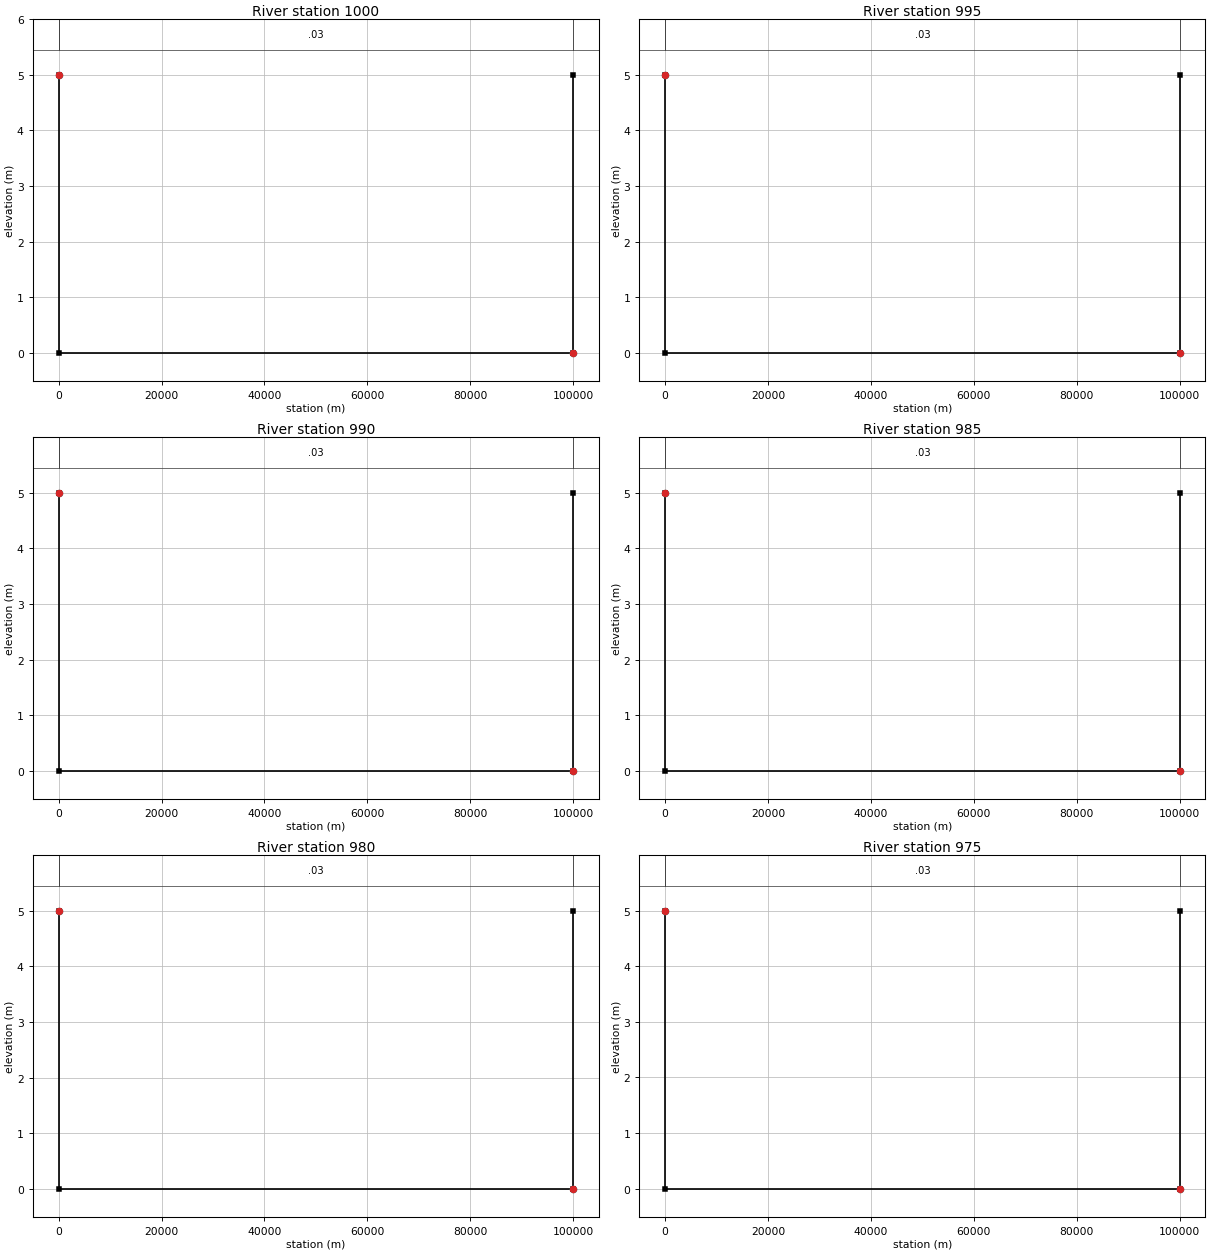
Type RM Length L Ch R = 1 ,1000    ,5,5,5
#Sta/Elev= 4
 0.00000       5 0.00000 0.00000  100000 0.00000  100000       5
#Mann= 3 ,0,0
 0.00000 0.03000 0.00000 0.00000 0.03000 0.00000  100000 0.03000 0.00000
Bank Sta=0,100000
XS Rating Curve= 0 ,0
Exp/Cntr=0,0

Type RM Length L Ch R = 1 ,995     ,5,5,5
#Sta/Elev= 4
 0.00000 4.99897 0.00000-0.00103  100000-0.00103  100000 4.99897
#Mann= 3 ,0,0
 0.00000 0.03000 0.00000 0.00000 0.03000 0.00000  100000 0.03000 0.00000
Bank Sta=0,100000
XS Rating Curve= 0 ,0
Exp/Cntr=0,0

Type RM Length L Ch R = 1 ,990     ,5,5,5
#Sta/Elev= 4
 0.00000  4.9979 0.00000-0.00210  100000-0.00210  100000  4.9979
#Mann= 3 ,0,0
 0.00000 0.03000 0.00000 0.00000 0.03000 0.00000  100000 0.03000 0.00000
Bank Sta=0,100000
XS Rating Curve= 0 ,0
Exp/Cntr=0,0

Type RM Length L Ch R = 1 ,985     ,5,5,5
#Sta/Elev= 4
 0.00000 4.99679 0.00000-0.00321  100000-0.00321  100000 4.99679
#Mann= 3 ,0,0
 0.00000 0.03000 0.00000 0.00000 0.03000 0.00000  100000 0.03000 0.00000
Bank Sta=0,100000
XS Rating Curve= 0 ,0
Exp/Cntr=0,0

Type RM Length L Ch R = 1 ,980     ,5,5,5
#Sta/Elev= 4
 0.00000 4.99564 0.00000-0.00436  100000-0.00436  100000 4.99564
#Mann= 3 ,0,0
 0.00000 0.03000 0.00000 0.00000 0.03000 0.00000  100000 0.03000 0.00000
Bank Sta=0,100000
XS Rating Curve= 0 ,0
Exp/Cntr=0,0

Type RM Length L Ch R = 1 ,975     ,5,5,5
#Sta/Elev= 4
 0.00000 4.99444 0.00000-0.00556  100000-0.00556  100000 4.99444
#Mann= 3 ,0,0
 0.00000 0.03000 0.00000 0.00000 0.03000 0.00000  100000 0.03000 0.00000
Bank Sta=0,100000
XS Rating Curve= 0 ,0
Exp/Cntr=0,0

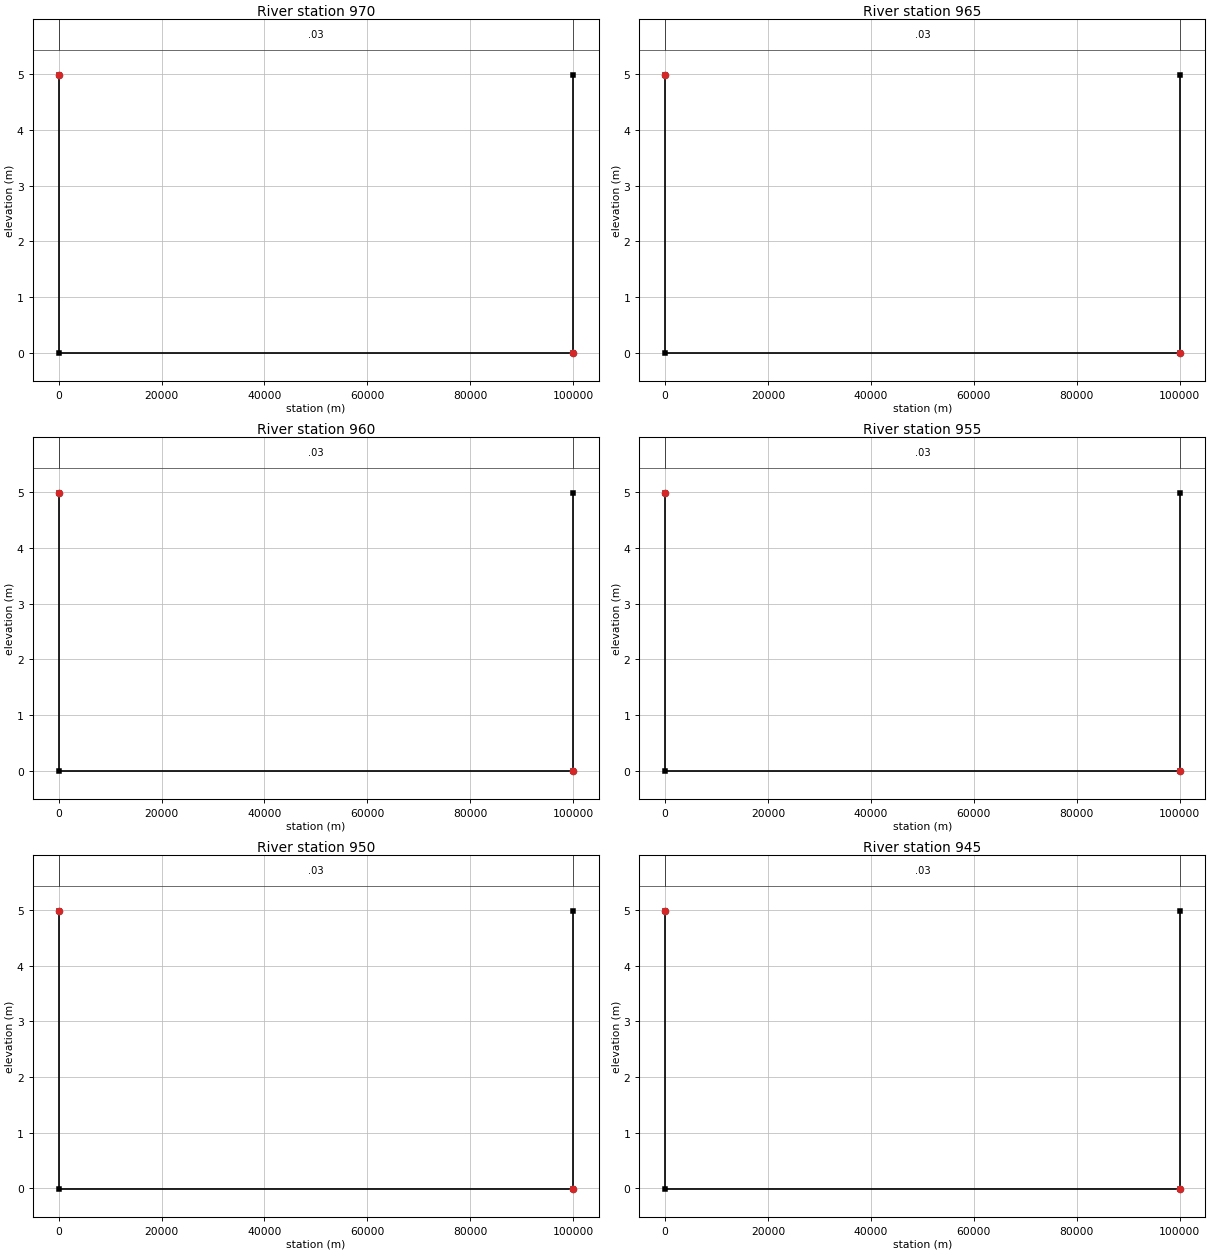
Type RM Length L Ch R = 1 ,970     ,5,5,5
#Sta/Elev= 4
 0.00000  4.9932 0.00000-0.00680  100000-0.00680  100000  4.9932
#Mann= 3 ,0,0
 0.00000 0.03000 0.00000 0.00000 0.03000 0.00000  100000 0.03000 0.00000
Bank Sta=0,100000
XS Rating Curve= 0 ,0
Exp/Cntr=0,0

Type RM Length L Ch R = 1 ,965     ,5,5,5
#Sta/Elev= 4
 0.00000  4.9919 0.00000-0.00810  100000-0.00810  100000  4.9919
#Mann= 3 ,0,0
 0.00000 0.03000 0.00000 0.00000 0.03000 0.00000  100000 0.03000 0.00000
Bank Sta=0,100000
XS Rating Curve= 0 ,0
Exp/Cntr=0,0

Type RM Length L Ch R = 1 ,960     ,5,5,5
#Sta/Elev= 4
 0.00000 4.99055 0.00000-0.00945  100000-0.00945  100000 4.99055
#Mann= 3 ,0,0
 0.00000 0.03000 0.00000 0.00000 0.03000 0.00000  100000 0.03000 0.00000
Bank Sta=0,100000
XS Rating Curve= 0 ,0
Exp/Cntr=0,0

Type RM Length L Ch R = 1 ,955     ,5,5,5
#Sta/Elev= 4
 0.00000 4.98915 0.00000-0.01085  100000-0.01085  100000 4.98915
#Mann= 3 ,0,0
 0.00000 0.03000 0.00000 0.00000 0.03000 0.00000  100000 0.03000 0.00000
Bank Sta=0,100000
XS Rating Curve= 0 ,0
Exp/Cntr=0,0

Type RM Length L Ch R = 1 ,950     ,5,5,5
#Sta/Elev= 4
 0.00000 4.98768 0.00000-0.01232  100000-0.01232  100000 4.98768
#Mann= 3 ,0,0
 0.00000 0.03000 0.00000 0.00000 0.03000 0.00000  100000 0.03000 0.00000
Bank Sta=0,100000
XS Rating Curve= 0 ,0
Exp/Cntr=0,0

Type RM Length L Ch R = 1 ,945     ,5,5,5
#Sta/Elev= 4
 0.00000 4.98616 0.00000-0.01384  100000-0.01384  100000 4.98616
#Mann= 3 ,0,0
 0.00000 0.03000 0.00000 0.00000 0.03000 0.00000  100000 0.03000 0.00000
Bank Sta=0,100000
XS Rating Curve= 0 ,0
Exp/Cntr=0,0

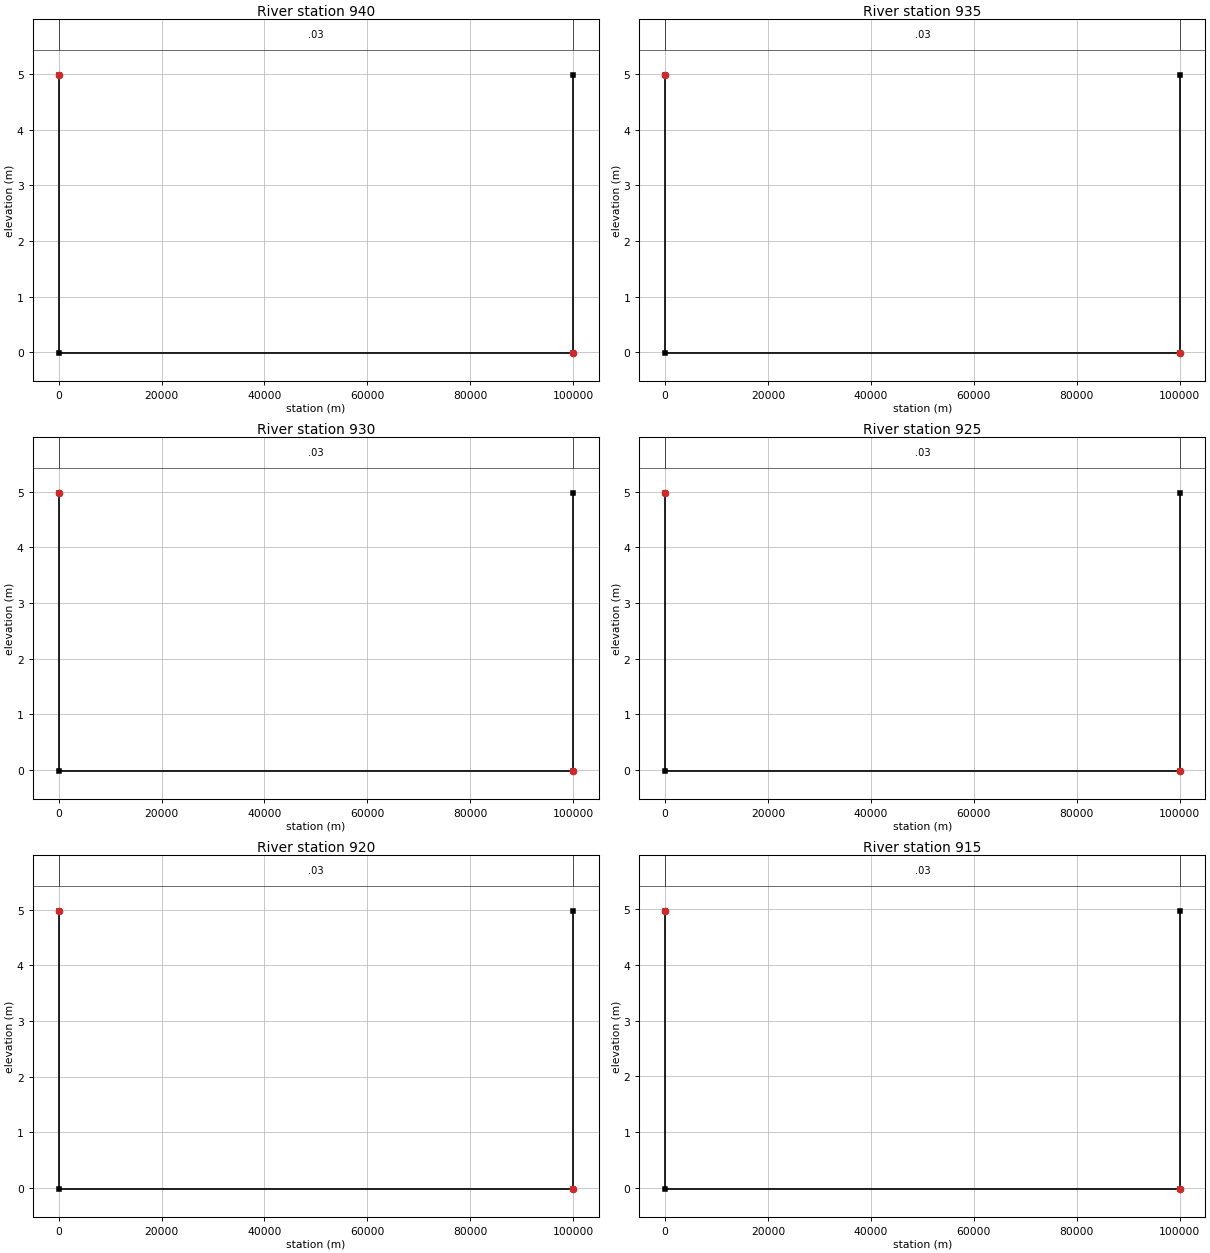
Type RM Length L Ch R = 1 ,940     ,5,5,5
#Sta/Elev= 4
 0.00000 4.98457 0.00000-0.01543  100000-0.01543  100000 4.98457
#Mann= 3 ,0,0
 0.00000 0.03000 0.00000 0.00000 0.03000 0.00000  100000 0.03000 0.00000
Bank Sta=0,100000
XS Rating Curve= 0 ,0
Exp/Cntr=0,0

Type RM Length L Ch R = 1 ,935     ,5,5,5
#Sta/Elev= 4
 0.00000 4.98292 0.00000-0.01708  100000-0.01708  100000 4.98292
#Mann= 3 ,0,0
 0.00000 0.03000 0.00000 0.00000 0.03000 0.00000  100000 0.03000 0.00000
Bank Sta=0,100000
XS Rating Curve= 0 ,0
Exp/Cntr=0,0

Type RM Length L Ch R = 1 ,930     ,5,5,5
#Sta/Elev= 4
 0.00000  4.9812 0.00000-0.01880  100000-0.01880  100000  4.9812
#Mann= 3 ,0,0
 0.00000 0.03000 0.00000 0.00000 0.03000 0.00000  100000 0.03000 0.00000
Bank Sta=0,100000
XS Rating Curve= 0 ,0
Exp/Cntr=0,0

Type RM Length L Ch R = 1 ,925     ,5,5,5
#Sta/Elev= 4
 0.00000  4.9794 0.00000-0.02060  100000-0.02060  100000  4.9794
#Mann= 3 ,0,0
 0.00000 0.03000 0.00000 0.00000 0.03000 0.00000  100000 0.03000 0.00000
Bank Sta=0,100000
XS Rating Curve= 0 ,0
Exp/Cntr=0,0

Type RM Length L Ch R = 1 ,920     ,5,5,5
#Sta/Elev= 4
 0.00000 4.97753 0.00000-0.02247  100000-0.02247  100000 4.97753
#Mann= 3 ,0,0
 0.00000 0.03000 0.00000 0.00000 0.03000 0.00000  100000 0.03000 0.00000
Bank Sta=0,100000
XS Rating Curve= 0 ,0
Exp/Cntr=0,0

Type RM Length L Ch R = 1 ,915     ,5,5,5
#Sta/Elev= 4
 0.00000 4.97558 0.00000-0.02442  100000-0.02442  100000 4.97558
#Mann= 3 ,0,0
 0.00000 0.03000 0.00000 0.00000 0.03000 0.00000  100000 0.03000 0.00000
Bank Sta=0,100000
XS Rating Curve= 0 ,0
Exp/Cntr=0,0

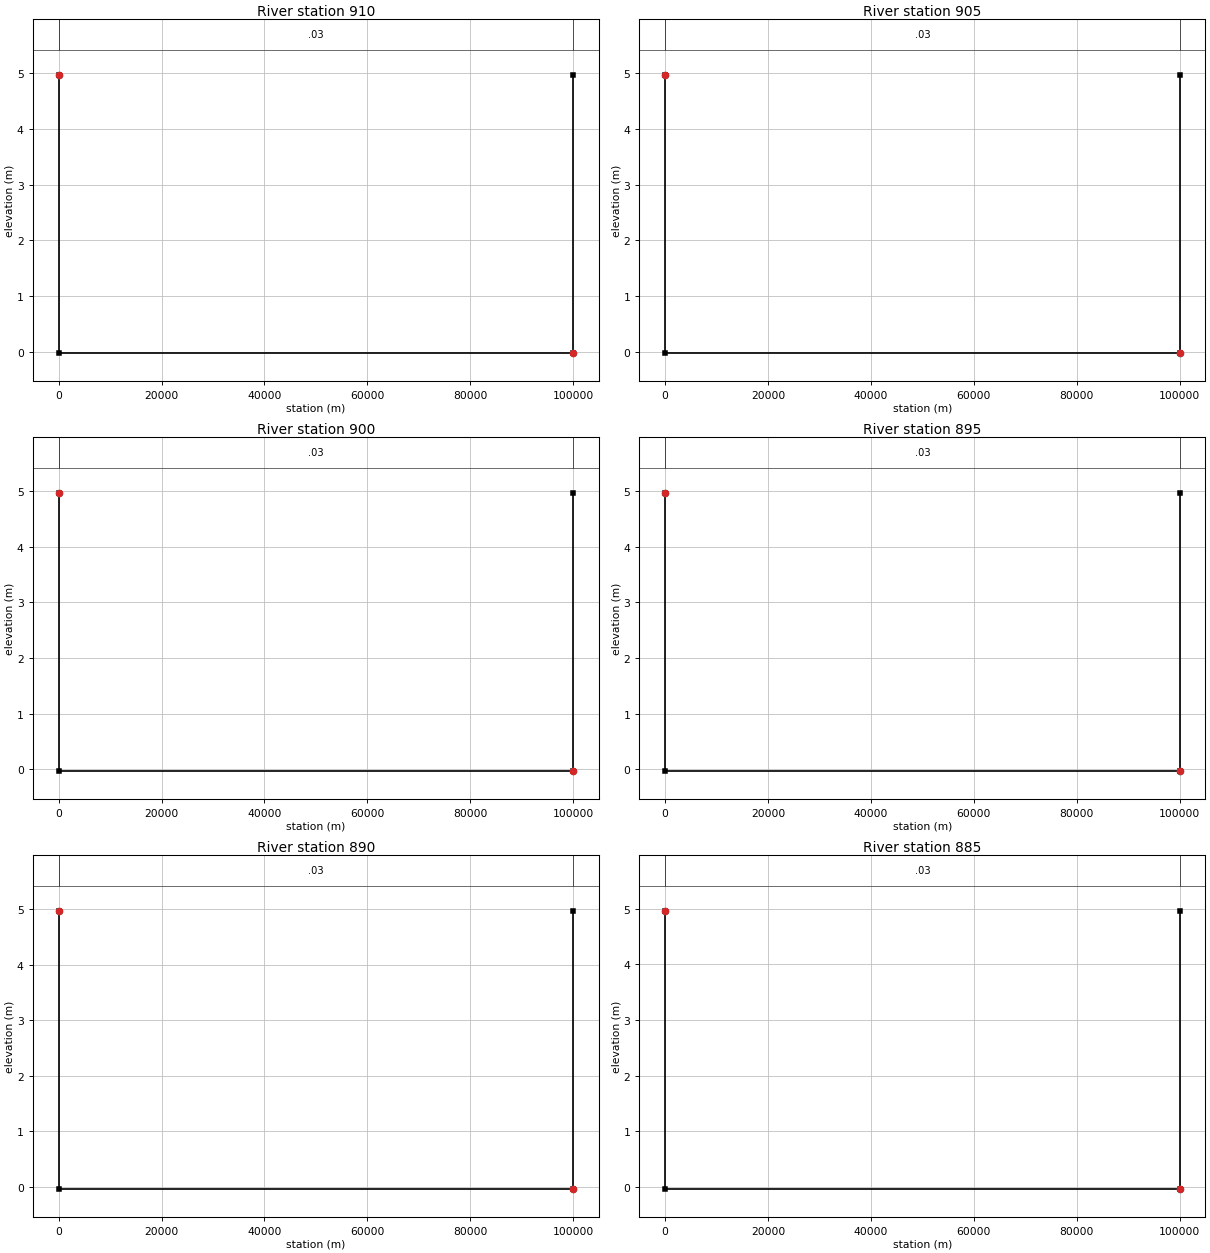
Type RM Length L Ch R = 1 ,910     ,5,5,5
#Sta/Elev= 4
 0.00000 4.97355 0.00000-0.02645  100000-0.02645  100000 4.97355
#Mann= 3 ,0,0
 0.00000 0.03000 0.00000 0.00000 0.03000 0.00000  100000 0.03000 0.00000
Bank Sta=0,100000
XS Rating Curve= 0 ,0
Exp/Cntr=0,0

Type RM Length L Ch R = 1 ,905     ,5,5,5
#Sta/Elev= 4
 0.00000 4.97143 0.00000-0.02857  100000-0.02857  100000 4.97143
#Mann= 3 ,0,0
 0.00000 0.03000 0.00000 0.00000 0.03000 0.00000  100000 0.03000 0.00000
Bank Sta=0,100000
XS Rating Curve= 0 ,0
Exp/Cntr=0,0

Type RM Length L Ch R = 1 ,900     ,5,5,5
#Sta/Elev= 4
 0.00000 4.96923 0.00000-0.03077  100000-0.03077  100000 4.96923
#Mann= 3 ,0,0
 0.00000 0.03000 0.00000 0.00000 0.03000 0.00000  100000 0.03000 0.00000
Bank Sta=0,100000
XS Rating Curve= 0 ,0
Exp/Cntr=0,0

Type RM Length L Ch R = 1 ,895     ,5,5,5
#Sta/Elev= 4
 0.00000 4.96693 0.00000-0.03307  100000-0.03307  100000 4.96693
#Mann= 3 ,0,0
 0.00000 0.03000 0.00000 0.00000 0.03000 0.00000  100000 0.03000 0.00000
Bank Sta=0,100000
XS Rating Curve= 0 ,0
Exp/Cntr=0,0

Type RM Length L Ch R = 1 ,890     ,5,5,5
#Sta/Elev= 4
 0.00000 4.96455 0.00000-0.03545  100000-0.03545  100000 4.96455
#Mann= 3 ,0,0
 0.00000 0.03000 0.00000 0.00000 0.03000 0.00000  100000 0.03000 0.00000
Bank Sta=0,100000
XS Rating Curve= 0 ,0
Exp/Cntr=0,0

Type RM Length L Ch R = 1 ,885     ,5,5,5
#Sta/Elev= 4
 0.00000 4.96206 0.00000-0.03794  100000-0.03794  100000 4.96206
#Mann= 3 ,0,0
 0.00000 0.03000 0.00000 0.00000 0.03000 0.00000  100000 0.03000 0.00000
Bank Sta=0,100000
XS Rating Curve= 0 ,0
Exp/Cntr=0,0

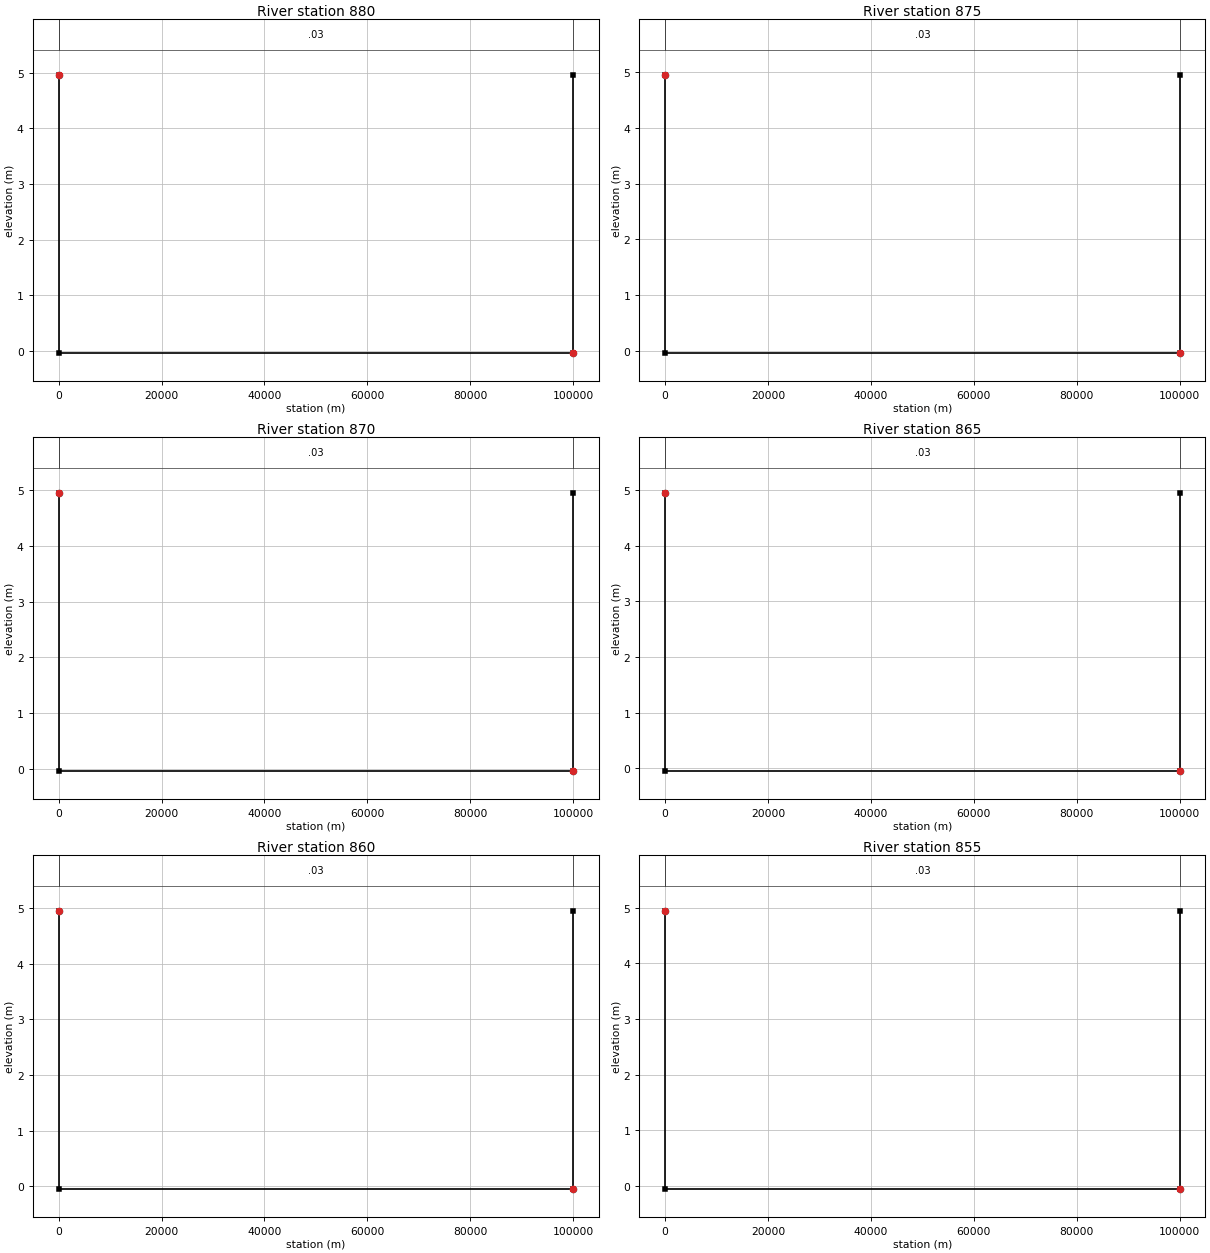
Type RM Length L Ch R = 1 ,880     ,5,5,5
#Sta/Elev= 4
 0.00000 4.95948 0.00000-0.04052  100000-0.04052  100000 4.95948
#Mann= 3 ,0,0
 0.00000 0.03000 0.00000 0.00000 0.03000 0.00000  100000 0.03000 0.00000
Bank Sta=0,100000
XS Rating Curve= 0 ,0
Exp/Cntr=0,0

Type RM Length L Ch R = 1 ,875     ,5,5,5
#Sta/Elev= 4
 0.00000  4.9568 0.00000-0.04320  100000-0.04320  100000  4.9568
#Mann= 3 ,0,0
 0.00000 0.03000 0.00000 0.00000 0.03000 0.00000  100000 0.03000 0.00000
Bank Sta=0,100000
XS Rating Curve= 0 ,0
Exp/Cntr=0,0

Type RM Length L Ch R = 1 ,870     ,5,5,5
#Sta/Elev= 4
 0.00000 4.95401 0.00000-0.04599  100000-0.04599  100000 4.95401
#Mann= 3 ,0,0
 0.00000 0.03000 0.00000 0.00000 0.03000 0.00000  100000 0.03000 0.00000
Bank Sta=0,100000
XS Rating Curve= 0 ,0
Exp/Cntr=0,0

Type RM Length L Ch R = 1 ,865     ,5,5,5
#Sta/Elev= 4
 0.00000 4.95111 0.00000-0.04889  100000-0.04889  100000 4.95111
#Mann= 3 ,0,0
 0.00000 0.03000 0.00000 0.00000 0.03000 0.00000  100000 0.03000 0.00000
Bank Sta=0,100000
XS Rating Curve= 0 ,0
Exp/Cntr=0,0

Type RM Length L Ch R = 1 ,860     ,5,5,5
#Sta/Elev= 4
 0.00000 4.94811 0.00000-0.05189  100000-0.05189  100000 4.94811
#Mann= 3 ,0,0
 0.00000 0.03000 0.00000 0.00000 0.03000 0.00000  100000 0.03000 0.00000
Bank Sta=0,100000
XS Rating Curve= 0 ,0
Exp/Cntr=0,0

Type RM Length L Ch R = 1 ,855     ,5,5,5
#Sta/Elev= 4
 0.00000 4.94499 0.00000-0.05501  100000-0.05501  100000 4.94499
#Mann= 3 ,0,0
 0.00000 0.03000 0.00000 0.00000 0.03000 0.00000  100000 0.03000 0.00000
Bank Sta=0,100000
XS Rating Curve= 0 ,0
Exp/Cntr=0,0

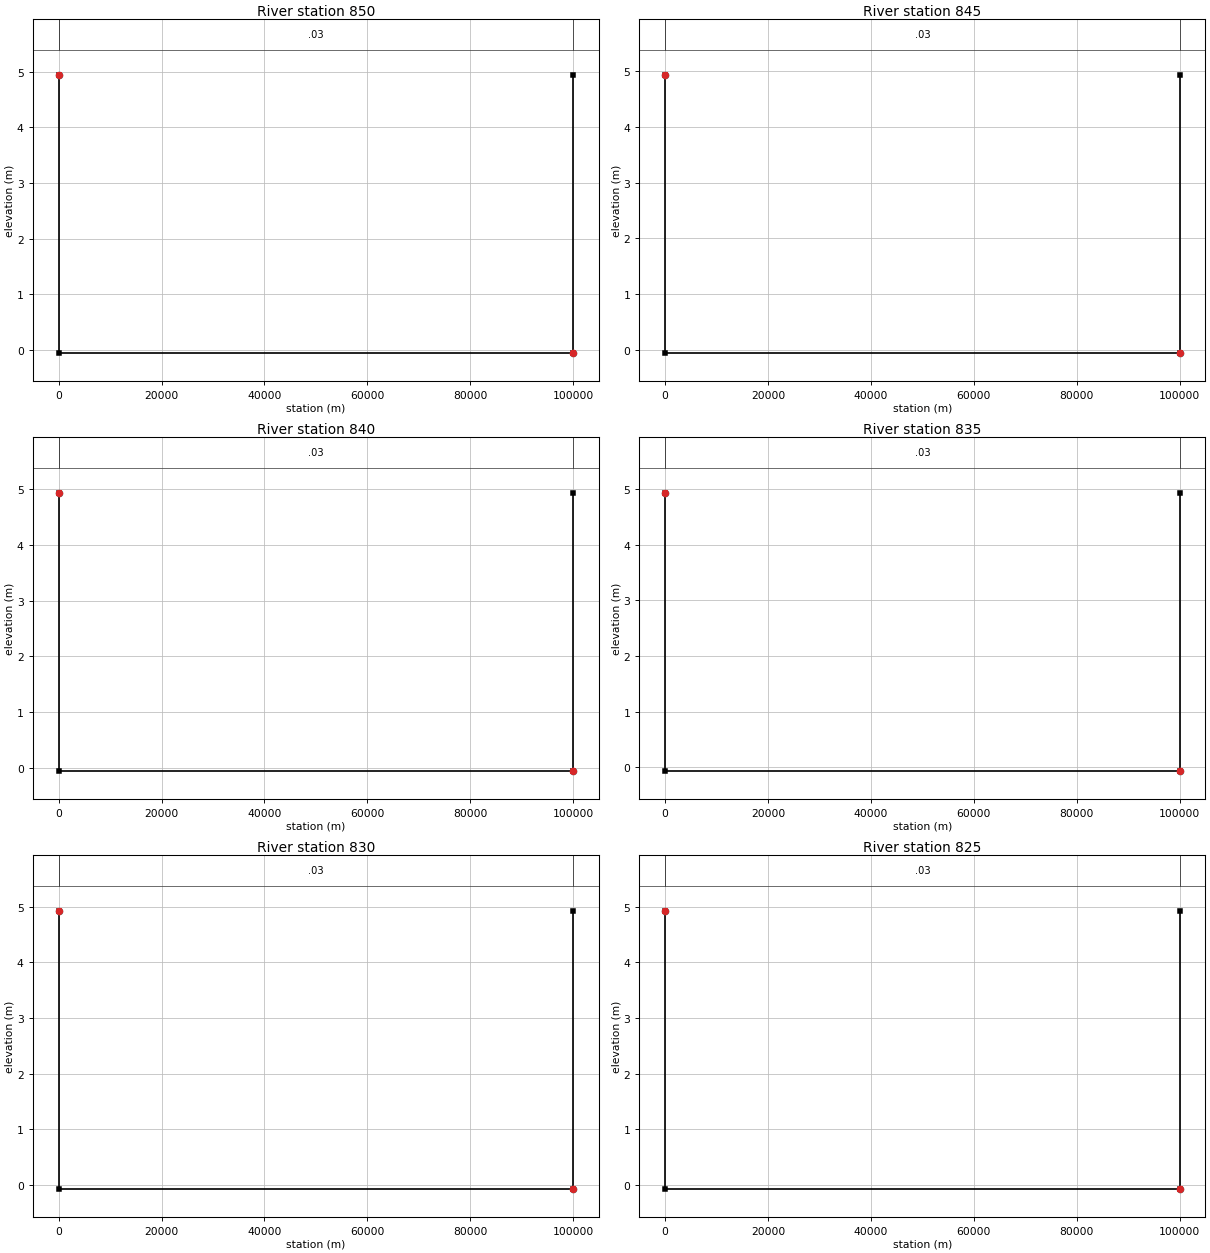
Type RM Length L Ch R = 1 ,850     ,5,5,5
#Sta/Elev= 4
 0.00000 4.94176 0.00000-0.05824  100000-0.05824  100000 4.94176
#Mann= 3 ,0,0
 0.00000 0.03000 0.00000 0.00000 0.03000 0.00000  100000 0.03000 0.00000
Bank Sta=0,100000
XS Rating Curve= 0 ,0
Exp/Cntr=0,0

Type RM Length L Ch R = 1 ,845     ,5,5,5
#Sta/Elev= 4
 0.00000 4.93841 0.00000-0.06159  100000-0.06159  100000 4.93841
#Mann= 3 ,0,0
 0.00000 0.03000 0.00000 0.00000 0.03000 0.00000  100000 0.03000 0.00000
Bank Sta=0,100000
XS Rating Curve= 0 ,0
Exp/Cntr=0,0

Type RM Length L Ch R = 1 ,840     ,5,5,5
#Sta/Elev= 4
 0.00000 4.93495 0.00000-0.06505  100000-0.06505  100000 4.93495
#Mann= 3 ,0,0
 0.00000 0.03000 0.00000 0.00000 0.03000 0.00000  100000 0.03000 0.00000
Bank Sta=0,100000
XS Rating Curve= 0 ,0
Exp/Cntr=0,0

Type RM Length L Ch R = 1 ,835     ,5,5,5
#Sta/Elev= 4
 0.00000 4.93136 0.00000-0.06864  100000-0.06864  100000 4.93136
#Mann= 3 ,0,0
 0.00000 0.03000 0.00000 0.00000 0.03000 0.00000  100000 0.03000 0.00000
Bank Sta=0,100000
XS Rating Curve= 0 ,0
Exp/Cntr=0,0

Type RM Length L Ch R = 1 ,830     ,5,5,5
#Sta/Elev= 4
 0.00000 4.92765 0.00000-0.07235  100000-0.07235  100000 4.92765
#Mann= 3 ,0,0
 0.00000 0.03000 0.00000 0.00000 0.03000 0.00000  100000 0.03000 0.00000
Bank Sta=0,100000
XS Rating Curve= 0 ,0
Exp/Cntr=0,0

Type RM Length L Ch R = 1 ,825     ,5,5,5
#Sta/Elev= 4
 0.00000 4.92382 0.00000-0.07618  100000-0.07618  100000 4.92382
#Mann= 3 ,0,0
 0.00000 0.03000 0.00000 0.00000 0.03000 0.00000  100000 0.03000 0.00000
Bank Sta=0,100000
XS Rating Curve= 0 ,0
Exp/Cntr=0,0

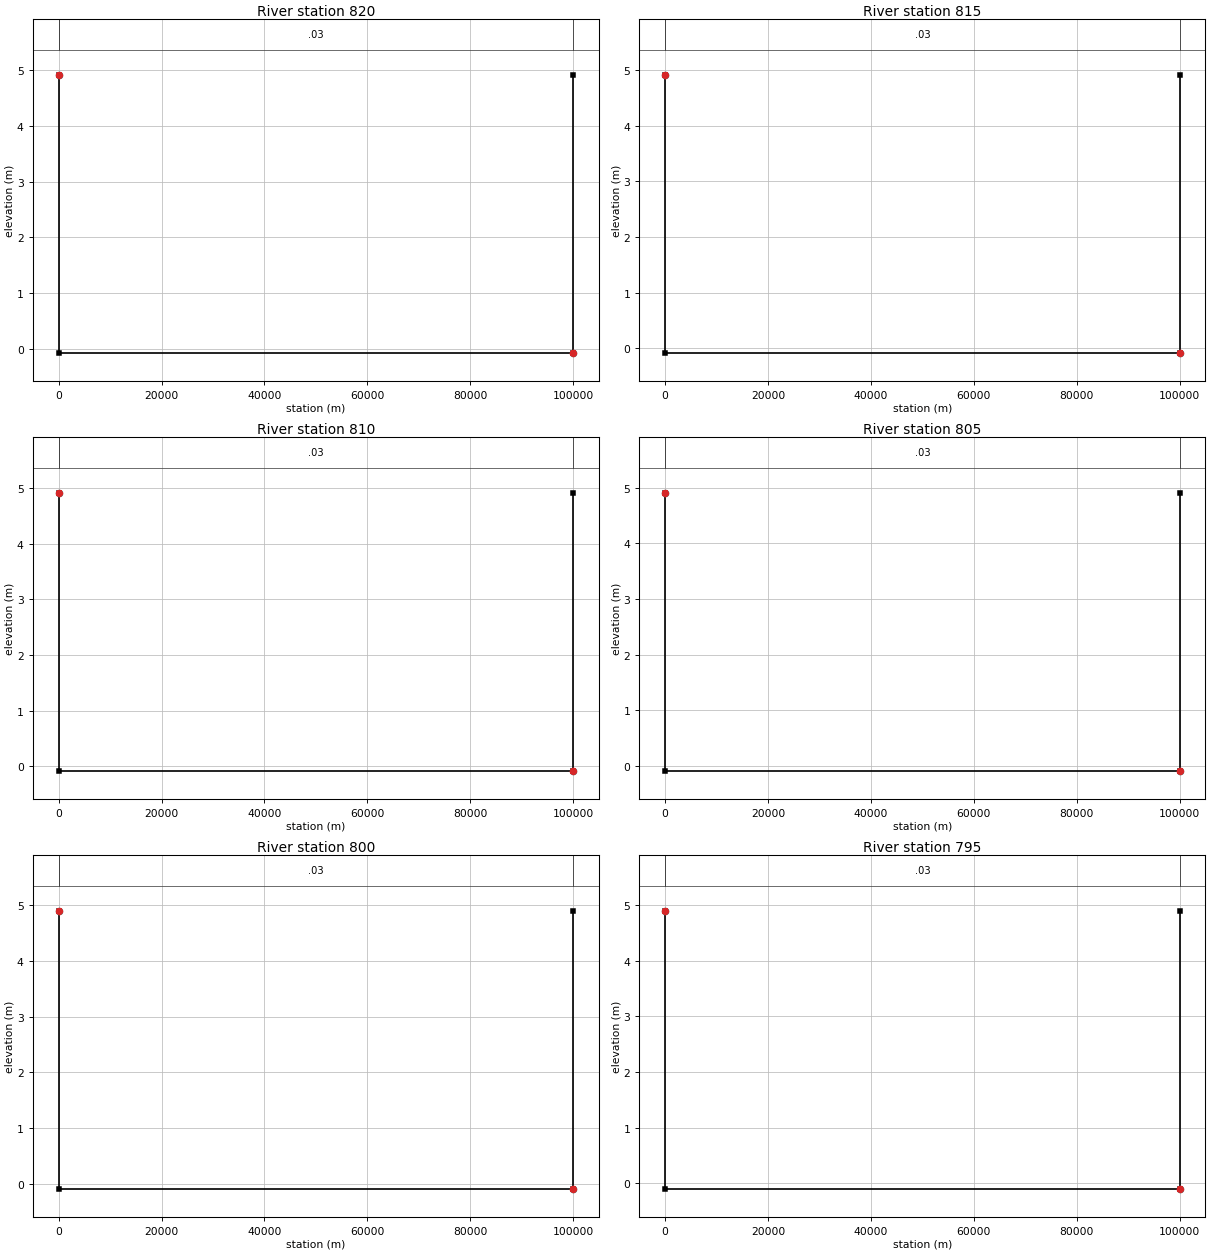
Type RM Length L Ch R = 1 ,820     ,5,5,5
#Sta/Elev= 4
 0.00000 4.91986 0.00000-0.08014  100000-0.08014  100000 4.91986
#Mann= 3 ,0,0
 0.00000 0.03000 0.00000 0.00000 0.03000 0.00000  100000 0.03000 0.00000
Bank Sta=0,100000
XS Rating Curve= 0 ,0
Exp/Cntr=0,0

Type RM Length L Ch R = 1 ,815     ,5,5,5
#Sta/Elev= 4
 0.00000 4.91578 0.00000-0.08422  100000-0.08422  100000 4.91578
#Mann= 3 ,0,0
 0.00000 0.03000 0.00000 0.00000 0.03000 0.00000  100000 0.03000 0.00000
Bank Sta=0,100000
XS Rating Curve= 0 ,0
Exp/Cntr=0,0

Type RM Length L Ch R = 1 ,810     ,5,5,5
#Sta/Elev= 4
 0.00000 4.91158 0.00000-0.08842  100000-0.08842  100000 4.91158
#Mann= 3 ,0,0
 0.00000 0.03000 0.00000 0.00000 0.03000 0.00000  100000 0.03000 0.00000
Bank Sta=0,100000
XS Rating Curve= 0 ,0
Exp/Cntr=0,0

Type RM Length L Ch R = 1 ,805     ,5,5,5
#Sta/Elev= 4
 0.00000 4.90724 0.00000-0.09276  100000-0.09276  100000 4.90724
#Mann= 3 ,0,0
 0.00000 0.03000 0.00000 0.00000 0.03000 0.00000  100000 0.03000 0.00000
Bank Sta=0,100000
XS Rating Curve= 0 ,0
Exp/Cntr=0,0

Type RM Length L Ch R = 1 ,800     ,5,5,5
#Sta/Elev= 4
 0.00000 4.90278 0.00000-0.09722  100000-0.09722  100000 4.90278
#Mann= 3 ,0,0
 0.00000 0.03000 0.00000 0.00000 0.03000 0.00000  100000 0.03000 0.00000
Bank Sta=0,100000
XS Rating Curve= 0 ,0
Exp/Cntr=0,0

Type RM Length L Ch R = 1 ,795     ,5,5,5
#Sta/Elev= 4
 0.00000  4.8982 0.00000-0.10180  100000-0.10180  100000  4.8982
#Mann= 3 ,0,0
 0.00000 0.03000 0.00000 0.00000 0.03000 0.00000  100000 0.03000 0.00000
Bank Sta=0,100000
XS Rating Curve= 0 ,0
Exp/Cntr=0,0

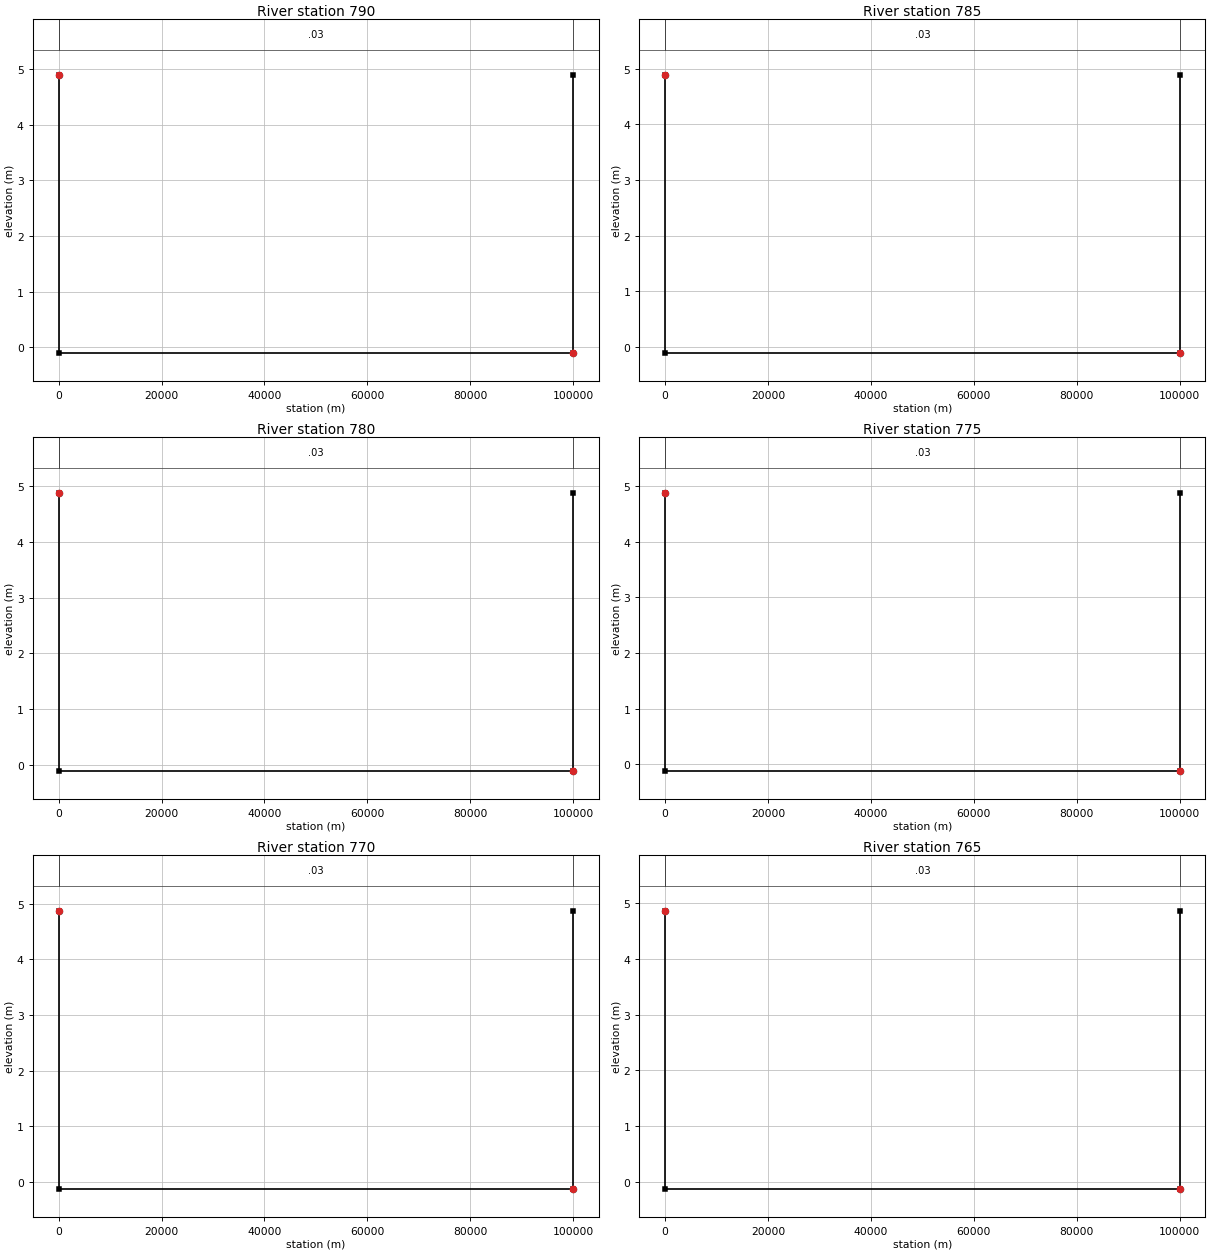
Type RM Length L Ch R = 1 ,790     ,5,5,5
#Sta/Elev= 4
 0.00000 4.89349 0.00000-0.10651  100000-0.10651  100000 4.89349
#Mann= 3 ,0,0
 0.00000 0.03000 0.00000 0.00000 0.03000 0.00000  100000 0.03000 0.00000
Bank Sta=0,100000
XS Rating Curve= 0 ,0
Exp/Cntr=0,0

Type RM Length L Ch R = 1 ,785     ,5,5,5
#Sta/Elev= 4
 0.00000 4.88865 0.00000-0.11135  100000-0.11135  100000 4.88865
#Mann= 3 ,0,0
 0.00000 0.03000 0.00000 0.00000 0.03000 0.00000  100000 0.03000 0.00000
Bank Sta=0,100000
XS Rating Curve= 0 ,0
Exp/Cntr=0,0

Type RM Length L Ch R = 1 ,780     ,5,5,5
#Sta/Elev= 4
 0.00000 4.88369 0.00000-0.11631  100000-0.11631  100000 4.88369
#Mann= 3 ,0,0
 0.00000 0.03000 0.00000 0.00000 0.03000 0.00000  100000 0.03000 0.00000
Bank Sta=0,100000
XS Rating Curve= 0 ,0
Exp/Cntr=0,0

Type RM Length L Ch R = 1 ,775     ,5,5,5
#Sta/Elev= 4
 0.00000 4.87862 0.00000-0.12138  100000-0.12138  100000 4.87862
#Mann= 3 ,0,0
 0.00000 0.03000 0.00000 0.00000 0.03000 0.00000  100000 0.03000 0.00000
Bank Sta=0,100000
XS Rating Curve= 0 ,0
Exp/Cntr=0,0

Type RM Length L Ch R = 1 ,770     ,5,5,5
#Sta/Elev= 4
 0.00000 4.87342 0.00000-0.12658  100000-0.12658  100000 4.87342
#Mann= 3 ,0,0
 0.00000 0.03000 0.00000 0.00000 0.03000 0.00000  100000 0.03000 0.00000
Bank Sta=0,100000
XS Rating Curve= 0 ,0
Exp/Cntr=0,0

Type RM Length L Ch R = 1 ,765     ,5,5,5
#Sta/Elev= 4
 0.00000  4.8681 0.00000-0.13190  100000-0.13190  100000  4.8681
#Mann= 3 ,0,0
 0.00000 0.03000 0.00000 0.00000 0.03000 0.00000  100000 0.03000 0.00000
Bank Sta=0,100000
XS Rating Curve= 0 ,0
Exp/Cntr=0,0

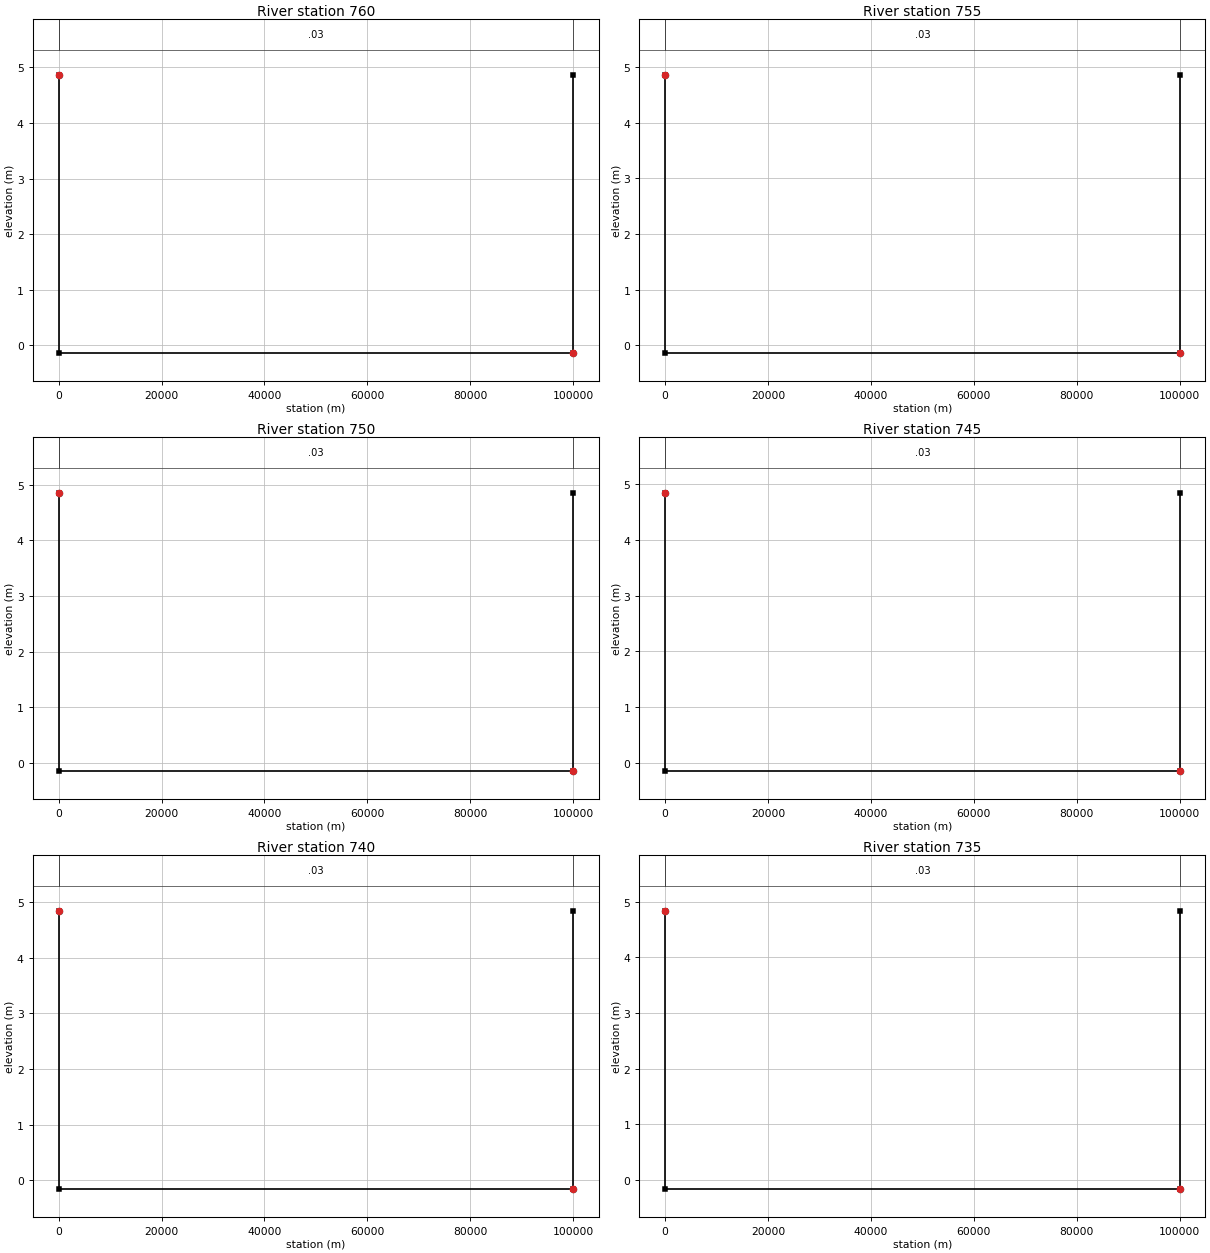
Type RM Length L Ch R = 1 ,760     ,5,5,5
#Sta/Elev= 4
 0.00000 4.86267 0.00000-0.13733  100000-0.13733  100000 4.86267
#Mann= 3 ,0,0
 0.00000 0.03000 0.00000 0.00000 0.03000 0.00000  100000 0.03000 0.00000
Bank Sta=0,100000
XS Rating Curve= 0 ,0
Exp/Cntr=0,0

Type RM Length L Ch R = 1 ,755     ,5,5,5
#Sta/Elev= 4
 0.00000 4.85713 0.00000-0.14287  100000-0.14287  100000 4.85713
#Mann= 3 ,0,0
 0.00000 0.03000 0.00000 0.00000 0.03000 0.00000  100000 0.03000 0.00000
Bank Sta=0,100000
XS Rating Curve= 0 ,0
Exp/Cntr=0,0

Type RM Length L Ch R = 1 ,750     ,5,5,5
#Sta/Elev= 4
 0.00000 4.85148 0.00000-0.14852  100000-0.14852  100000 4.85148
#Mann= 3 ,0,0
 0.00000 0.03000 0.00000 0.00000 0.03000 0.00000  100000 0.03000 0.00000
Bank Sta=0,100000
XS Rating Curve= 0 ,0
Exp/Cntr=0,0

Type RM Length L Ch R = 1 ,745     ,5,5,5
#Sta/Elev= 4
 0.00000 4.84573 0.00000-0.15427  100000-0.15427  100000 4.84573
#Mann= 3 ,0,0
 0.00000 0.03000 0.00000 0.00000 0.03000 0.00000  100000 0.03000 0.00000
Bank Sta=0,100000
XS Rating Curve= 0 ,0
Exp/Cntr=0,0

Type RM Length L Ch R = 1 ,740     ,5,5,5
#Sta/Elev= 4
 0.00000 4.83988 0.00000-0.16012  100000-0.16012  100000 4.83988
#Mann= 3 ,0,0
 0.00000 0.03000 0.00000 0.00000 0.03000 0.00000  100000 0.03000 0.00000
Bank Sta=0,100000
XS Rating Curve= 0 ,0
Exp/Cntr=0,0

Type RM Length L Ch R = 1 ,735     ,5,5,5
#Sta/Elev= 4
 0.00000 4.83393 0.00000-0.16607  100000-0.16607  100000 4.83393
#Mann= 3 ,0,0
 0.00000 0.03000 0.00000 0.00000 0.03000 0.00000  100000 0.03000 0.00000
Bank Sta=0,100000
XS Rating Curve= 0 ,0
Exp/Cntr=0,0