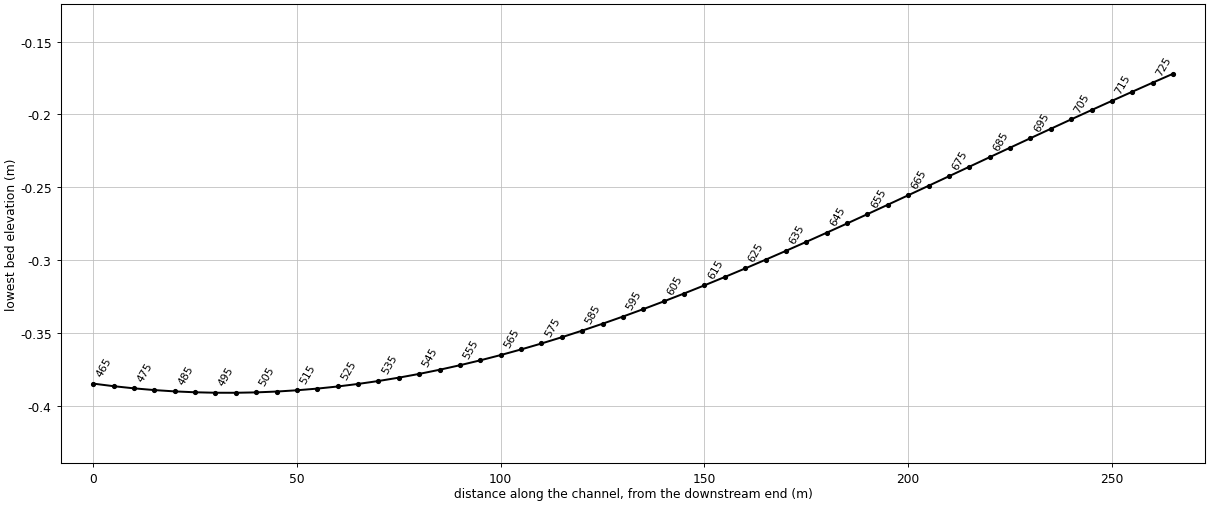
HEC-RAS study macdonald.prj: A1F-001 MacDonald backwater dx=5 m

--- macdonald.g01 (geometry) --- (continued)

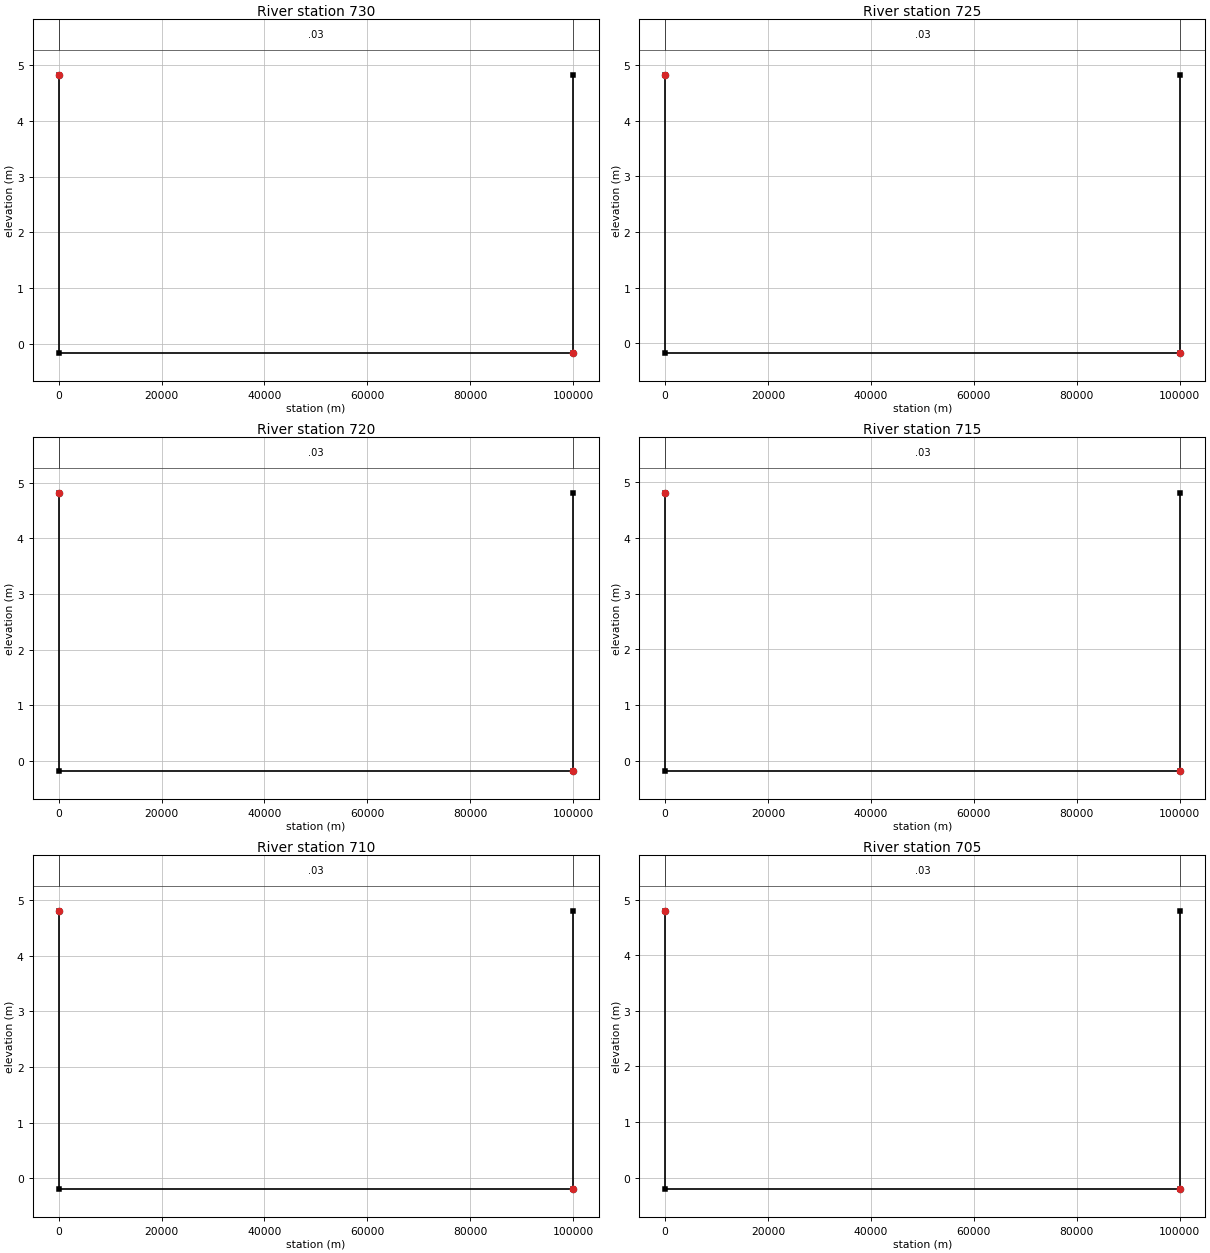
Type RM Length L Ch R = 1 ,730     ,5,5,5
#Sta/Elev= 4
 0.00000  4.8279 0.00000-0.17210  100000-0.17210  100000  4.8279
#Mann= 3 ,0,0
 0.00000 0.03000 0.00000 0.00000 0.03000 0.00000  100000 0.03000 0.00000
Bank Sta=0,100000
XS Rating Curve= 0 ,0
Exp/Cntr=0,0

Type RM Length L Ch R = 1 ,725     ,5,5,5
#Sta/Elev= 4
 0.00000 4.82179 0.00000-0.17821  100000-0.17821  100000 4.82179
#Mann= 3 ,0,0
 0.00000 0.03000 0.00000 0.00000 0.03000 0.00000  100000 0.03000 0.00000
Bank Sta=0,100000
XS Rating Curve= 0 ,0
Exp/Cntr=0,0

Type RM Length L Ch R = 1 ,720     ,5,5,5
#Sta/Elev= 4
 0.00000 4.81559 0.00000-0.18441  100000-0.18441  100000 4.81559
#Mann= 3 ,0,0
 0.00000 0.03000 0.00000 0.00000 0.03000 0.00000  100000 0.03000 0.00000
Bank Sta=0,100000
XS Rating Curve= 0 ,0
Exp/Cntr=0,0

Type RM Length L Ch R = 1 ,715     ,5,5,5
#Sta/Elev= 4
 0.00000 4.80933 0.00000-0.19067  100000-0.19067  100000 4.80933
#Mann= 3 ,0,0
 0.00000 0.03000 0.00000 0.00000 0.03000 0.00000  100000 0.03000 0.00000
Bank Sta=0,100000
XS Rating Curve= 0 ,0
Exp/Cntr=0,0

Type RM Length L Ch R = 1 ,710     ,5,5,5
#Sta/Elev= 4
 0.00000 4.80301 0.00000-0.19699  100000-0.19699  100000 4.80301
#Mann= 3 ,0,0
 0.00000 0.03000 0.00000 0.00000 0.03000 0.00000  100000 0.03000 0.00000
Bank Sta=0,100000
XS Rating Curve= 0 ,0
Exp/Cntr=0,0

Type RM Length L Ch R = 1 ,705     ,5,5,5
#Sta/Elev= 4
 0.00000 4.79663 0.00000-0.20337  100000-0.20337  100000 4.79663
#Mann= 3 ,0,0
 0.00000 0.03000 0.00000 0.00000 0.03000 0.00000  100000 0.03000 0.00000
Bank Sta=0,100000
XS Rating Curve= 0 ,0
Exp/Cntr=0,0

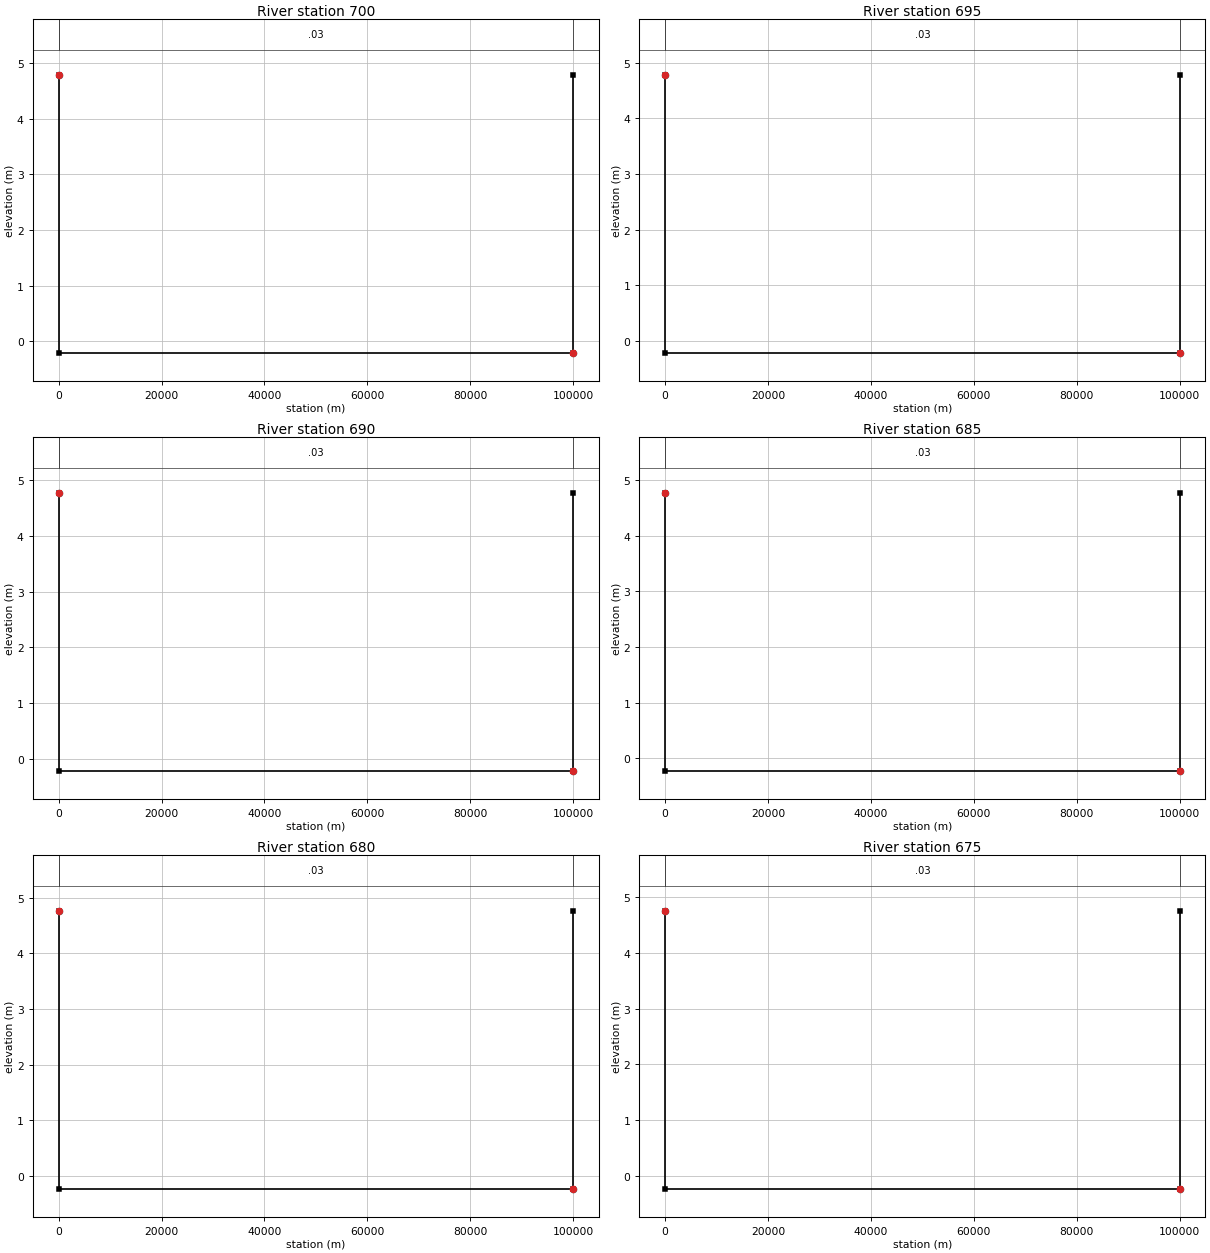
Type RM Length L Ch R = 1 ,700     ,5,5,5
#Sta/Elev= 4
 0.00000  4.7902 0.00000-0.20980  100000-0.20980  100000  4.7902
#Mann= 3 ,0,0
 0.00000 0.03000 0.00000 0.00000 0.03000 0.00000  100000 0.03000 0.00000
Bank Sta=0,100000
XS Rating Curve= 0 ,0
Exp/Cntr=0,0

Type RM Length L Ch R = 1 ,695     ,5,5,5
#Sta/Elev= 4
 0.00000 4.78373 0.00000-0.21627  100000-0.21627  100000 4.78373
#Mann= 3 ,0,0
 0.00000 0.03000 0.00000 0.00000 0.03000 0.00000  100000 0.03000 0.00000
Bank Sta=0,100000
XS Rating Curve= 0 ,0
Exp/Cntr=0,0

Type RM Length L Ch R = 1 ,690     ,5,5,5
#Sta/Elev= 4
 0.00000 4.77723 0.00000-0.22277  100000-0.22277  100000 4.77723
#Mann= 3 ,0,0
 0.00000 0.03000 0.00000 0.00000 0.03000 0.00000  100000 0.03000 0.00000
Bank Sta=0,100000
XS Rating Curve= 0 ,0
Exp/Cntr=0,0

Type RM Length L Ch R = 1 ,685     ,5,5,5
#Sta/Elev= 4
 0.00000 4.77072 0.00000-0.22928  100000-0.22928  100000 4.77072
#Mann= 3 ,0,0
 0.00000 0.03000 0.00000 0.00000 0.03000 0.00000  100000 0.03000 0.00000
Bank Sta=0,100000
XS Rating Curve= 0 ,0
Exp/Cntr=0,0

Type RM Length L Ch R = 1 ,680     ,5,5,5
#Sta/Elev= 4
 0.00000 4.76418 0.00000-0.23582  100000-0.23582  100000 4.76418
#Mann= 3 ,0,0
 0.00000 0.03000 0.00000 0.00000 0.03000 0.00000  100000 0.03000 0.00000
Bank Sta=0,100000
XS Rating Curve= 0 ,0
Exp/Cntr=0,0

Type RM Length L Ch R = 1 ,675     ,5,5,5
#Sta/Elev= 4
 0.00000 4.75765 0.00000-0.24235  100000-0.24235  100000 4.75765
#Mann= 3 ,0,0
 0.00000 0.03000 0.00000 0.00000 0.03000 0.00000  100000 0.03000 0.00000
Bank Sta=0,100000
XS Rating Curve= 0 ,0
Exp/Cntr=0,0

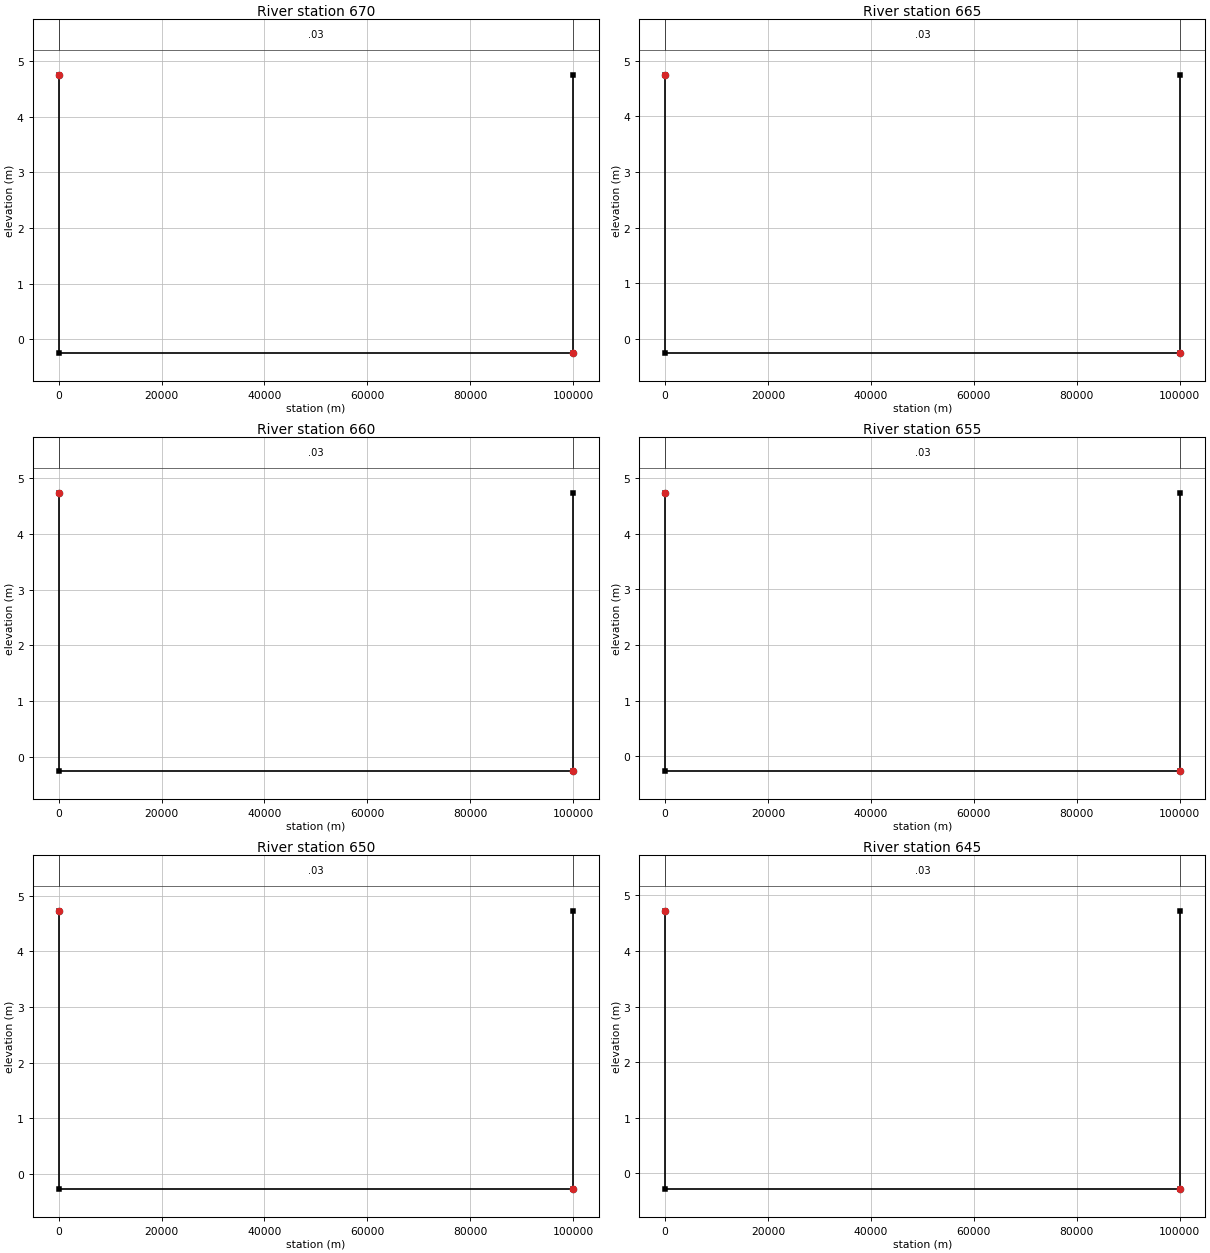
Type RM Length L Ch R = 1 ,670     ,5,5,5
#Sta/Elev= 4
 0.00000 4.75112 0.00000-0.24888  100000-0.24888  100000 4.75112
#Mann= 3 ,0,0
 0.00000 0.03000 0.00000 0.00000 0.03000 0.00000  100000 0.03000 0.00000
Bank Sta=0,100000
XS Rating Curve= 0 ,0
Exp/Cntr=0,0

Type RM Length L Ch R = 1 ,665     ,5,5,5
#Sta/Elev= 4
 0.00000 4.74462 0.00000-0.25538  100000-0.25538  100000 4.74462
#Mann= 3 ,0,0
 0.00000 0.03000 0.00000 0.00000 0.03000 0.00000  100000 0.03000 0.00000
Bank Sta=0,100000
XS Rating Curve= 0 ,0
Exp/Cntr=0,0

Type RM Length L Ch R = 1 ,660     ,5,5,5
#Sta/Elev= 4
 0.00000 4.73814 0.00000-0.26186  100000-0.26186  100000 4.73814
#Mann= 3 ,0,0
 0.00000 0.03000 0.00000 0.00000 0.03000 0.00000  100000 0.03000 0.00000
Bank Sta=0,100000
XS Rating Curve= 0 ,0
Exp/Cntr=0,0

Type RM Length L Ch R = 1 ,655     ,5,5,5
#Sta/Elev= 4
 0.00000 4.73169 0.00000-0.26831  100000-0.26831  100000 4.73169
#Mann= 3 ,0,0
 0.00000 0.03000 0.00000 0.00000 0.03000 0.00000  100000 0.03000 0.00000
Bank Sta=0,100000
XS Rating Curve= 0 ,0
Exp/Cntr=0,0

Type RM Length L Ch R = 1 ,650     ,5,5,5
#Sta/Elev= 4
 0.00000  4.7253 0.00000-0.27470  100000-0.27470  100000  4.7253
#Mann= 3 ,0,0
 0.00000 0.03000 0.00000 0.00000 0.03000 0.00000  100000 0.03000 0.00000
Bank Sta=0,100000
XS Rating Curve= 0 ,0
Exp/Cntr=0,0

Type RM Length L Ch R = 1 ,645     ,5,5,5
#Sta/Elev= 4
 0.00000 4.71897 0.00000-0.28103  100000-0.28103  100000 4.71897
#Mann= 3 ,0,0
 0.00000 0.03000 0.00000 0.00000 0.03000 0.00000  100000 0.03000 0.00000
Bank Sta=0,100000
XS Rating Curve= 0 ,0
Exp/Cntr=0,0

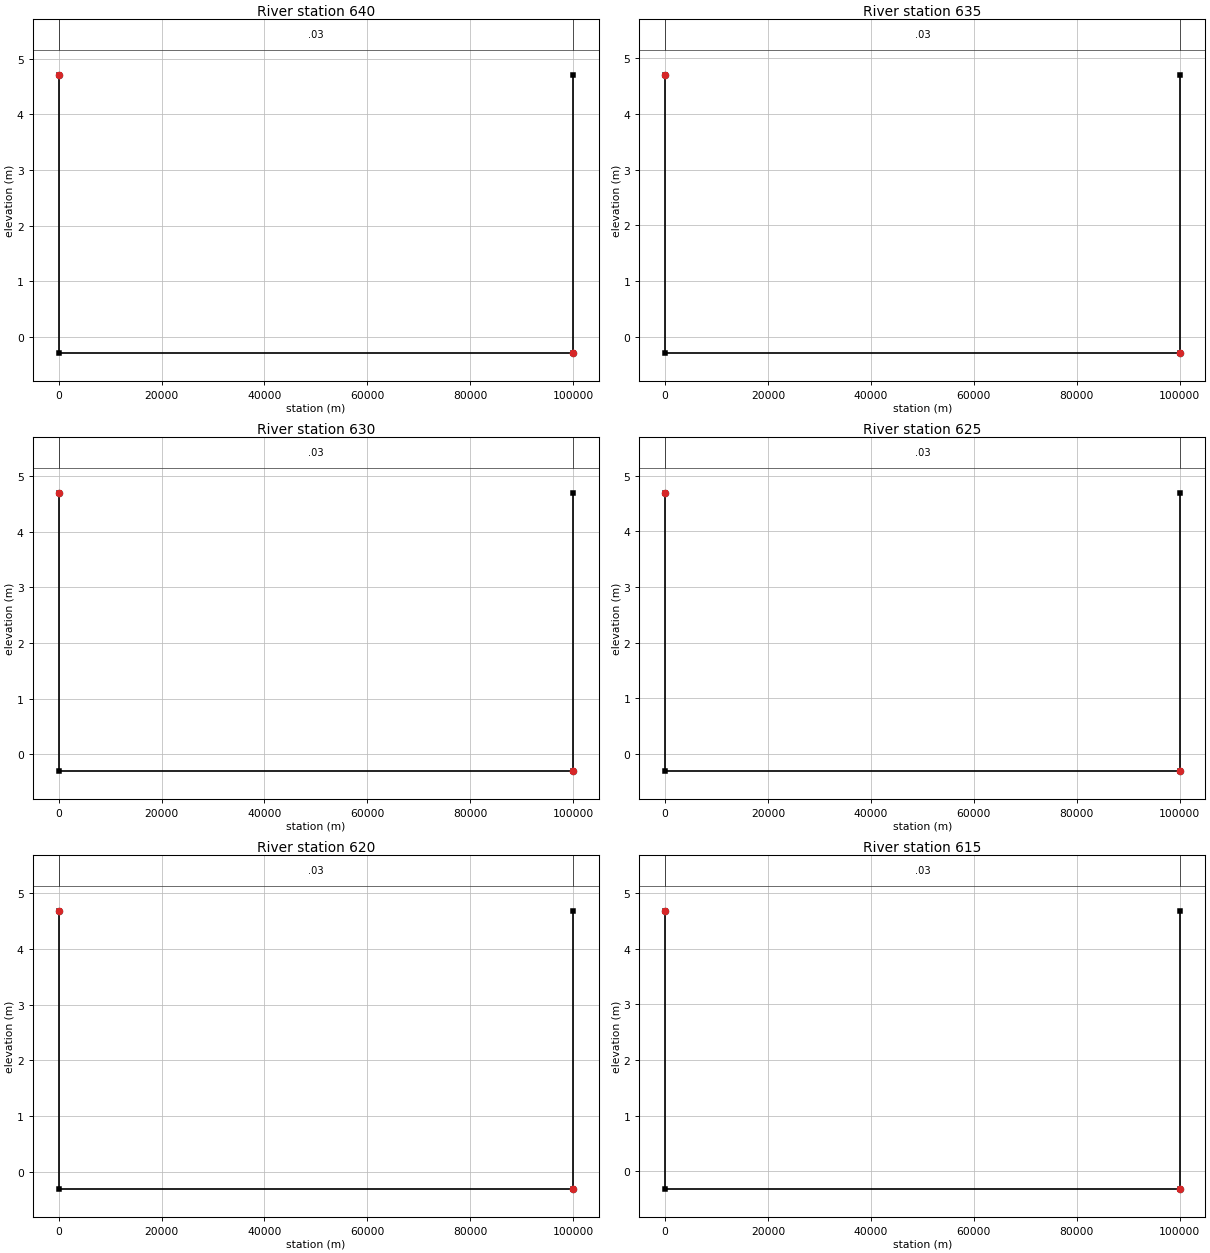
Type RM Length L Ch R = 1 ,640     ,5,5,5
#Sta/Elev= 4
 0.00000 4.71271 0.00000-0.28729  100000-0.28729  100000 4.71271
#Mann= 3 ,0,0
 0.00000 0.03000 0.00000 0.00000 0.03000 0.00000  100000 0.03000 0.00000
Bank Sta=0,100000
XS Rating Curve= 0 ,0
Exp/Cntr=0,0

Type RM Length L Ch R = 1 ,635     ,5,5,5
#Sta/Elev= 4
 0.00000 4.70654 0.00000-0.29346  100000-0.29346  100000 4.70654
#Mann= 3 ,0,0
 0.00000 0.03000 0.00000 0.00000 0.03000 0.00000  100000 0.03000 0.00000
Bank Sta=0,100000
XS Rating Curve= 0 ,0
Exp/Cntr=0,0

Type RM Length L Ch R = 1 ,630     ,5,5,5
#Sta/Elev= 4
 0.00000 4.70046 0.00000-0.29954  100000-0.29954  100000 4.70046
#Mann= 3 ,0,0
 0.00000 0.03000 0.00000 0.00000 0.03000 0.00000  100000 0.03000 0.00000
Bank Sta=0,100000
XS Rating Curve= 0 ,0
Exp/Cntr=0,0

Type RM Length L Ch R = 1 ,625     ,5,5,5
#Sta/Elev= 4
 0.00000 4.69449 0.00000-0.30551  100000-0.30551  100000 4.69449
#Mann= 3 ,0,0
 0.00000 0.03000 0.00000 0.00000 0.03000 0.00000  100000 0.03000 0.00000
Bank Sta=0,100000
XS Rating Curve= 0 ,0
Exp/Cntr=0,0

Type RM Length L Ch R = 1 ,620     ,5,5,5
#Sta/Elev= 4
 0.00000 4.68863 0.00000-0.31137  100000-0.31137  100000 4.68863
#Mann= 3 ,0,0
 0.00000 0.03000 0.00000 0.00000 0.03000 0.00000  100000 0.03000 0.00000
Bank Sta=0,100000
XS Rating Curve= 0 ,0
Exp/Cntr=0,0

Type RM Length L Ch R = 1 ,615     ,5,5,5
#Sta/Elev= 4
 0.00000  4.6829 0.00000-0.31710  100000-0.31710  100000  4.6829
#Mann= 3 ,0,0
 0.00000 0.03000 0.00000 0.00000 0.03000 0.00000  100000 0.03000 0.00000
Bank Sta=0,100000
XS Rating Curve= 0 ,0
Exp/Cntr=0,0

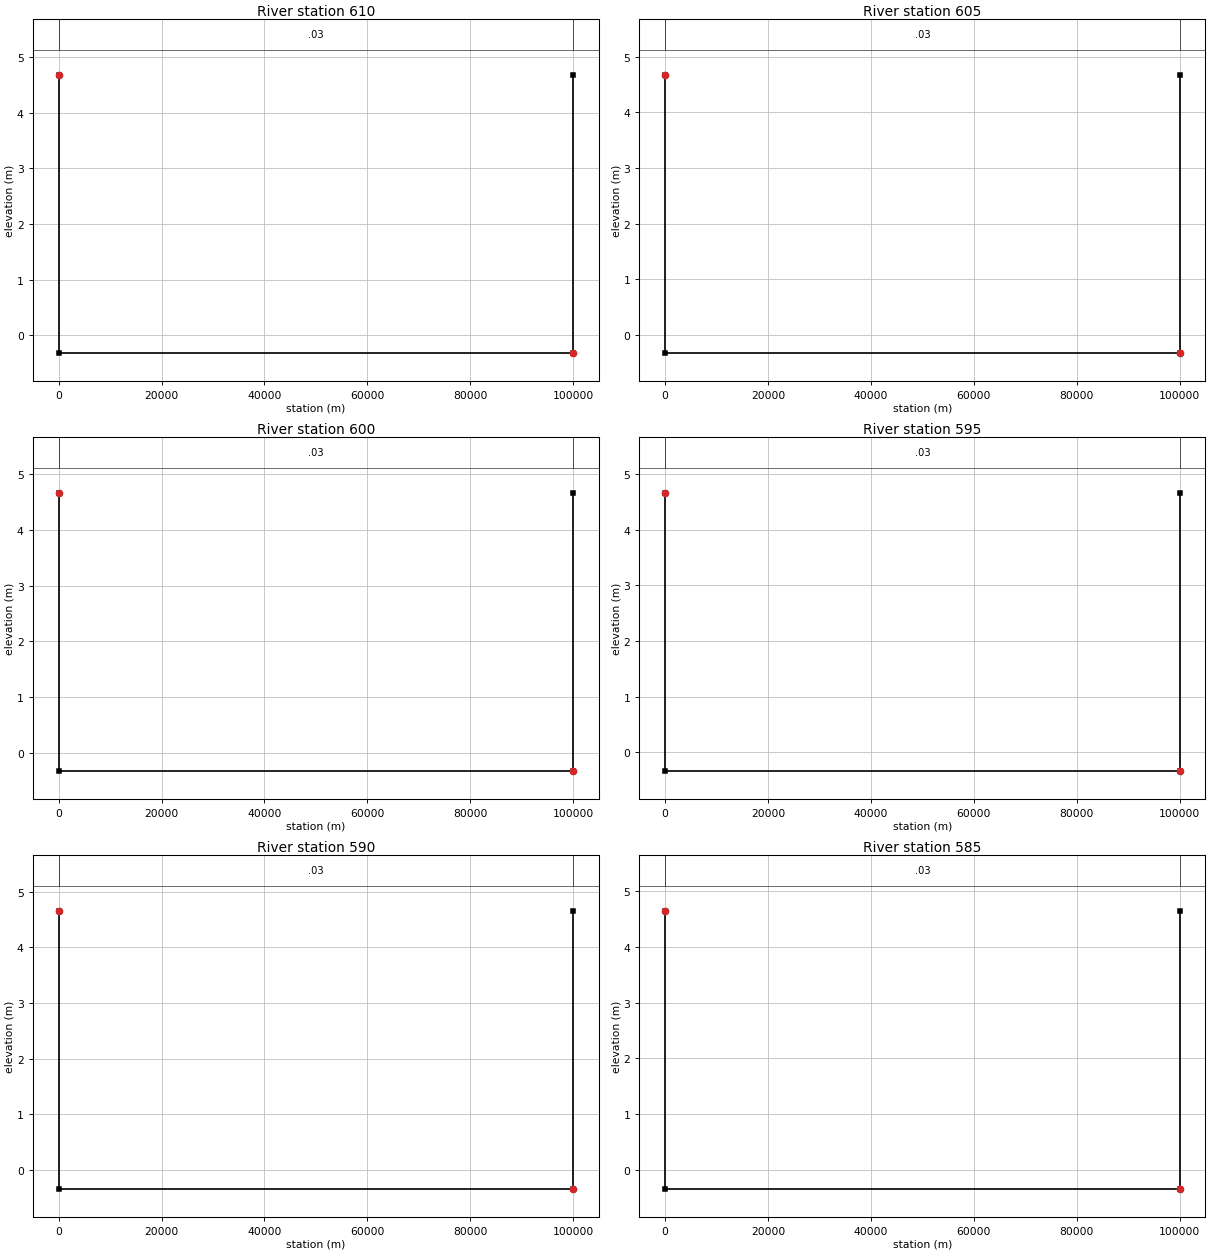
Type RM Length L Ch R = 1 ,610     ,5,5,5
#Sta/Elev= 4
 0.00000 4.67732 0.00000-0.32268  100000-0.32268  100000 4.67732
#Mann= 3 ,0,0
 0.00000 0.03000 0.00000 0.00000 0.03000 0.00000  100000 0.03000 0.00000
Bank Sta=0,100000
XS Rating Curve= 0 ,0
Exp/Cntr=0,0

Type RM Length L Ch R = 1 ,605     ,5,5,5
#Sta/Elev= 4
 0.00000 4.67188 0.00000-0.32812  100000-0.32812  100000 4.67188
#Mann= 3 ,0,0
 0.00000 0.03000 0.00000 0.00000 0.03000 0.00000  100000 0.03000 0.00000
Bank Sta=0,100000
XS Rating Curve= 0 ,0
Exp/Cntr=0,0

Type RM Length L Ch R = 1 ,600     ,5,5,5
#Sta/Elev= 4
 0.00000 4.66661 0.00000-0.33339  100000-0.33339  100000 4.66661
#Mann= 3 ,0,0
 0.00000 0.03000 0.00000 0.00000 0.03000 0.00000  100000 0.03000 0.00000
Bank Sta=0,100000
XS Rating Curve= 0 ,0
Exp/Cntr=0,0

Type RM Length L Ch R = 1 ,595     ,5,5,5
#Sta/Elev= 4
 0.00000 4.66151 0.00000-0.33849  100000-0.33849  100000 4.66151
#Mann= 3 ,0,0
 0.00000 0.03000 0.00000 0.00000 0.03000 0.00000  100000 0.03000 0.00000
Bank Sta=0,100000
XS Rating Curve= 0 ,0
Exp/Cntr=0,0

Type RM Length L Ch R = 1 ,590     ,5,5,5
#Sta/Elev= 4
 0.00000  4.6566 0.00000-0.34340  100000-0.34340  100000  4.6566
#Mann= 3 ,0,0
 0.00000 0.03000 0.00000 0.00000 0.03000 0.00000  100000 0.03000 0.00000
Bank Sta=0,100000
XS Rating Curve= 0 ,0
Exp/Cntr=0,0

Type RM Length L Ch R = 1 ,585     ,5,5,5
#Sta/Elev= 4
 0.00000 4.65188 0.00000-0.34812  100000-0.34812  100000 4.65188
#Mann= 3 ,0,0
 0.00000 0.03000 0.00000 0.00000 0.03000 0.00000  100000 0.03000 0.00000
Bank Sta=0,100000
XS Rating Curve= 0 ,0
Exp/Cntr=0,0

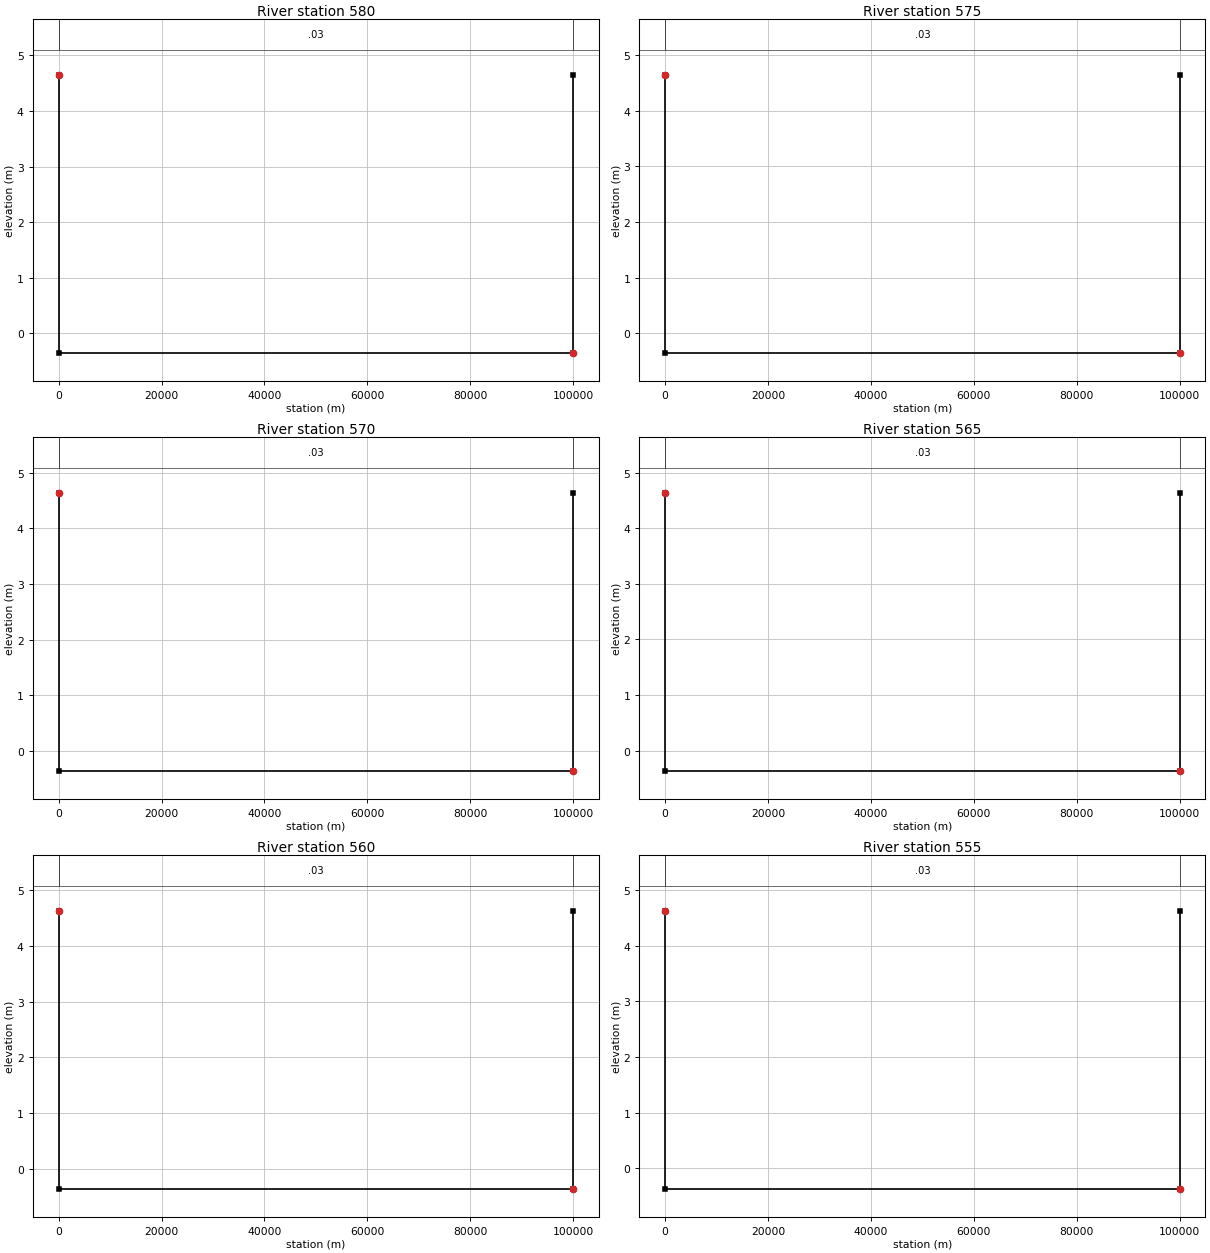
Type RM Length L Ch R = 1 ,580     ,5,5,5
#Sta/Elev= 4
 0.00000 4.64736 0.00000-0.35264  100000-0.35264  100000 4.64736
#Mann= 3 ,0,0
 0.00000 0.03000 0.00000 0.00000 0.03000 0.00000  100000 0.03000 0.00000
Bank Sta=0,100000
XS Rating Curve= 0 ,0
Exp/Cntr=0,0

Type RM Length L Ch R = 1 ,575     ,5,5,5
#Sta/Elev= 4
 0.00000 4.64306 0.00000-0.35694  100000-0.35694  100000 4.64306
#Mann= 3 ,0,0
 0.00000 0.03000 0.00000 0.00000 0.03000 0.00000  100000 0.03000 0.00000
Bank Sta=0,100000
XS Rating Curve= 0 ,0
Exp/Cntr=0,0

Type RM Length L Ch R = 1 ,570     ,5,5,5
#Sta/Elev= 4
 0.00000 4.63898 0.00000-0.36102  100000-0.36102  100000 4.63898
#Mann= 3 ,0,0
 0.00000 0.03000 0.00000 0.00000 0.03000 0.00000  100000 0.03000 0.00000
Bank Sta=0,100000
XS Rating Curve= 0 ,0
Exp/Cntr=0,0

Type RM Length L Ch R = 1 ,565     ,5,5,5
#Sta/Elev= 4
 0.00000 4.63513 0.00000-0.36487  100000-0.36487  100000 4.63513
#Mann= 3 ,0,0
 0.00000 0.03000 0.00000 0.00000 0.03000 0.00000  100000 0.03000 0.00000
Bank Sta=0,100000
XS Rating Curve= 0 ,0
Exp/Cntr=0,0

Type RM Length L Ch R = 1 ,560     ,5,5,5
#Sta/Elev= 4
 0.00000 4.63153 0.00000-0.36847  100000-0.36847  100000 4.63153
#Mann= 3 ,0,0
 0.00000 0.03000 0.00000 0.00000 0.03000 0.00000  100000 0.03000 0.00000
Bank Sta=0,100000
XS Rating Curve= 0 ,0
Exp/Cntr=0,0

Type RM Length L Ch R = 1 ,555     ,5,5,5
#Sta/Elev= 4
 0.00000 4.62817 0.00000-0.37183  100000-0.37183  100000 4.62817
#Mann= 3 ,0,0
 0.00000 0.03000 0.00000 0.00000 0.03000 0.00000  100000 0.03000 0.00000
Bank Sta=0,100000
XS Rating Curve= 0 ,0
Exp/Cntr=0,0

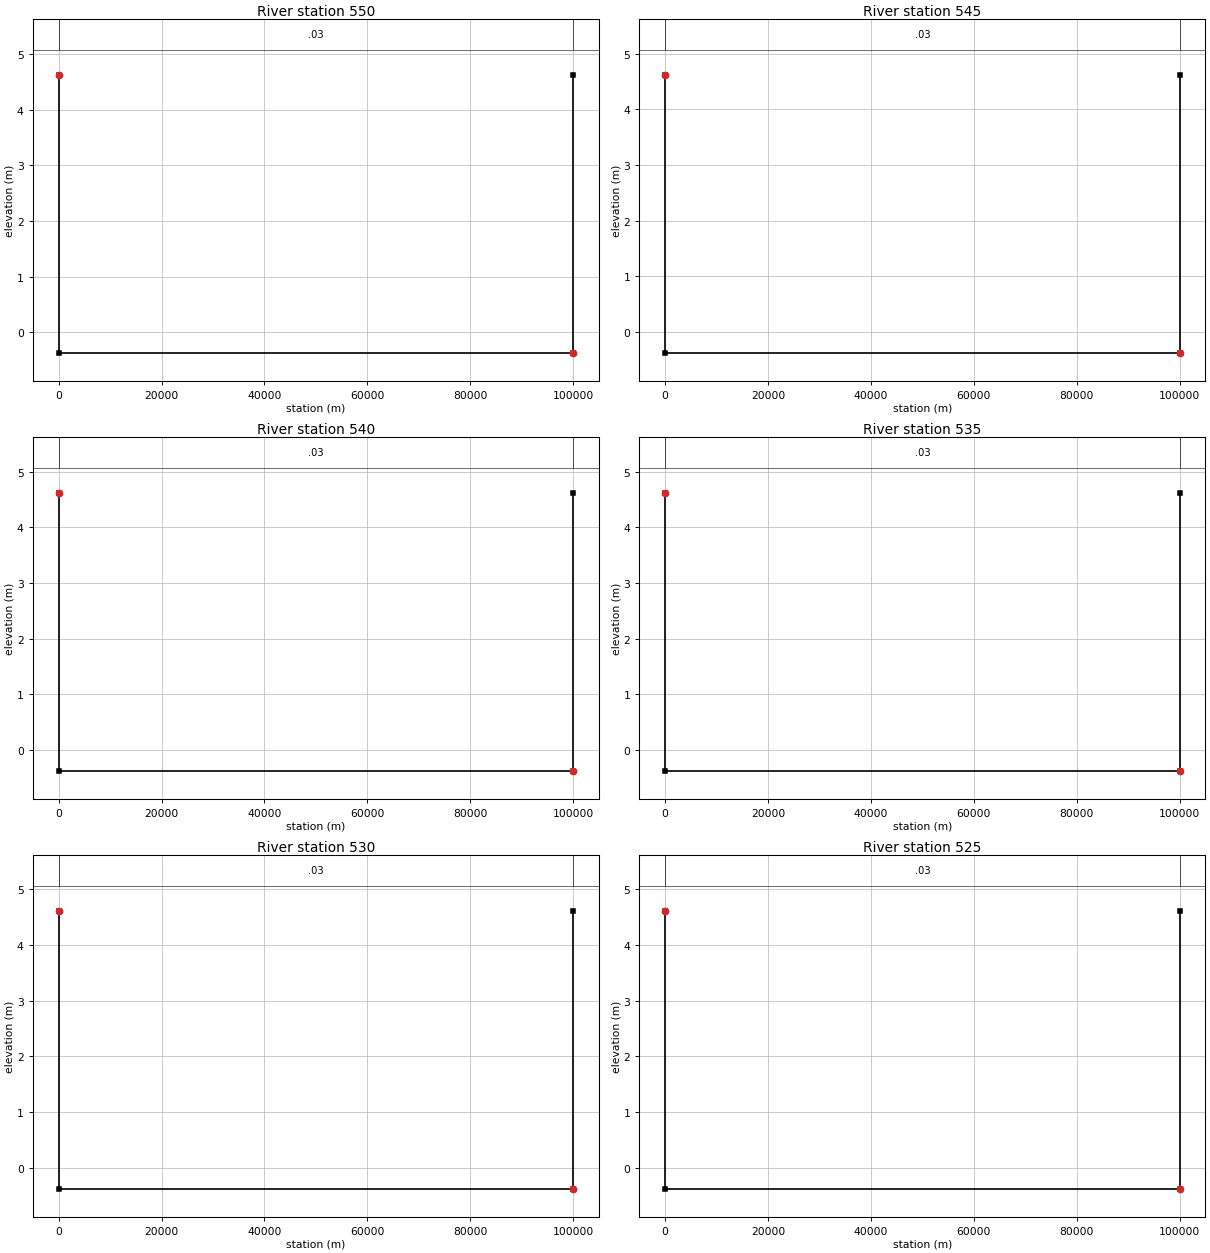
Type RM Length L Ch R = 1 ,550     ,5,5,5
#Sta/Elev= 4
 0.00000 4.62506 0.00000-0.37494  100000-0.37494  100000 4.62506
#Mann= 3 ,0,0
 0.00000 0.03000 0.00000 0.00000 0.03000 0.00000  100000 0.03000 0.00000
Bank Sta=0,100000
XS Rating Curve= 0 ,0
Exp/Cntr=0,0

Type RM Length L Ch R = 1 ,545     ,5,5,5
#Sta/Elev= 4
 0.00000 4.62222 0.00000-0.37778  100000-0.37778  100000 4.62222
#Mann= 3 ,0,0
 0.00000 0.03000 0.00000 0.00000 0.03000 0.00000  100000 0.03000 0.00000
Bank Sta=0,100000
XS Rating Curve= 0 ,0
Exp/Cntr=0,0

Type RM Length L Ch R = 1 ,540     ,5,5,5
#Sta/Elev= 4
 0.00000 4.61965 0.00000-0.38035  100000-0.38035  100000 4.61965
#Mann= 3 ,0,0
 0.00000 0.03000 0.00000 0.00000 0.03000 0.00000  100000 0.03000 0.00000
Bank Sta=0,100000
XS Rating Curve= 0 ,0
Exp/Cntr=0,0

Type RM Length L Ch R = 1 ,535     ,5,5,5
#Sta/Elev= 4
 0.00000 4.61735 0.00000-0.38265  100000-0.38265  100000 4.61735
#Mann= 3 ,0,0
 0.00000 0.03000 0.00000 0.00000 0.03000 0.00000  100000 0.03000 0.00000
Bank Sta=0,100000
XS Rating Curve= 0 ,0
Exp/Cntr=0,0

Type RM Length L Ch R = 1 ,530     ,5,5,5
#Sta/Elev= 4
 0.00000 4.61534 0.00000-0.38466  100000-0.38466  100000 4.61534
#Mann= 3 ,0,0
 0.00000 0.03000 0.00000 0.00000 0.03000 0.00000  100000 0.03000 0.00000
Bank Sta=0,100000
XS Rating Curve= 0 ,0
Exp/Cntr=0,0

Type RM Length L Ch R = 1 ,525     ,5,5,5
#Sta/Elev= 4
 0.00000  4.6136 0.00000-0.38640  100000-0.38640  100000  4.6136
#Mann= 3 ,0,0
 0.00000 0.03000 0.00000 0.00000 0.03000 0.00000  100000 0.03000 0.00000
Bank Sta=0,100000
XS Rating Curve= 0 ,0
Exp/Cntr=0,0

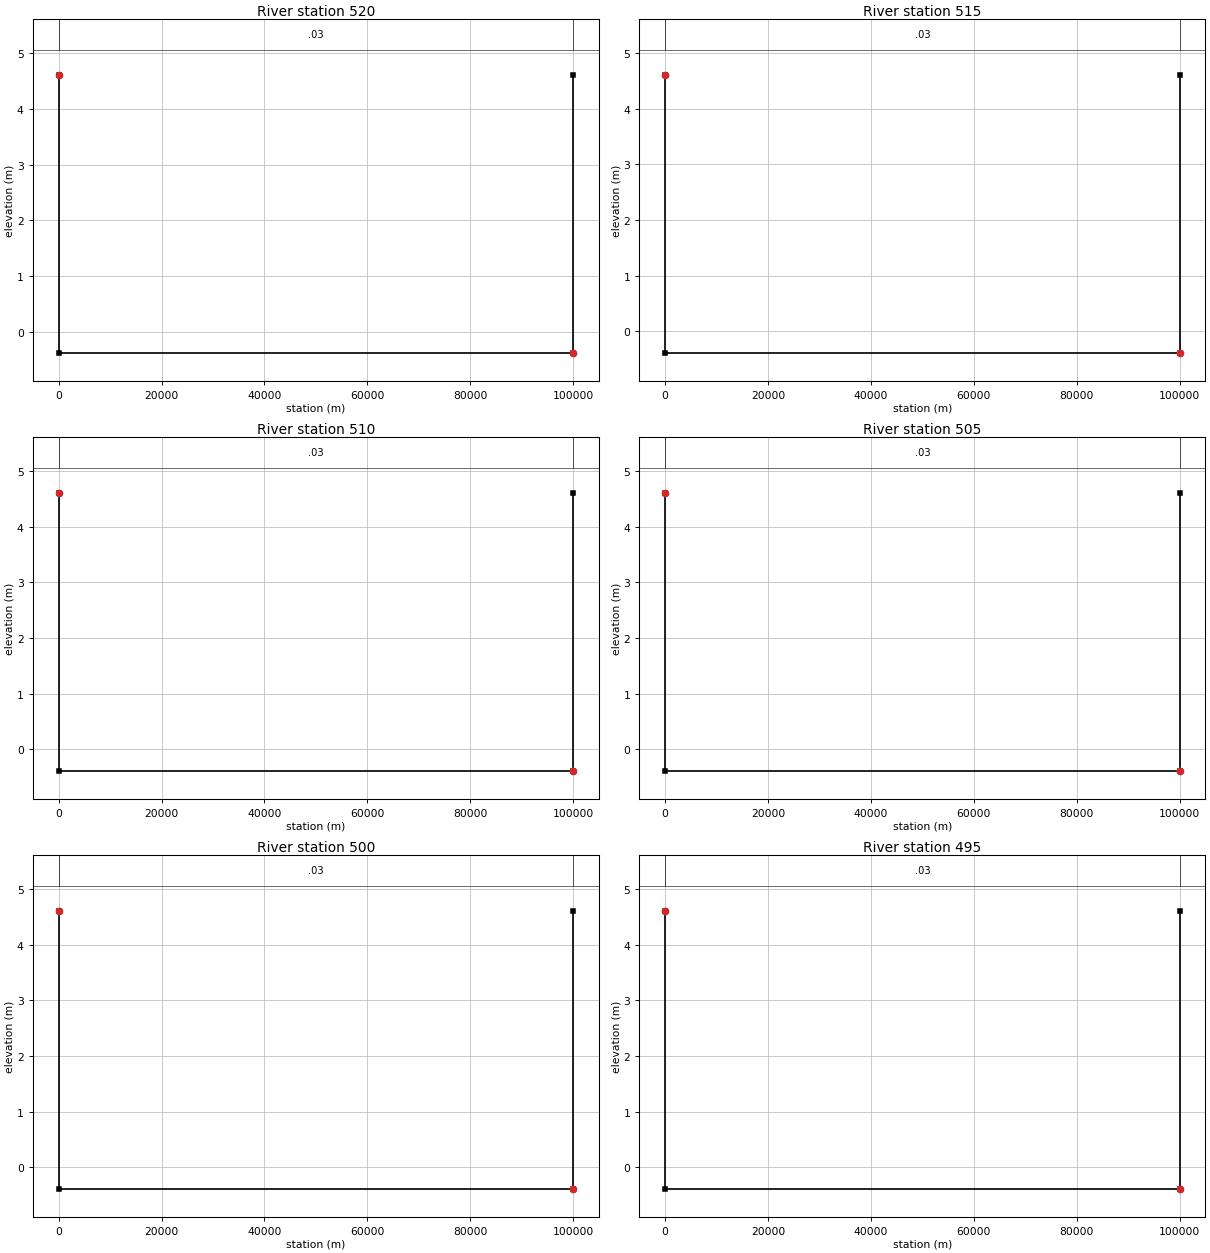
Type RM Length L Ch R = 1 ,520     ,5,5,5
#Sta/Elev= 4
 0.00000 4.61215 0.00000-0.38785  100000-0.38785  100000 4.61215
#Mann= 3 ,0,0
 0.00000 0.03000 0.00000 0.00000 0.03000 0.00000  100000 0.03000 0.00000
Bank Sta=0,100000
XS Rating Curve= 0 ,0
Exp/Cntr=0,0

Type RM Length L Ch R = 1 ,515     ,5,5,5
#Sta/Elev= 4
 0.00000   4.611 0.00000-0.38900  100000-0.38900  100000   4.611
#Mann= 3 ,0,0
 0.00000 0.03000 0.00000 0.00000 0.03000 0.00000  100000 0.03000 0.00000
Bank Sta=0,100000
XS Rating Curve= 0 ,0
Exp/Cntr=0,0

Type RM Length L Ch R = 1 ,510     ,5,5,5
#Sta/Elev= 4
 0.00000 4.61013 0.00000-0.38987  100000-0.38987  100000 4.61013
#Mann= 3 ,0,0
 0.00000 0.03000 0.00000 0.00000 0.03000 0.00000  100000 0.03000 0.00000
Bank Sta=0,100000
XS Rating Curve= 0 ,0
Exp/Cntr=0,0

Type RM Length L Ch R = 1 ,505     ,5,5,5
#Sta/Elev= 4
 0.00000 4.60956 0.00000-0.39044  100000-0.39044  100000 4.60956
#Mann= 3 ,0,0
 0.00000 0.03000 0.00000 0.00000 0.03000 0.00000  100000 0.03000 0.00000
Bank Sta=0,100000
XS Rating Curve= 0 ,0
Exp/Cntr=0,0

Type RM Length L Ch R = 1 ,500     ,5,5,5
#Sta/Elev= 4
 0.00000 4.60929 0.00000-0.39071  100000-0.39071  100000 4.60929
#Mann= 3 ,0,0
 0.00000 0.03000 0.00000 0.00000 0.03000 0.00000  100000 0.03000 0.00000
Bank Sta=0,100000
XS Rating Curve= 0 ,0
Exp/Cntr=0,0

Type RM Length L Ch R = 1 ,495     ,5,5,5
#Sta/Elev= 4
 0.00000 4.60931 0.00000-0.39069  100000-0.39069  100000 4.60931
#Mann= 3 ,0,0
 0.00000 0.03000 0.00000 0.00000 0.03000 0.00000  100000 0.03000 0.00000
Bank Sta=0,100000
XS Rating Curve= 0 ,0
Exp/Cntr=0,0

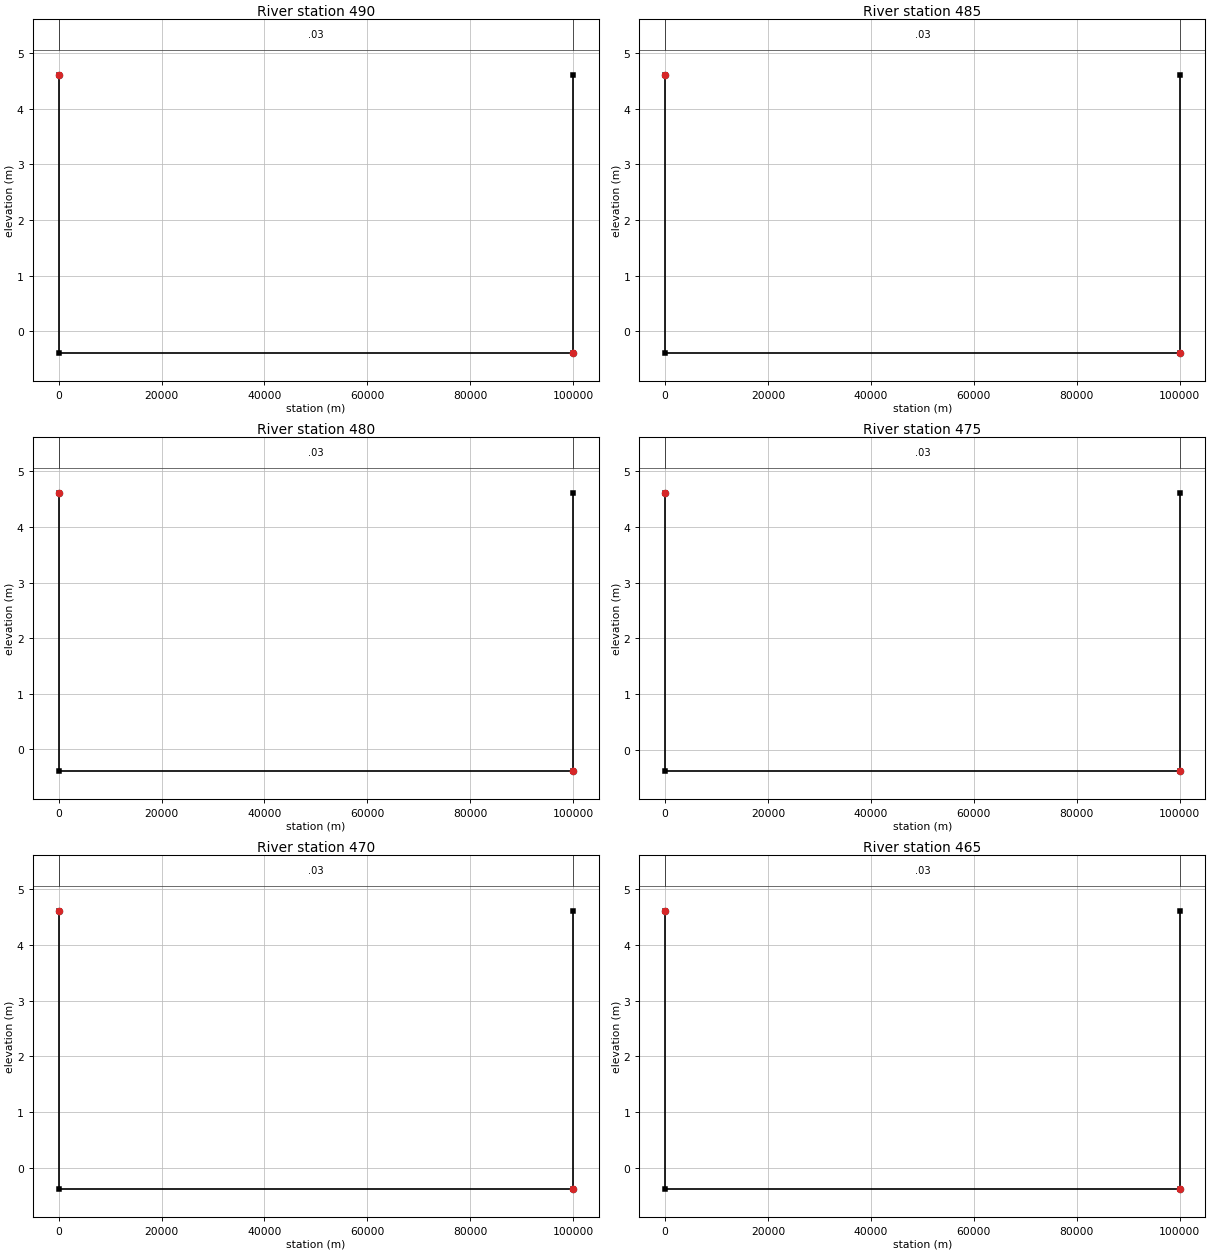
Type RM Length L Ch R = 1 ,490     ,5,5,5
#Sta/Elev= 4
 0.00000 4.60963 0.00000-0.39037  100000-0.39037  100000 4.60963
#Mann= 3 ,0,0
 0.00000 0.03000 0.00000 0.00000 0.03000 0.00000  100000 0.03000 0.00000
Bank Sta=0,100000
XS Rating Curve= 0 ,0
Exp/Cntr=0,0

Type RM Length L Ch R = 1 ,485     ,5,5,5
#Sta/Elev= 4
 0.00000 4.61024 0.00000-0.38976  100000-0.38976  100000 4.61024
#Mann= 3 ,0,0
 0.00000 0.03000 0.00000 0.00000 0.03000 0.00000  100000 0.03000 0.00000
Bank Sta=0,100000
XS Rating Curve= 0 ,0
Exp/Cntr=0,0

Type RM Length L Ch R = 1 ,480     ,5,5,5
#Sta/Elev= 4
 0.00000 4.61114 0.00000-0.38886  100000-0.38886  100000 4.61114
#Mann= 3 ,0,0
 0.00000 0.03000 0.00000 0.00000 0.03000 0.00000  100000 0.03000 0.00000
Bank Sta=0,100000
XS Rating Curve= 0 ,0
Exp/Cntr=0,0

Type RM Length L Ch R = 1 ,475     ,5,5,5
#Sta/Elev= 4
 0.00000 4.61233 0.00000-0.38767  100000-0.38767  100000 4.61233
#Mann= 3 ,0,0
 0.00000 0.03000 0.00000 0.00000 0.03000 0.00000  100000 0.03000 0.00000
Bank Sta=0,100000
XS Rating Curve= 0 ,0
Exp/Cntr=0,0

Type RM Length L Ch R = 1 ,470     ,5,5,5
#Sta/Elev= 4
 0.00000 4.61381 0.00000-0.38619  100000-0.38619  100000 4.61381
#Mann= 3 ,0,0
 0.00000 0.03000 0.00000 0.00000 0.03000 0.00000  100000 0.03000 0.00000
Bank Sta=0,100000
XS Rating Curve= 0 ,0
Exp/Cntr=0,0

Type RM Length L Ch R = 1 ,465     ,5,5,5
#Sta/Elev= 4
 0.00000 4.61557 0.00000-0.38443  100000-0.38443  100000 4.61557
#Mann= 3 ,0,0
 0.00000 0.03000 0.00000 0.00000 0.03000 0.00000  100000 0.03000 0.00000
Bank Sta=0,100000
XS Rating Curve= 0 ,0
Exp/Cntr=0,0