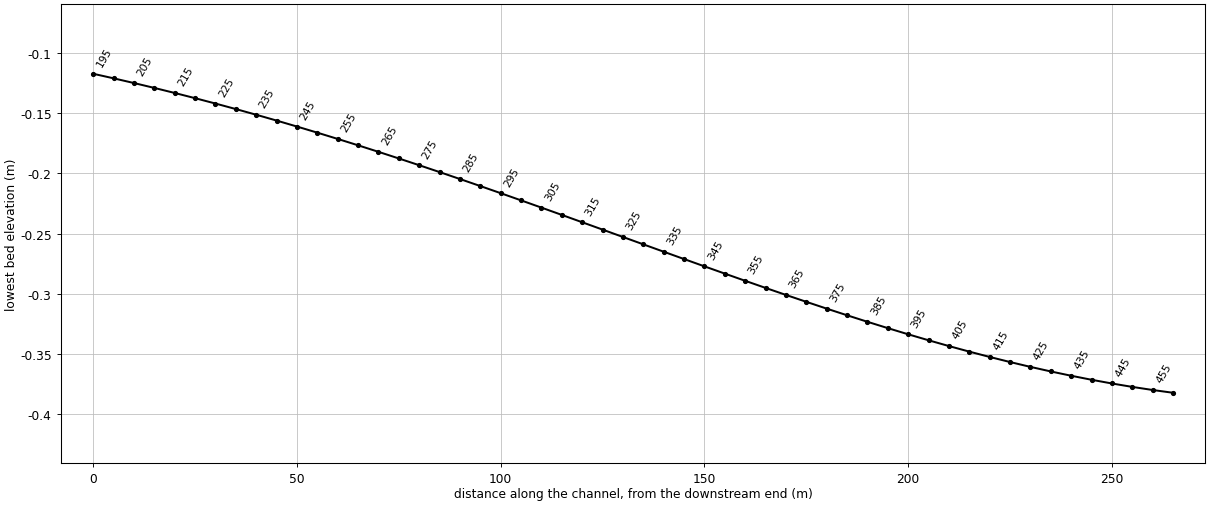
HEC-RAS study macdonald.prj: A1F-001 MacDonald backwater dx=5 m

--- macdonald.g01 (geometry) --- (continued)

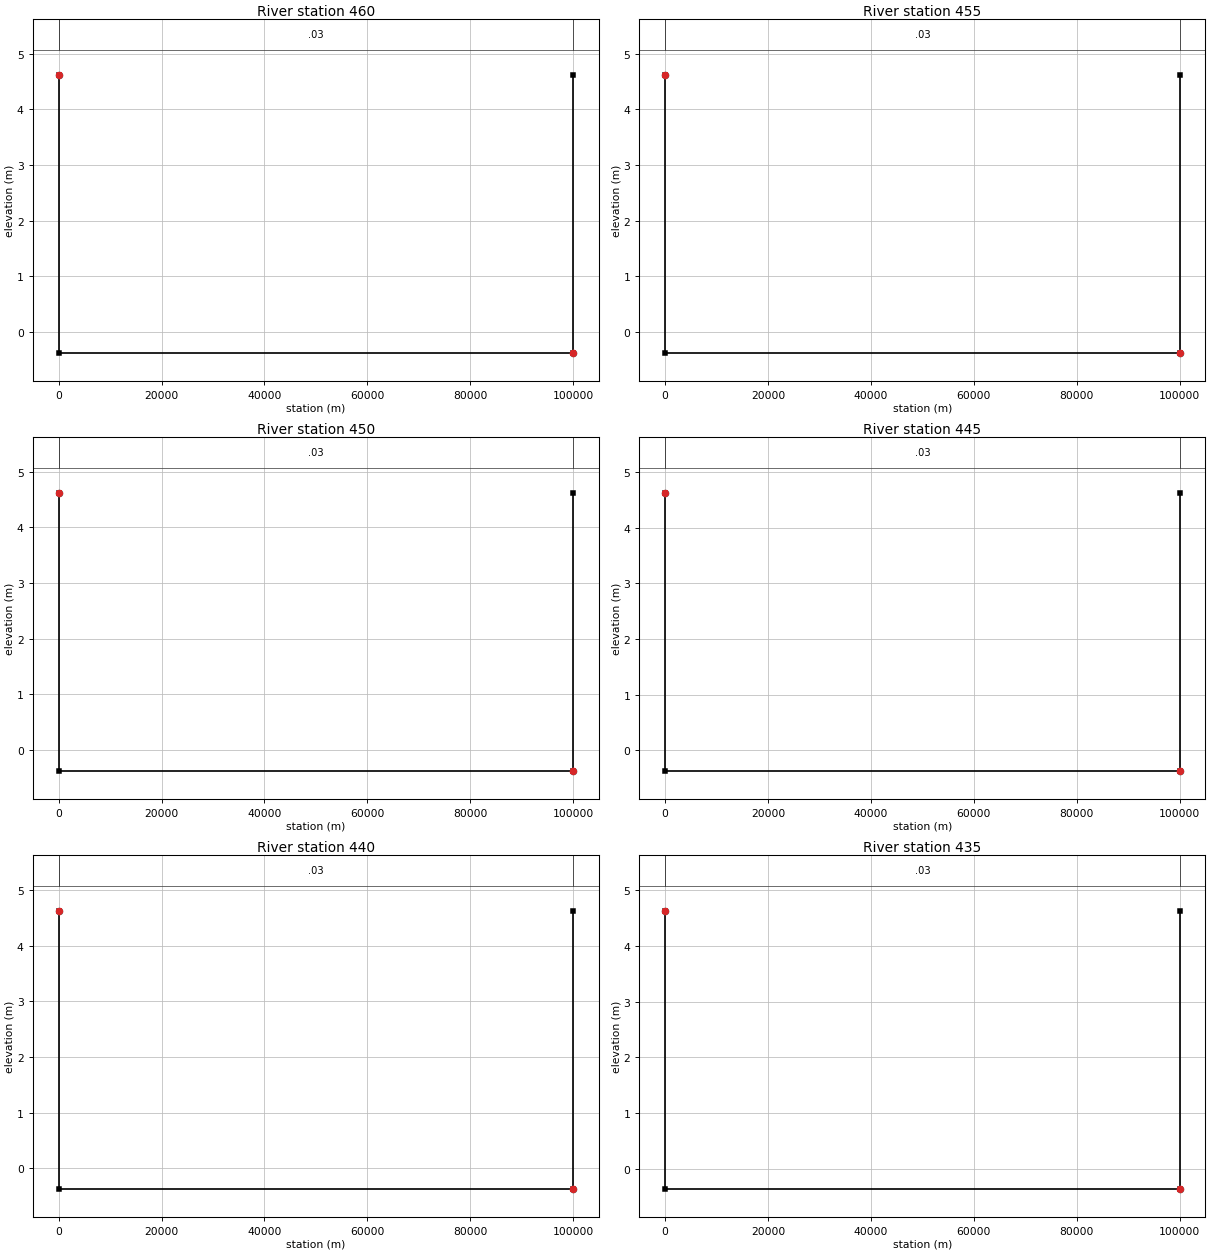
Type RM Length L Ch R = 1 ,460     ,5,5,5
#Sta/Elev= 4
 0.00000 4.61761 0.00000-0.38239  100000-0.38239  100000 4.61761
#Mann= 3 ,0,0
 0.00000 0.03000 0.00000 0.00000 0.03000 0.00000  100000 0.03000 0.00000
Bank Sta=0,100000
XS Rating Curve= 0 ,0
Exp/Cntr=0,0

Type RM Length L Ch R = 1 ,455     ,5,5,5
#Sta/Elev= 4
 0.00000 4.61992 0.00000-0.38008  100000-0.38008  100000 4.61992
#Mann= 3 ,0,0
 0.00000 0.03000 0.00000 0.00000 0.03000 0.00000  100000 0.03000 0.00000
Bank Sta=0,100000
XS Rating Curve= 0 ,0
Exp/Cntr=0,0

Type RM Length L Ch R = 1 ,450     ,5,5,5
#Sta/Elev= 4
 0.00000  4.6225 0.00000-0.37750  100000-0.37750  100000  4.6225
#Mann= 3 ,0,0
 0.00000 0.03000 0.00000 0.00000 0.03000 0.00000  100000 0.03000 0.00000
Bank Sta=0,100000
XS Rating Curve= 0 ,0
Exp/Cntr=0,0

Type RM Length L Ch R = 1 ,445     ,5,5,5
#Sta/Elev= 4
 0.00000 4.62534 0.00000-0.37466  100000-0.37466  100000 4.62534
#Mann= 3 ,0,0
 0.00000 0.03000 0.00000 0.00000 0.03000 0.00000  100000 0.03000 0.00000
Bank Sta=0,100000
XS Rating Curve= 0 ,0
Exp/Cntr=0,0

Type RM Length L Ch R = 1 ,440     ,5,5,5
#Sta/Elev= 4
 0.00000 4.62843 0.00000-0.37157  100000-0.37157  100000 4.62843
#Mann= 3 ,0,0
 0.00000 0.03000 0.00000 0.00000 0.03000 0.00000  100000 0.03000 0.00000
Bank Sta=0,100000
XS Rating Curve= 0 ,0
Exp/Cntr=0,0

Type RM Length L Ch R = 1 ,435     ,5,5,5
#Sta/Elev= 4
 0.00000 4.63177 0.00000-0.36823  100000-0.36823  100000 4.63177
#Mann= 3 ,0,0
 0.00000 0.03000 0.00000 0.00000 0.03000 0.00000  100000 0.03000 0.00000
Bank Sta=0,100000
XS Rating Curve= 0 ,0
Exp/Cntr=0,0

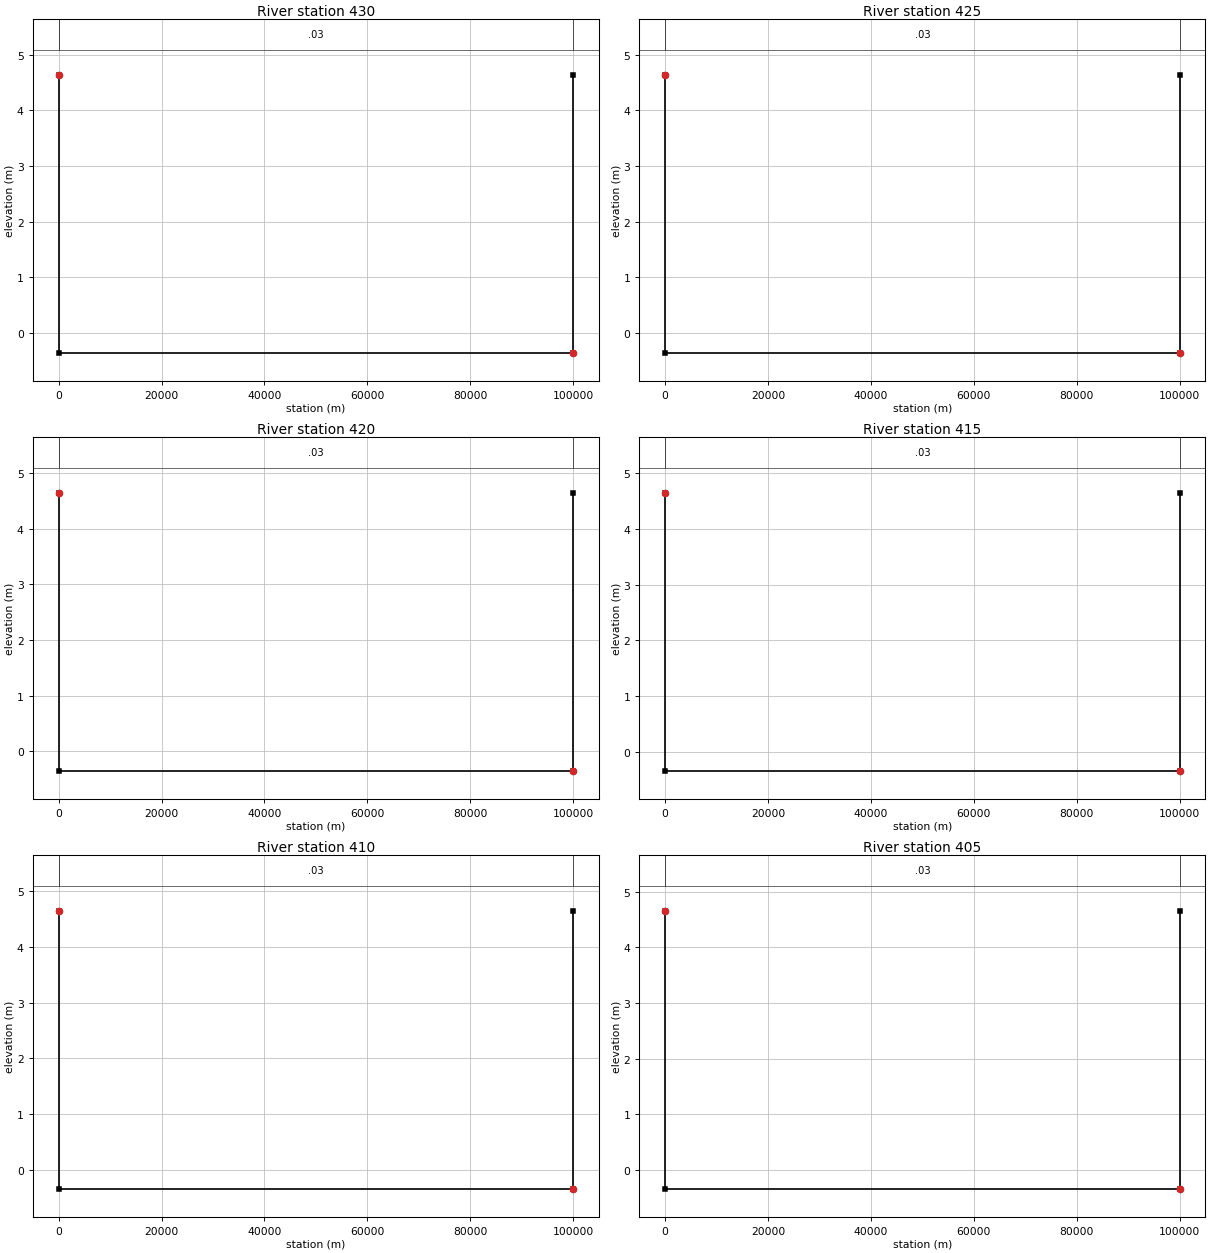
Type RM Length L Ch R = 1 ,430     ,5,5,5
#Sta/Elev= 4
 0.00000 4.63534 0.00000-0.36466  100000-0.36466  100000 4.63534
#Mann= 3 ,0,0
 0.00000 0.03000 0.00000 0.00000 0.03000 0.00000  100000 0.03000 0.00000
Bank Sta=0,100000
XS Rating Curve= 0 ,0
Exp/Cntr=0,0

Type RM Length L Ch R = 1 ,425     ,5,5,5
#Sta/Elev= 4
 0.00000 4.63914 0.00000-0.36086  100000-0.36086  100000 4.63914
#Mann= 3 ,0,0
 0.00000 0.03000 0.00000 0.00000 0.03000 0.00000  100000 0.03000 0.00000
Bank Sta=0,100000
XS Rating Curve= 0 ,0
Exp/Cntr=0,0

Type RM Length L Ch R = 1 ,420     ,5,5,5
#Sta/Elev= 4
 0.00000 4.64317 0.00000-0.35683  100000-0.35683  100000 4.64317
#Mann= 3 ,0,0
 0.00000 0.03000 0.00000 0.00000 0.03000 0.00000  100000 0.03000 0.00000
Bank Sta=0,100000
XS Rating Curve= 0 ,0
Exp/Cntr=0,0

Type RM Length L Ch R = 1 ,415     ,5,5,5
#Sta/Elev= 4
 0.00000  4.6474 0.00000-0.35260  100000-0.35260  100000  4.6474
#Mann= 3 ,0,0
 0.00000 0.03000 0.00000 0.00000 0.03000 0.00000  100000 0.03000 0.00000
Bank Sta=0,100000
XS Rating Curve= 0 ,0
Exp/Cntr=0,0

Type RM Length L Ch R = 1 ,410     ,5,5,5
#Sta/Elev= 4
 0.00000 4.65183 0.00000-0.34817  100000-0.34817  100000 4.65183
#Mann= 3 ,0,0
 0.00000 0.03000 0.00000 0.00000 0.03000 0.00000  100000 0.03000 0.00000
Bank Sta=0,100000
XS Rating Curve= 0 ,0
Exp/Cntr=0,0

Type RM Length L Ch R = 1 ,405     ,5,5,5
#Sta/Elev= 4
 0.00000 4.65645 0.00000-0.34355  100000-0.34355  100000 4.65645
#Mann= 3 ,0,0
 0.00000 0.03000 0.00000 0.00000 0.03000 0.00000  100000 0.03000 0.00000
Bank Sta=0,100000
XS Rating Curve= 0 ,0
Exp/Cntr=0,0

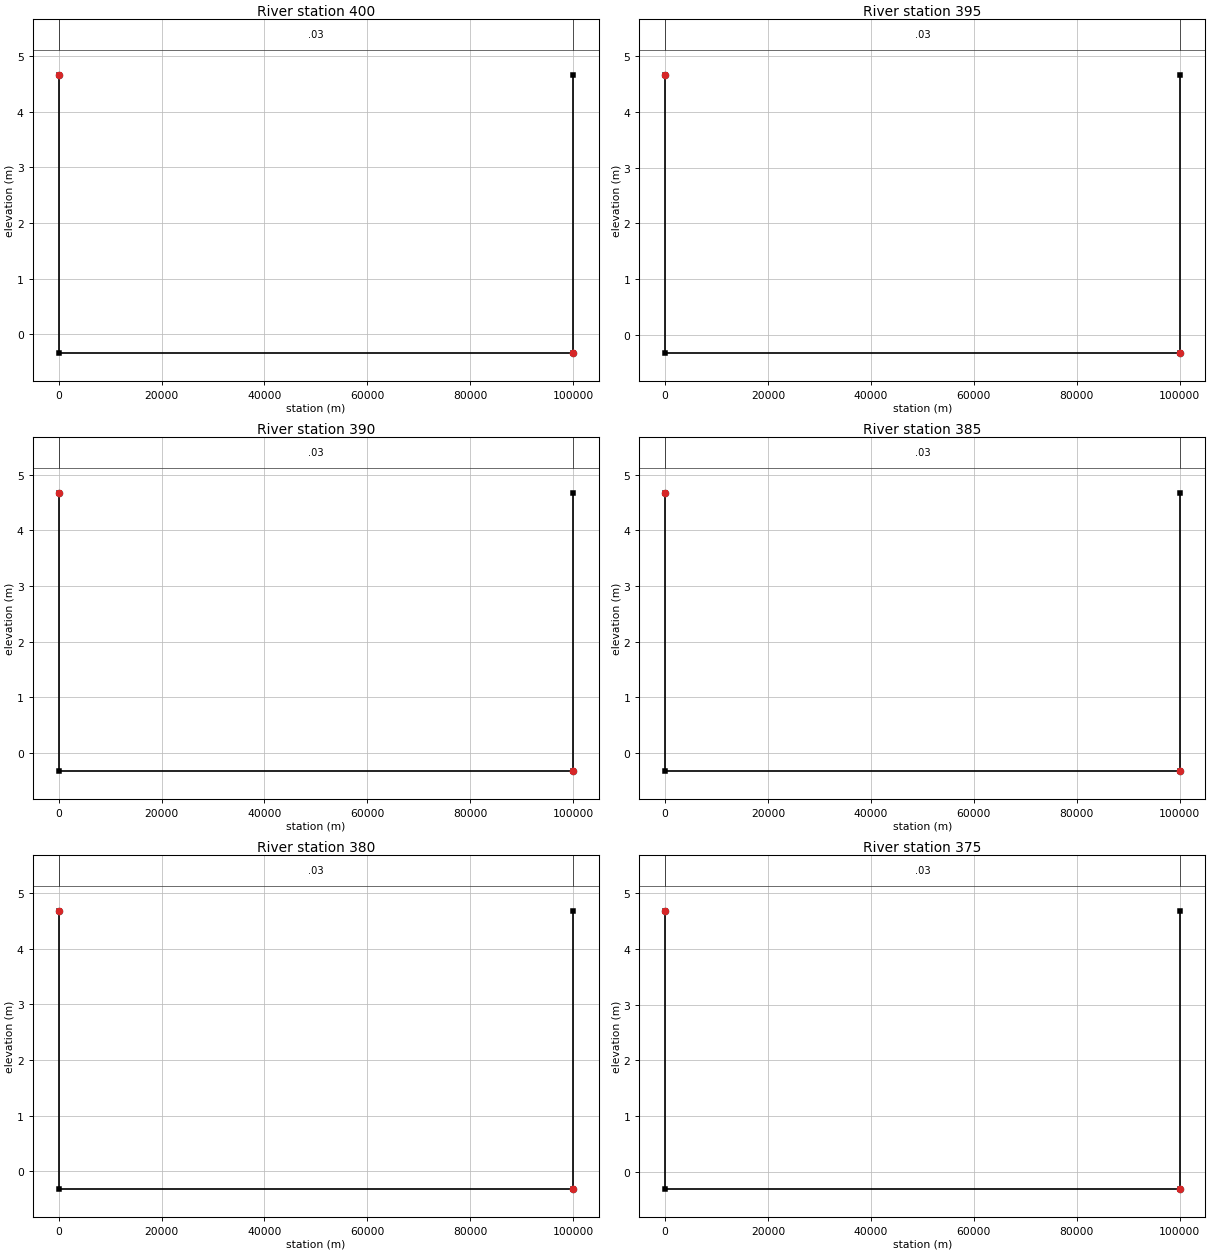
Type RM Length L Ch R = 1 ,400     ,5,5,5
#Sta/Elev= 4
 0.00000 4.66126 0.00000-0.33874  100000-0.33874  100000 4.66126
#Mann= 3 ,0,0
 0.00000 0.03000 0.00000 0.00000 0.03000 0.00000  100000 0.03000 0.00000
Bank Sta=0,100000
XS Rating Curve= 0 ,0
Exp/Cntr=0,0

Type RM Length L Ch R = 1 ,395     ,5,5,5
#Sta/Elev= 4
 0.00000 4.66623 0.00000-0.33377  100000-0.33377  100000 4.66623
#Mann= 3 ,0,0
 0.00000 0.03000 0.00000 0.00000 0.03000 0.00000  100000 0.03000 0.00000
Bank Sta=0,100000
XS Rating Curve= 0 ,0
Exp/Cntr=0,0

Type RM Length L Ch R = 1 ,390     ,5,5,5
#Sta/Elev= 4
 0.00000 4.67136 0.00000-0.32864  100000-0.32864  100000 4.67136
#Mann= 3 ,0,0
 0.00000 0.03000 0.00000 0.00000 0.03000 0.00000  100000 0.03000 0.00000
Bank Sta=0,100000
XS Rating Curve= 0 ,0
Exp/Cntr=0,0

Type RM Length L Ch R = 1 ,385     ,5,5,5
#Sta/Elev= 4
 0.00000 4.67663 0.00000-0.32337  100000-0.32337  100000 4.67663
#Mann= 3 ,0,0
 0.00000 0.03000 0.00000 0.00000 0.03000 0.00000  100000 0.03000 0.00000
Bank Sta=0,100000
XS Rating Curve= 0 ,0
Exp/Cntr=0,0

Type RM Length L Ch R = 1 ,380     ,5,5,5
#Sta/Elev= 4
 0.00000 4.68204 0.00000-0.31796  100000-0.31796  100000 4.68204
#Mann= 3 ,0,0
 0.00000 0.03000 0.00000 0.00000 0.03000 0.00000  100000 0.03000 0.00000
Bank Sta=0,100000
XS Rating Curve= 0 ,0
Exp/Cntr=0,0

Type RM Length L Ch R = 1 ,375     ,5,5,5
#Sta/Elev= 4
 0.00000 4.68757 0.00000-0.31243  100000-0.31243  100000 4.68757
#Mann= 3 ,0,0
 0.00000 0.03000 0.00000 0.00000 0.03000 0.00000  100000 0.03000 0.00000
Bank Sta=0,100000
XS Rating Curve= 0 ,0
Exp/Cntr=0,0

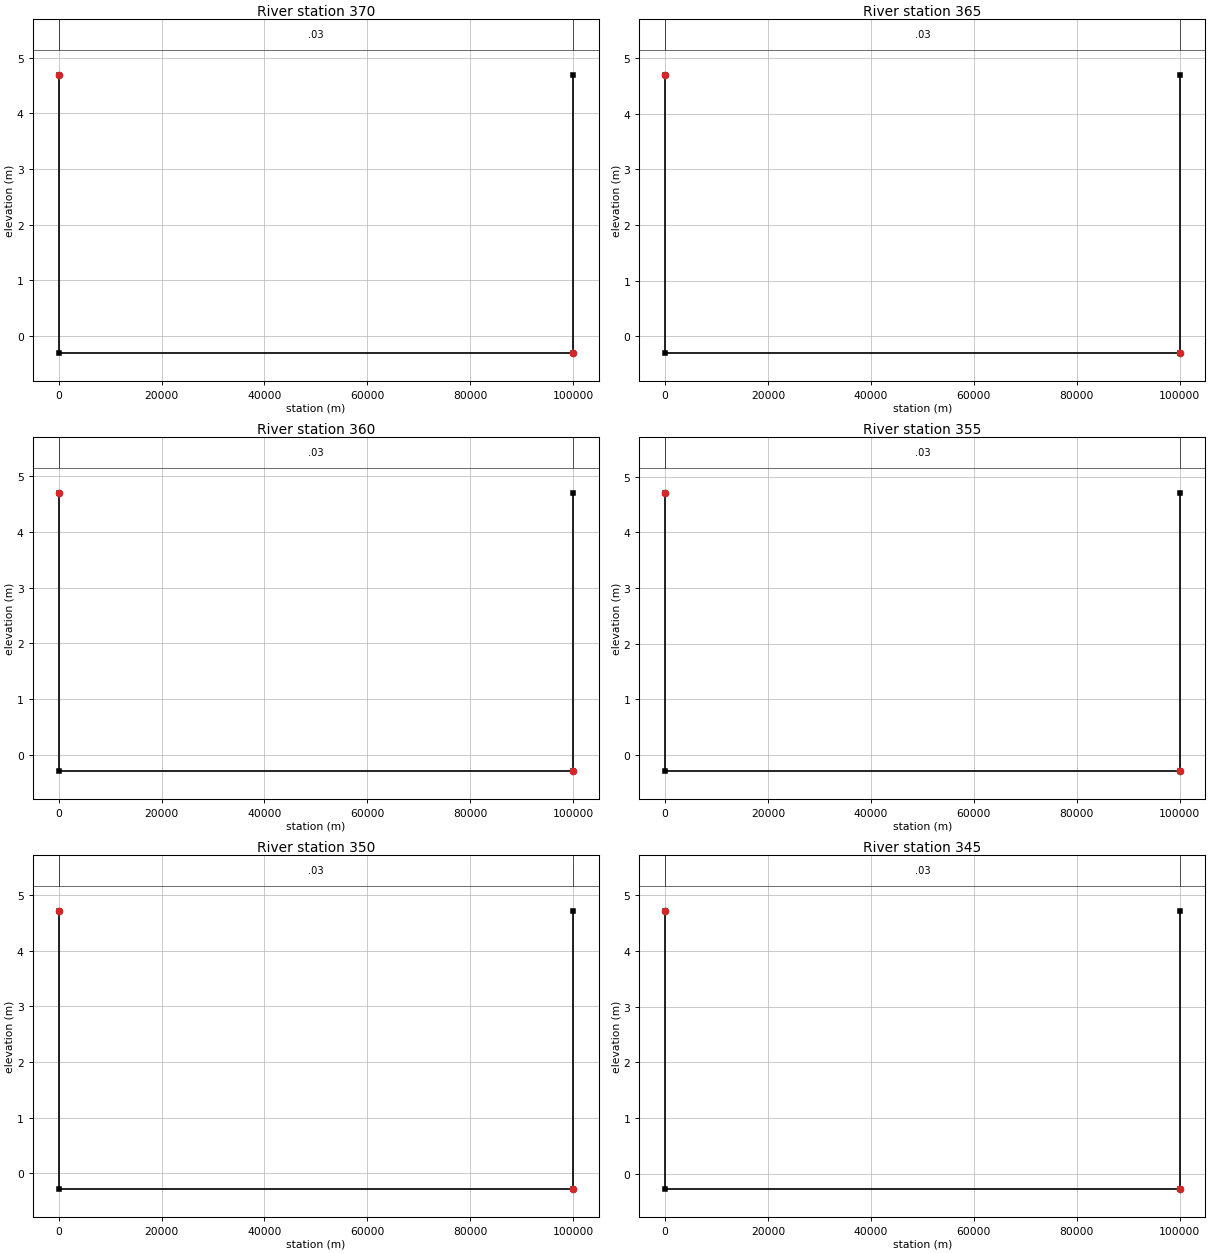
Type RM Length L Ch R = 1 ,370     ,5,5,5
#Sta/Elev= 4
 0.00000 4.69322 0.00000-0.30678  100000-0.30678  100000 4.69322
#Mann= 3 ,0,0
 0.00000 0.03000 0.00000 0.00000 0.03000 0.00000  100000 0.03000 0.00000
Bank Sta=0,100000
XS Rating Curve= 0 ,0
Exp/Cntr=0,0

Type RM Length L Ch R = 1 ,365     ,5,5,5
#Sta/Elev= 4
 0.00000 4.69896 0.00000-0.30104  100000-0.30104  100000 4.69896
#Mann= 3 ,0,0
 0.00000 0.03000 0.00000 0.00000 0.03000 0.00000  100000 0.03000 0.00000
Bank Sta=0,100000
XS Rating Curve= 0 ,0
Exp/Cntr=0,0

Type RM Length L Ch R = 1 ,360     ,5,5,5
#Sta/Elev= 4
 0.00000 4.70479 0.00000-0.29521  100000-0.29521  100000 4.70479
#Mann= 3 ,0,0
 0.00000 0.03000 0.00000 0.00000 0.03000 0.00000  100000 0.03000 0.00000
Bank Sta=0,100000
XS Rating Curve= 0 ,0
Exp/Cntr=0,0

Type RM Length L Ch R = 1 ,355     ,5,5,5
#Sta/Elev= 4
 0.00000  4.7107 0.00000-0.28930  100000-0.28930  100000  4.7107
#Mann= 3 ,0,0
 0.00000 0.03000 0.00000 0.00000 0.03000 0.00000  100000 0.03000 0.00000
Bank Sta=0,100000
XS Rating Curve= 0 ,0
Exp/Cntr=0,0

Type RM Length L Ch R = 1 ,350     ,5,5,5
#Sta/Elev= 4
 0.00000 4.71668 0.00000-0.28332  100000-0.28332  100000 4.71668
#Mann= 3 ,0,0
 0.00000 0.03000 0.00000 0.00000 0.03000 0.00000  100000 0.03000 0.00000
Bank Sta=0,100000
XS Rating Curve= 0 ,0
Exp/Cntr=0,0

Type RM Length L Ch R = 1 ,345     ,5,5,5
#Sta/Elev= 4
 0.00000 4.72271 0.00000-0.27729  100000-0.27729  100000 4.72271
#Mann= 3 ,0,0
 0.00000 0.03000 0.00000 0.00000 0.03000 0.00000  100000 0.03000 0.00000
Bank Sta=0,100000
XS Rating Curve= 0 ,0
Exp/Cntr=0,0

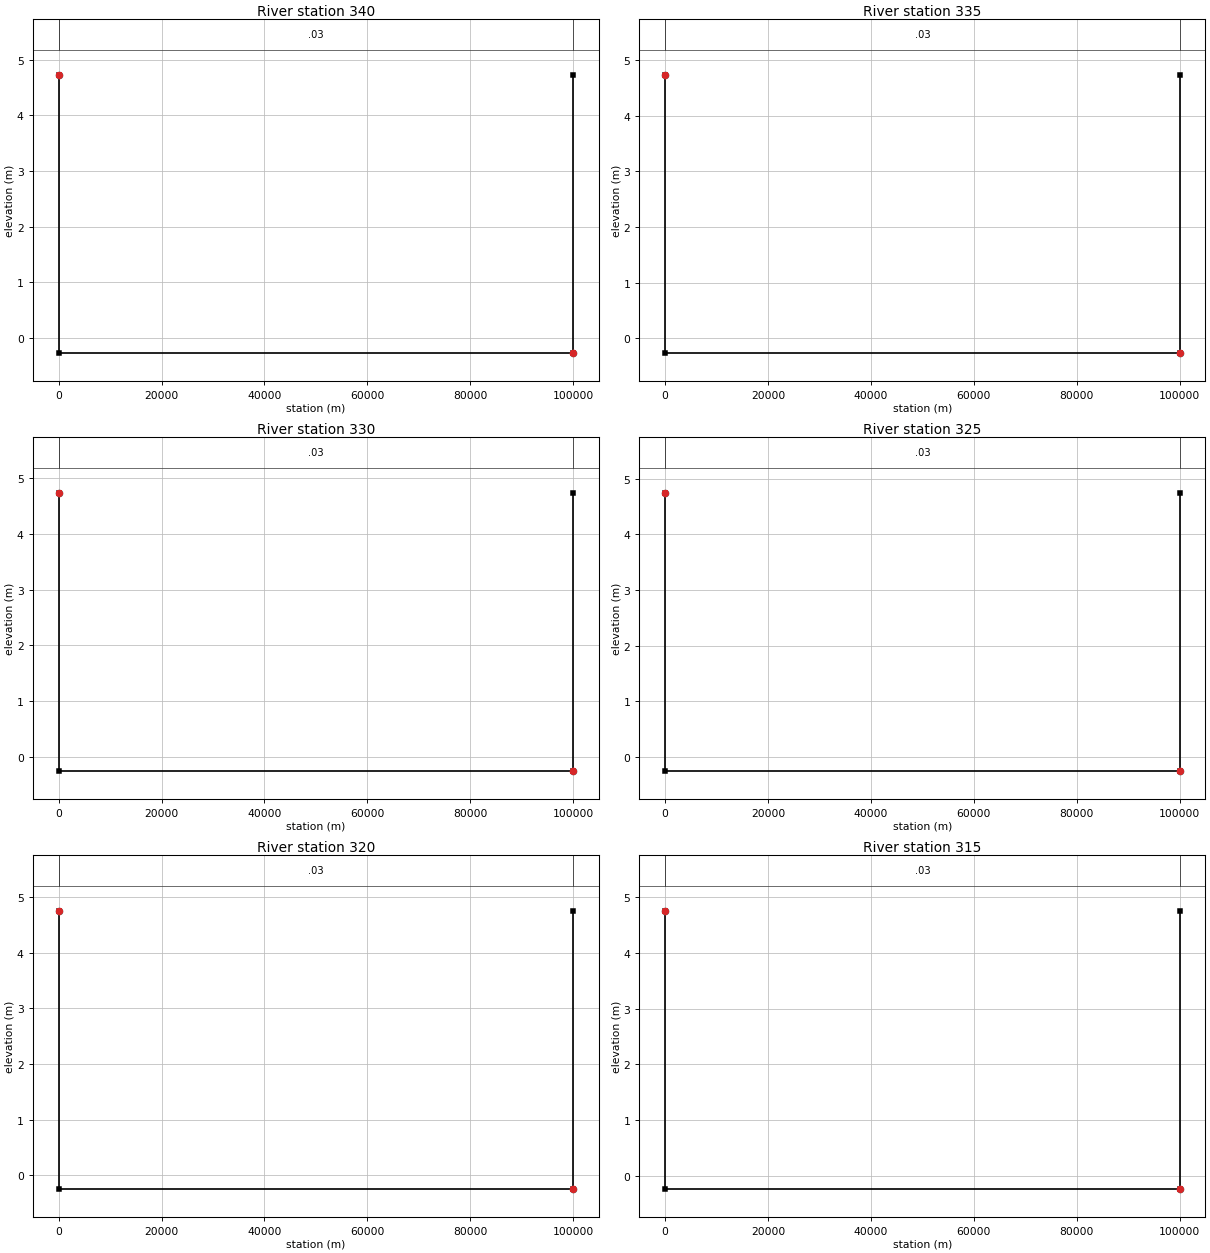
Type RM Length L Ch R = 1 ,340     ,5,5,5
#Sta/Elev= 4
 0.00000 4.72878 0.00000-0.27122  100000-0.27122  100000 4.72878
#Mann= 3 ,0,0
 0.00000 0.03000 0.00000 0.00000 0.03000 0.00000  100000 0.03000 0.00000
Bank Sta=0,100000
XS Rating Curve= 0 ,0
Exp/Cntr=0,0

Type RM Length L Ch R = 1 ,335     ,5,5,5
#Sta/Elev= 4
 0.00000 4.73488 0.00000-0.26512  100000-0.26512  100000 4.73488
#Mann= 3 ,0,0
 0.00000 0.03000 0.00000 0.00000 0.03000 0.00000  100000 0.03000 0.00000
Bank Sta=0,100000
XS Rating Curve= 0 ,0
Exp/Cntr=0,0

Type RM Length L Ch R = 1 ,330     ,5,5,5
#Sta/Elev= 4
 0.00000   4.741 0.00000-0.25900  100000-0.25900  100000   4.741
#Mann= 3 ,0,0
 0.00000 0.03000 0.00000 0.00000 0.03000 0.00000  100000 0.03000 0.00000
Bank Sta=0,100000
XS Rating Curve= 0 ,0
Exp/Cntr=0,0

Type RM Length L Ch R = 1 ,325     ,5,5,5
#Sta/Elev= 4
 0.00000 4.74713 0.00000-0.25287  100000-0.25287  100000 4.74713
#Mann= 3 ,0,0
 0.00000 0.03000 0.00000 0.00000 0.03000 0.00000  100000 0.03000 0.00000
Bank Sta=0,100000
XS Rating Curve= 0 ,0
Exp/Cntr=0,0

Type RM Length L Ch R = 1 ,320     ,5,5,5
#Sta/Elev= 4
 0.00000 4.75326 0.00000-0.24674  100000-0.24674  100000 4.75326
#Mann= 3 ,0,0
 0.00000 0.03000 0.00000 0.00000 0.03000 0.00000  100000 0.03000 0.00000
Bank Sta=0,100000
XS Rating Curve= 0 ,0
Exp/Cntr=0,0

Type RM Length L Ch R = 1 ,315     ,5,5,5
#Sta/Elev= 4
 0.00000 4.75937 0.00000-0.24063  100000-0.24063  100000 4.75937
#Mann= 3 ,0,0
 0.00000 0.03000 0.00000 0.00000 0.03000 0.00000  100000 0.03000 0.00000
Bank Sta=0,100000
XS Rating Curve= 0 ,0
Exp/Cntr=0,0

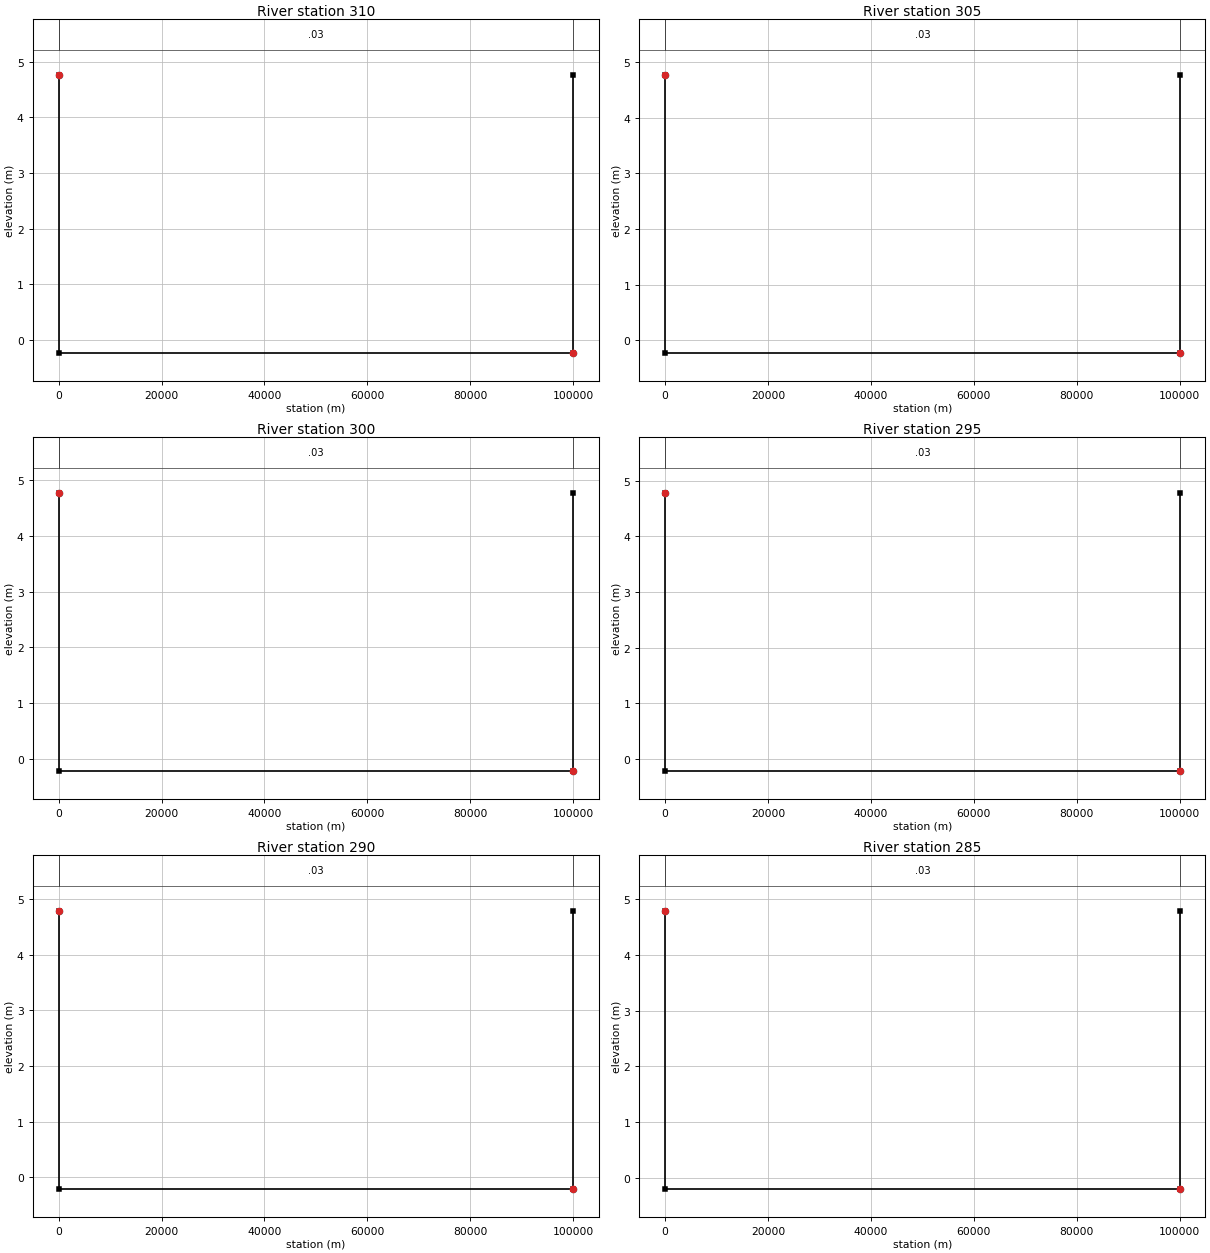
Type RM Length L Ch R = 1 ,310     ,5,5,5
#Sta/Elev= 4
 0.00000 4.76547 0.00000-0.23453  100000-0.23453  100000 4.76547
#Mann= 3 ,0,0
 0.00000 0.03000 0.00000 0.00000 0.03000 0.00000  100000 0.03000 0.00000
Bank Sta=0,100000
XS Rating Curve= 0 ,0
Exp/Cntr=0,0

Type RM Length L Ch R = 1 ,305     ,5,5,5
#Sta/Elev= 4
 0.00000 4.77154 0.00000-0.22846  100000-0.22846  100000 4.77154
#Mann= 3 ,0,0
 0.00000 0.03000 0.00000 0.00000 0.03000 0.00000  100000 0.03000 0.00000
Bank Sta=0,100000
XS Rating Curve= 0 ,0
Exp/Cntr=0,0

Type RM Length L Ch R = 1 ,300     ,5,5,5
#Sta/Elev= 4
 0.00000 4.77756 0.00000-0.22244  100000-0.22244  100000 4.77756
#Mann= 3 ,0,0
 0.00000 0.03000 0.00000 0.00000 0.03000 0.00000  100000 0.03000 0.00000
Bank Sta=0,100000
XS Rating Curve= 0 ,0
Exp/Cntr=0,0

Type RM Length L Ch R = 1 ,295     ,5,5,5
#Sta/Elev= 4
 0.00000 4.78354 0.00000-0.21646  100000-0.21646  100000 4.78354
#Mann= 3 ,0,0
 0.00000 0.03000 0.00000 0.00000 0.03000 0.00000  100000 0.03000 0.00000
Bank Sta=0,100000
XS Rating Curve= 0 ,0
Exp/Cntr=0,0

Type RM Length L Ch R = 1 ,290     ,5,5,5
#Sta/Elev= 4
 0.00000 4.78945 0.00000-0.21055  100000-0.21055  100000 4.78945
#Mann= 3 ,0,0
 0.00000 0.03000 0.00000 0.00000 0.03000 0.00000  100000 0.03000 0.00000
Bank Sta=0,100000
XS Rating Curve= 0 ,0
Exp/Cntr=0,0

Type RM Length L Ch R = 1 ,285     ,5,5,5
#Sta/Elev= 4
 0.00000 4.79531 0.00000-0.20469  100000-0.20469  100000 4.79531
#Mann= 3 ,0,0
 0.00000 0.03000 0.00000 0.00000 0.03000 0.00000  100000 0.03000 0.00000
Bank Sta=0,100000
XS Rating Curve= 0 ,0
Exp/Cntr=0,0

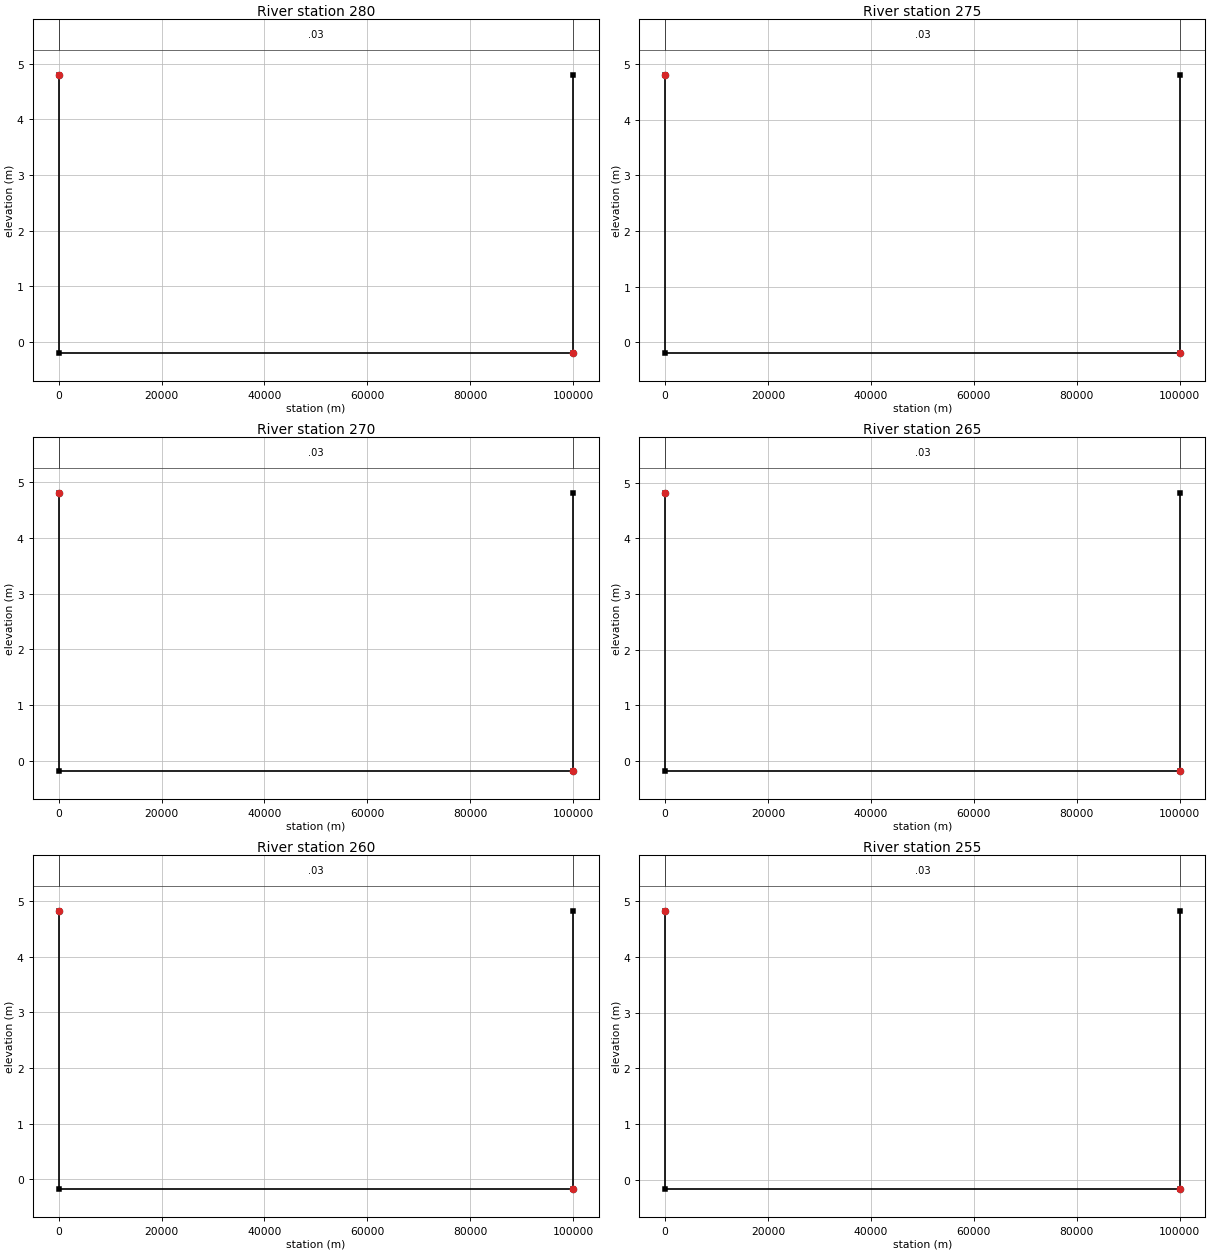
Type RM Length L Ch R = 1 ,280     ,5,5,5
#Sta/Elev= 4
 0.00000 4.80108 0.00000-0.19892  100000-0.19892  100000 4.80108
#Mann= 3 ,0,0
 0.00000 0.03000 0.00000 0.00000 0.03000 0.00000  100000 0.03000 0.00000
Bank Sta=0,100000
XS Rating Curve= 0 ,0
Exp/Cntr=0,0

Type RM Length L Ch R = 1 ,275     ,5,5,5
#Sta/Elev= 4
 0.00000 4.80678 0.00000-0.19322  100000-0.19322  100000 4.80678
#Mann= 3 ,0,0
 0.00000 0.03000 0.00000 0.00000 0.03000 0.00000  100000 0.03000 0.00000
Bank Sta=0,100000
XS Rating Curve= 0 ,0
Exp/Cntr=0,0

Type RM Length L Ch R = 1 ,270     ,5,5,5
#Sta/Elev= 4
 0.00000 4.81239 0.00000-0.18761  100000-0.18761  100000 4.81239
#Mann= 3 ,0,0
 0.00000 0.03000 0.00000 0.00000 0.03000 0.00000  100000 0.03000 0.00000
Bank Sta=0,100000
XS Rating Curve= 0 ,0
Exp/Cntr=0,0

Type RM Length L Ch R = 1 ,265     ,5,5,5
#Sta/Elev= 4
 0.00000 4.81791 0.00000-0.18209  100000-0.18209  100000 4.81791
#Mann= 3 ,0,0
 0.00000 0.03000 0.00000 0.00000 0.03000 0.00000  100000 0.03000 0.00000
Bank Sta=0,100000
XS Rating Curve= 0 ,0
Exp/Cntr=0,0

Type RM Length L Ch R = 1 ,260     ,5,5,5
#Sta/Elev= 4
 0.00000 4.82333 0.00000-0.17667  100000-0.17667  100000 4.82333
#Mann= 3 ,0,0
 0.00000 0.03000 0.00000 0.00000 0.03000 0.00000  100000 0.03000 0.00000
Bank Sta=0,100000
XS Rating Curve= 0 ,0
Exp/Cntr=0,0

Type RM Length L Ch R = 1 ,255     ,5,5,5
#Sta/Elev= 4
 0.00000 4.82864 0.00000-0.17136  100000-0.17136  100000 4.82864
#Mann= 3 ,0,0
 0.00000 0.03000 0.00000 0.00000 0.03000 0.00000  100000 0.03000 0.00000
Bank Sta=0,100000
XS Rating Curve= 0 ,0
Exp/Cntr=0,0

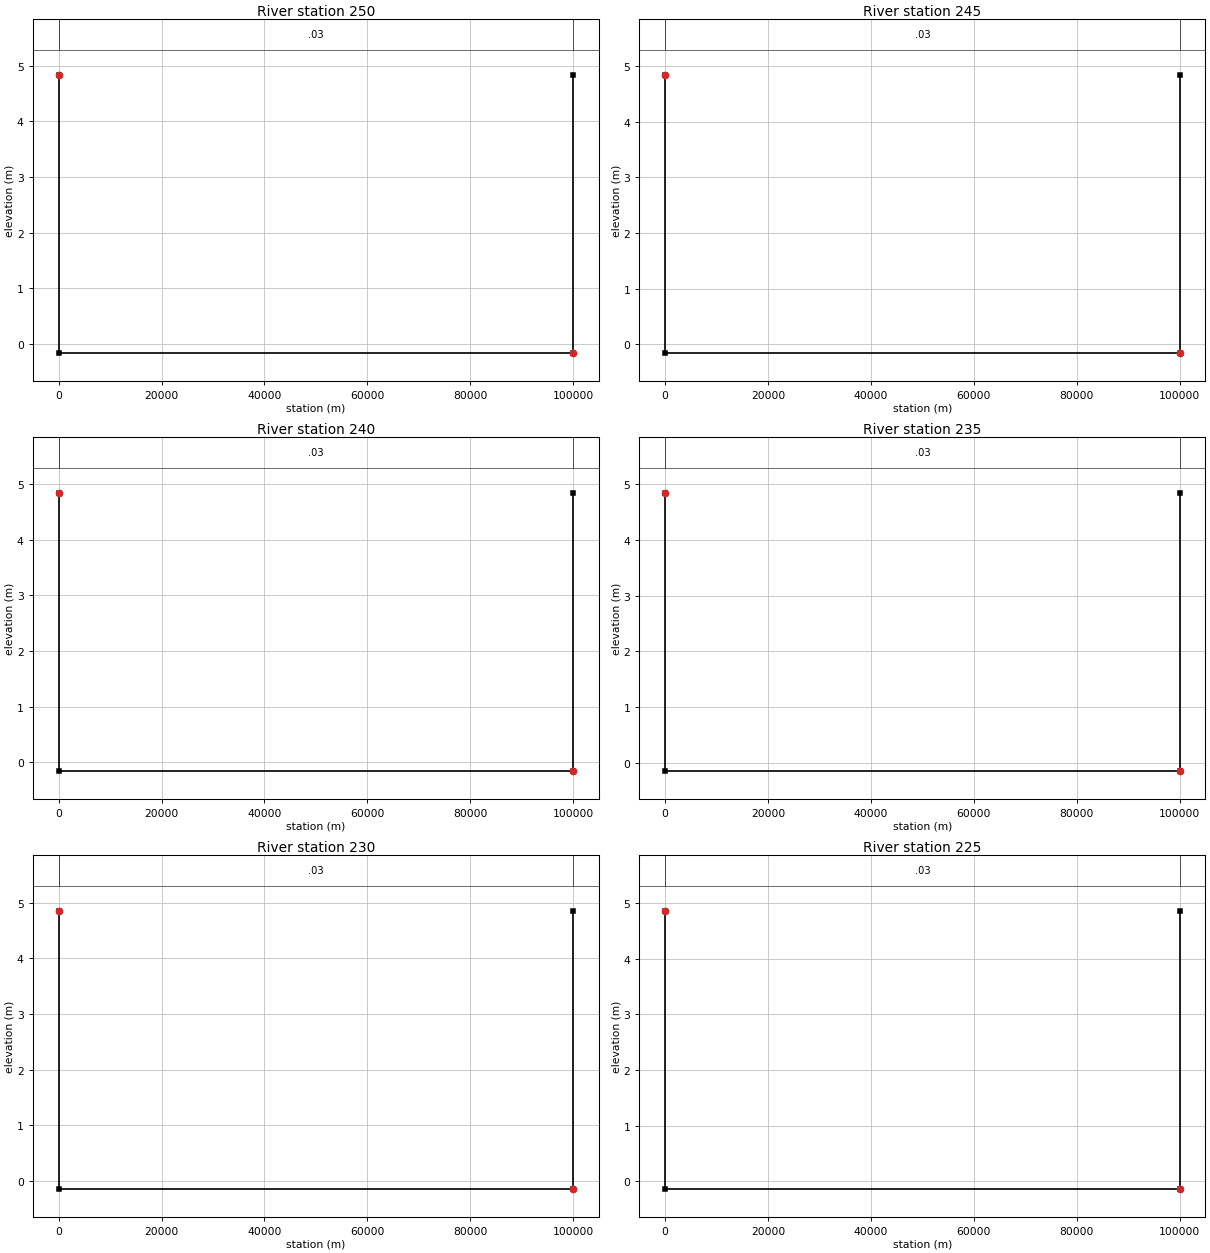
Type RM Length L Ch R = 1 ,250     ,5,5,5
#Sta/Elev= 4
 0.00000 4.83384 0.00000-0.16616  100000-0.16616  100000 4.83384
#Mann= 3 ,0,0
 0.00000 0.03000 0.00000 0.00000 0.03000 0.00000  100000 0.03000 0.00000
Bank Sta=0,100000
XS Rating Curve= 0 ,0
Exp/Cntr=0,0

Type RM Length L Ch R = 1 ,245     ,5,5,5
#Sta/Elev= 4
 0.00000 4.83893 0.00000-0.16107  100000-0.16107  100000 4.83893
#Mann= 3 ,0,0
 0.00000 0.03000 0.00000 0.00000 0.03000 0.00000  100000 0.03000 0.00000
Bank Sta=0,100000
XS Rating Curve= 0 ,0
Exp/Cntr=0,0

Type RM Length L Ch R = 1 ,240     ,5,5,5
#Sta/Elev= 4
 0.00000  4.8439 0.00000-0.15610  100000-0.15610  100000  4.8439
#Mann= 3 ,0,0
 0.00000 0.03000 0.00000 0.00000 0.03000 0.00000  100000 0.03000 0.00000
Bank Sta=0,100000
XS Rating Curve= 0 ,0
Exp/Cntr=0,0

Type RM Length L Ch R = 1 ,235     ,5,5,5
#Sta/Elev= 4
 0.00000 4.84874 0.00000-0.15126  100000-0.15126  100000 4.84874
#Mann= 3 ,0,0
 0.00000 0.03000 0.00000 0.00000 0.03000 0.00000  100000 0.03000 0.00000
Bank Sta=0,100000
XS Rating Curve= 0 ,0
Exp/Cntr=0,0

Type RM Length L Ch R = 1 ,230     ,5,5,5
#Sta/Elev= 4
 0.00000 4.85346 0.00000-0.14654  100000-0.14654  100000 4.85346
#Mann= 3 ,0,0
 0.00000 0.03000 0.00000 0.00000 0.03000 0.00000  100000 0.03000 0.00000
Bank Sta=0,100000
XS Rating Curve= 0 ,0
Exp/Cntr=0,0

Type RM Length L Ch R = 1 ,225     ,5,5,5
#Sta/Elev= 4
 0.00000 4.85805 0.00000-0.14195  100000-0.14195  100000 4.85805
#Mann= 3 ,0,0
 0.00000 0.03000 0.00000 0.00000 0.03000 0.00000  100000 0.03000 0.00000
Bank Sta=0,100000
XS Rating Curve= 0 ,0
Exp/Cntr=0,0

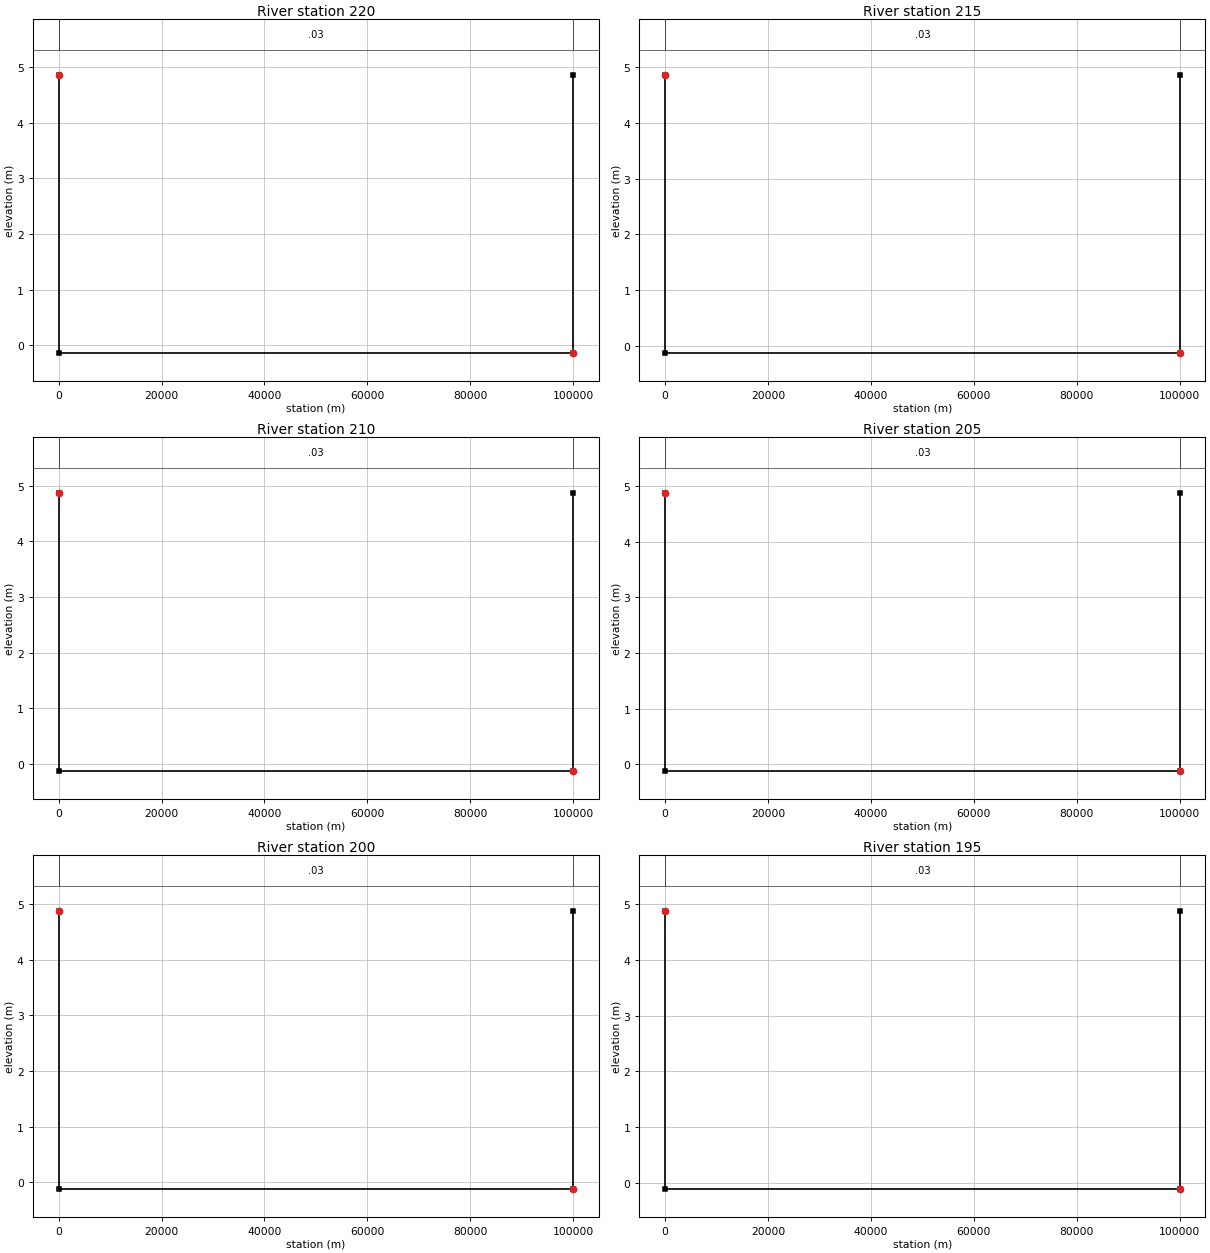
Type RM Length L Ch R = 1 ,220     ,5,5,5
#Sta/Elev= 4
 0.00000 4.86251 0.00000-0.13749  100000-0.13749  100000 4.86251
#Mann= 3 ,0,0
 0.00000 0.03000 0.00000 0.00000 0.03000 0.00000  100000 0.03000 0.00000
Bank Sta=0,100000
XS Rating Curve= 0 ,0
Exp/Cntr=0,0

Type RM Length L Ch R = 1 ,215     ,5,5,5
#Sta/Elev= 4
 0.00000 4.86684 0.00000-0.13316  100000-0.13316  100000 4.86684
#Mann= 3 ,0,0
 0.00000 0.03000 0.00000 0.00000 0.03000 0.00000  100000 0.03000 0.00000
Bank Sta=0,100000
XS Rating Curve= 0 ,0
Exp/Cntr=0,0

Type RM Length L Ch R = 1 ,210     ,5,5,5
#Sta/Elev= 4
 0.00000 4.87103 0.00000-0.12897  100000-0.12897  100000 4.87103
#Mann= 3 ,0,0
 0.00000 0.03000 0.00000 0.00000 0.03000 0.00000  100000 0.03000 0.00000
Bank Sta=0,100000
XS Rating Curve= 0 ,0
Exp/Cntr=0,0

Type RM Length L Ch R = 1 ,205     ,5,5,5
#Sta/Elev= 4
 0.00000 4.87509 0.00000-0.12491  100000-0.12491  100000 4.87509
#Mann= 3 ,0,0
 0.00000 0.03000 0.00000 0.00000 0.03000 0.00000  100000 0.03000 0.00000
Bank Sta=0,100000
XS Rating Curve= 0 ,0
Exp/Cntr=0,0

Type RM Length L Ch R = 1 ,200     ,5,5,5
#Sta/Elev= 4
 0.00000 4.87901 0.00000-0.12099  100000-0.12099  100000 4.87901
#Mann= 3 ,0,0
 0.00000 0.03000 0.00000 0.00000 0.03000 0.00000  100000 0.03000 0.00000
Bank Sta=0,100000
XS Rating Curve= 0 ,0
Exp/Cntr=0,0

Type RM Length L Ch R = 1 ,195     ,5,5,5
#Sta/Elev= 4
 0.00000 4.88279 0.00000-0.11721  100000-0.11721  100000 4.88279
#Mann= 3 ,0,0
 0.00000 0.03000 0.00000 0.00000 0.03000 0.00000  100000 0.03000 0.00000
Bank Sta=0,100000
XS Rating Curve= 0 ,0
Exp/Cntr=0,0