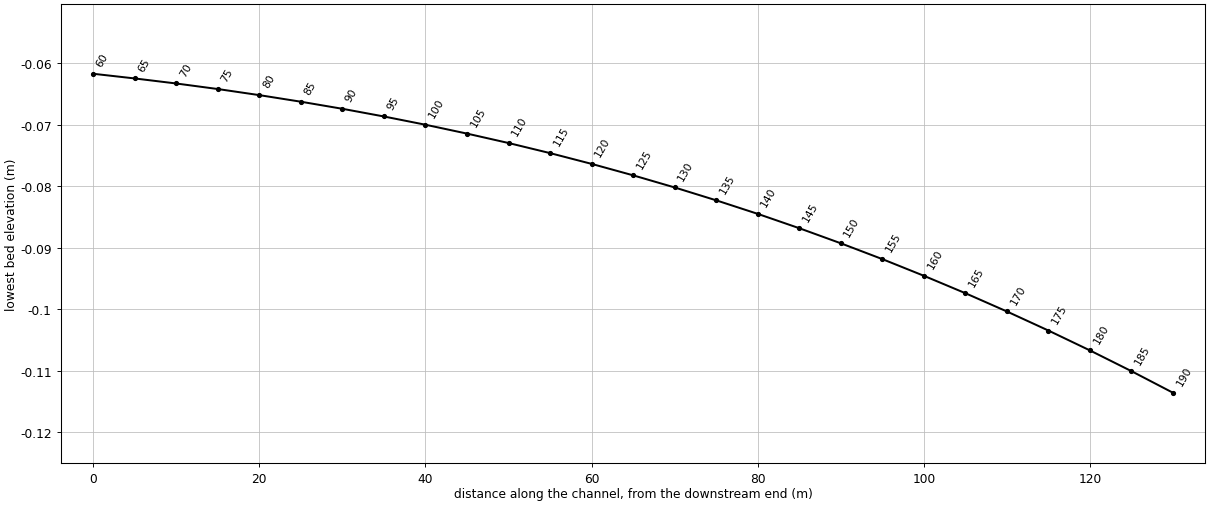
HEC-RAS study macdonald.prj: A1F-001 MacDonald backwater dx=5 m

--- macdonald.g01 (geometry) --- (continued)

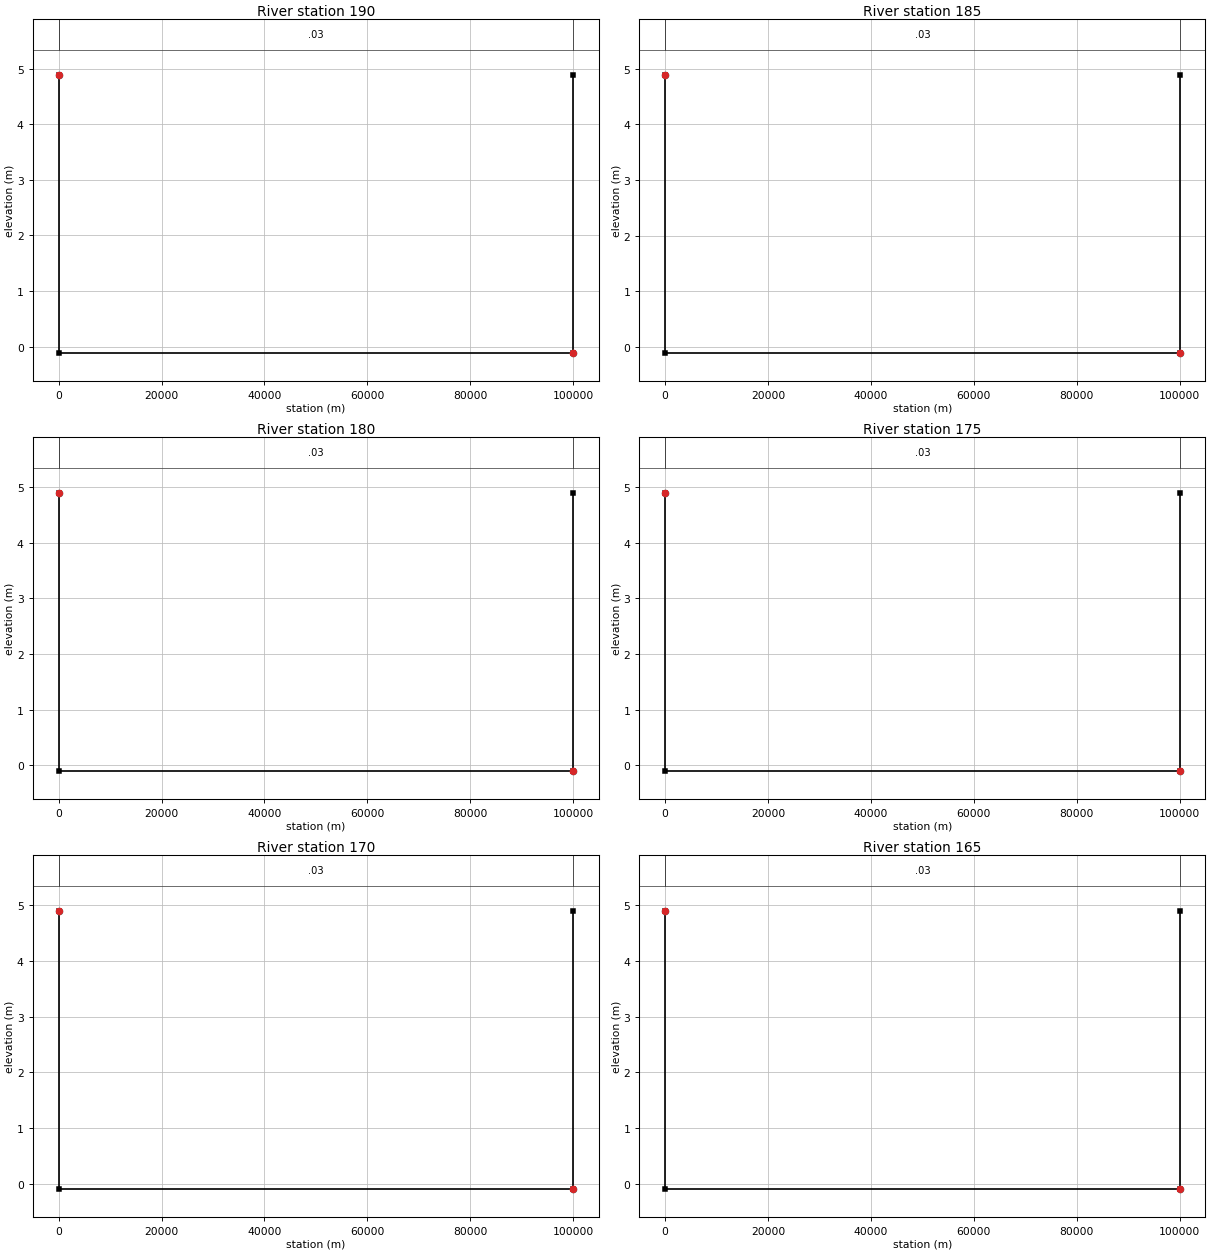
Type RM Length L Ch R = 1 ,190     ,5,5,5
#Sta/Elev= 4
 0.00000 4.88643 0.00000-0.11357  100000-0.11357  100000 4.88643
#Mann= 3 ,0,0
 0.00000 0.03000 0.00000 0.00000 0.03000 0.00000  100000 0.03000 0.00000
Bank Sta=0,100000
XS Rating Curve= 0 ,0
Exp/Cntr=0,0

Type RM Length L Ch R = 1 ,185     ,5,5,5
#Sta/Elev= 4
 0.00000 4.88994 0.00000-0.11006  100000-0.11006  100000 4.88994
#Mann= 3 ,0,0
 0.00000 0.03000 0.00000 0.00000 0.03000 0.00000  100000 0.03000 0.00000
Bank Sta=0,100000
XS Rating Curve= 0 ,0
Exp/Cntr=0,0

Type RM Length L Ch R = 1 ,180     ,5,5,5
#Sta/Elev= 4
 0.00000 4.89331 0.00000-0.10669  100000-0.10669  100000 4.89331
#Mann= 3 ,0,0
 0.00000 0.03000 0.00000 0.00000 0.03000 0.00000  100000 0.03000 0.00000
Bank Sta=0,100000
XS Rating Curve= 0 ,0
Exp/Cntr=0,0

Type RM Length L Ch R = 1 ,175     ,5,5,5
#Sta/Elev= 4
 0.00000 4.89654 0.00000-0.10346  100000-0.10346  100000 4.89654
#Mann= 3 ,0,0
 0.00000 0.03000 0.00000 0.00000 0.03000 0.00000  100000 0.03000 0.00000
Bank Sta=0,100000
XS Rating Curve= 0 ,0
Exp/Cntr=0,0

Type RM Length L Ch R = 1 ,170     ,5,5,5
#Sta/Elev= 4
 0.00000 4.89964 0.00000-0.10036  100000-0.10036  100000 4.89964
#Mann= 3 ,0,0
 0.00000 0.03000 0.00000 0.00000 0.03000 0.00000  100000 0.03000 0.00000
Bank Sta=0,100000
XS Rating Curve= 0 ,0
Exp/Cntr=0,0

Type RM Length L Ch R = 1 ,165     ,5,5,5
#Sta/Elev= 4
 0.00000 4.90261 0.00000-0.09739  100000-0.09739  100000 4.90261
#Mann= 3 ,0,0
 0.00000 0.03000 0.00000 0.00000 0.03000 0.00000  100000 0.03000 0.00000
Bank Sta=0,100000
XS Rating Curve= 0 ,0
Exp/Cntr=0,0

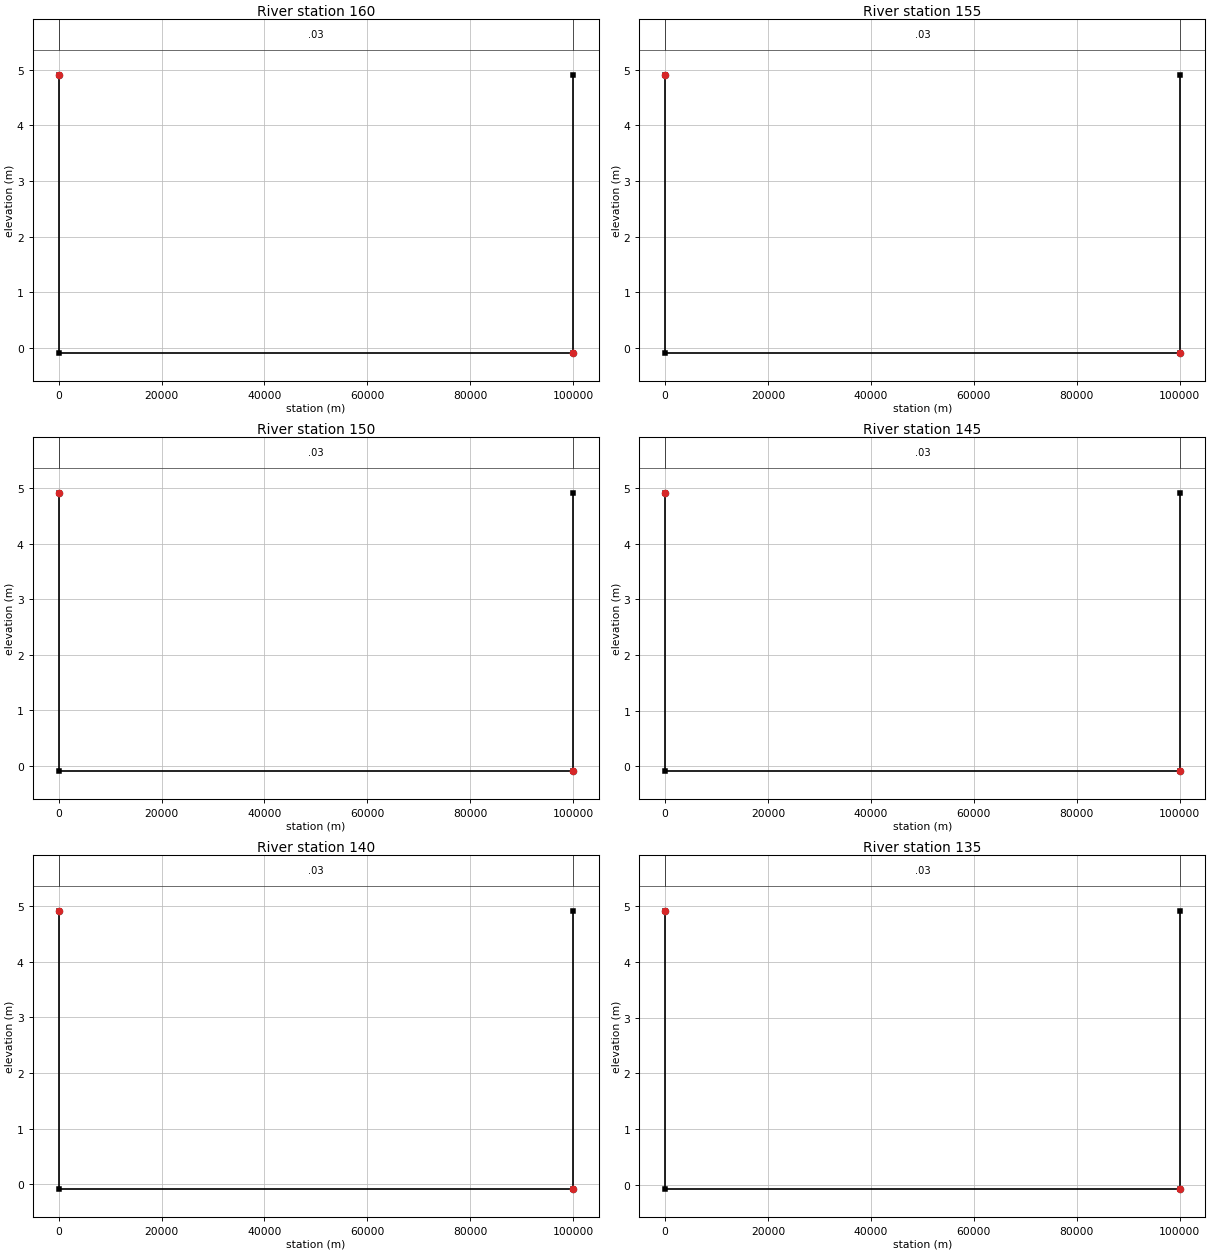
Type RM Length L Ch R = 1 ,160     ,5,5,5
#Sta/Elev= 4
 0.00000 4.90544 0.00000-0.09456  100000-0.09456  100000 4.90544
#Mann= 3 ,0,0
 0.00000 0.03000 0.00000 0.00000 0.03000 0.00000  100000 0.03000 0.00000
Bank Sta=0,100000
XS Rating Curve= 0 ,0
Exp/Cntr=0,0

Type RM Length L Ch R = 1 ,155     ,5,5,5
#Sta/Elev= 4
 0.00000 4.90815 0.00000-0.09185  100000-0.09185  100000 4.90815
#Mann= 3 ,0,0
 0.00000 0.03000 0.00000 0.00000 0.03000 0.00000  100000 0.03000 0.00000
Bank Sta=0,100000
XS Rating Curve= 0 ,0
Exp/Cntr=0,0

Type RM Length L Ch R = 1 ,150     ,5,5,5
#Sta/Elev= 4
 0.00000 4.91072 0.00000-0.08928  100000-0.08928  100000 4.91072
#Mann= 3 ,0,0
 0.00000 0.03000 0.00000 0.00000 0.03000 0.00000  100000 0.03000 0.00000
Bank Sta=0,100000
XS Rating Curve= 0 ,0
Exp/Cntr=0,0

Type RM Length L Ch R = 1 ,145     ,5,5,5
#Sta/Elev= 4
 0.00000 4.91317 0.00000-0.08683  100000-0.08683  100000 4.91317
#Mann= 3 ,0,0
 0.00000 0.03000 0.00000 0.00000 0.03000 0.00000  100000 0.03000 0.00000
Bank Sta=0,100000
XS Rating Curve= 0 ,0
Exp/Cntr=0,0

Type RM Length L Ch R = 1 ,140     ,5,5,5
#Sta/Elev= 4
 0.00000  4.9155 0.00000-0.08450  100000-0.08450  100000  4.9155
#Mann= 3 ,0,0
 0.00000 0.03000 0.00000 0.00000 0.03000 0.00000  100000 0.03000 0.00000
Bank Sta=0,100000
XS Rating Curve= 0 ,0
Exp/Cntr=0,0

Type RM Length L Ch R = 1 ,135     ,5,5,5
#Sta/Elev= 4
 0.00000  4.9177 0.00000-0.08230  100000-0.08230  100000  4.9177
#Mann= 3 ,0,0
 0.00000 0.03000 0.00000 0.00000 0.03000 0.00000  100000 0.03000 0.00000
Bank Sta=0,100000
XS Rating Curve= 0 ,0
Exp/Cntr=0,0

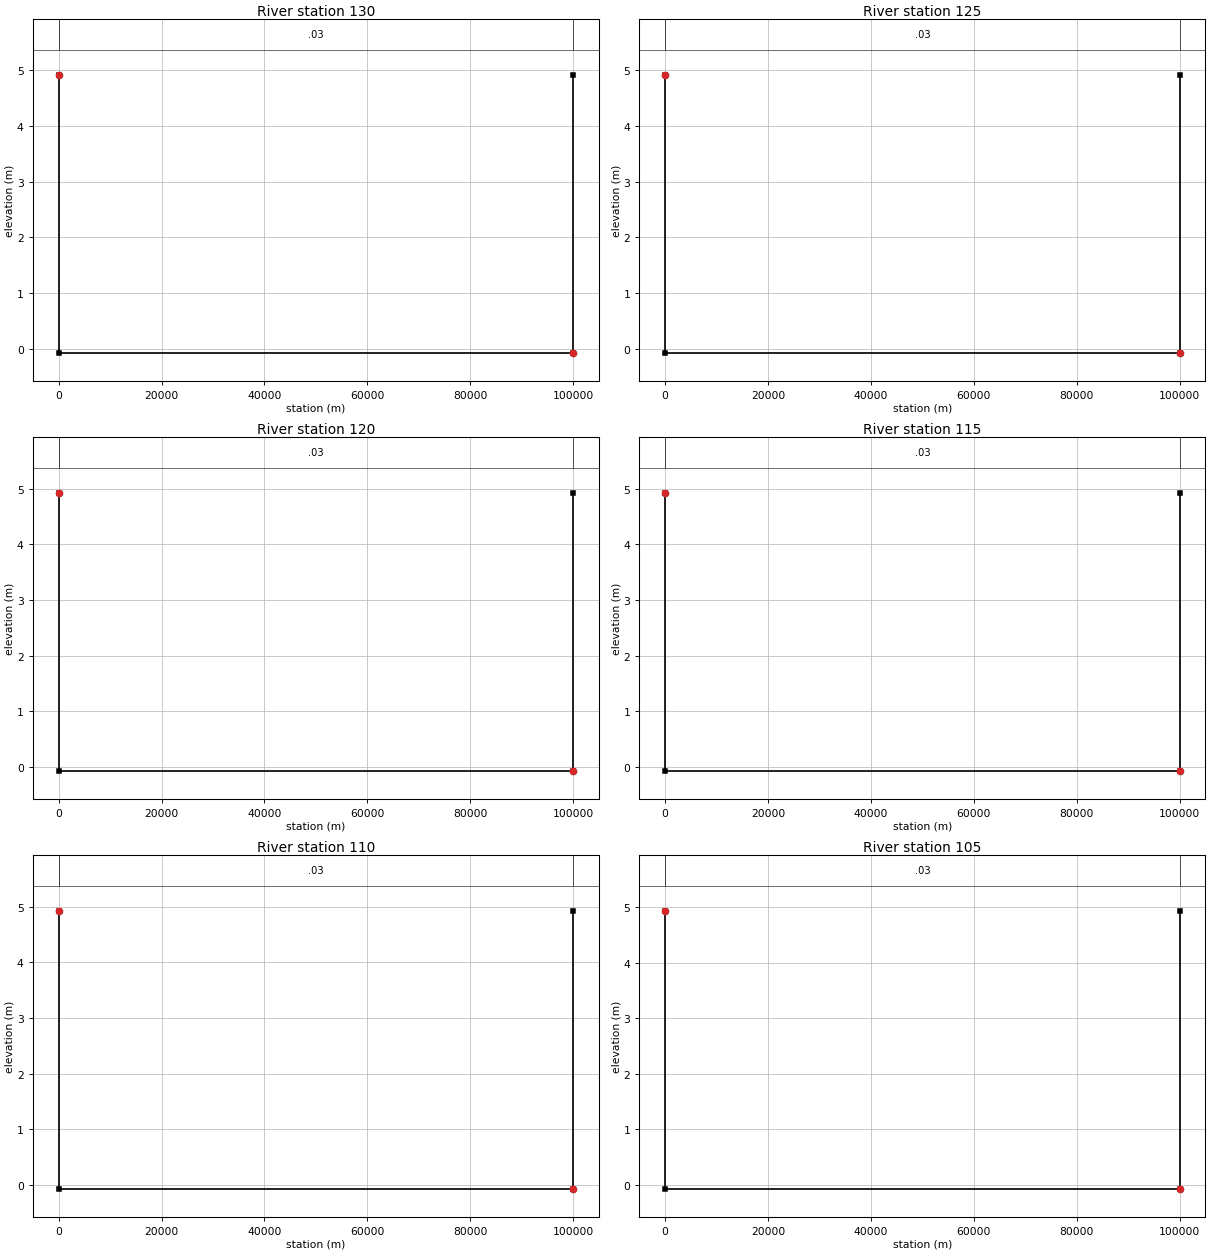
Type RM Length L Ch R = 1 ,130     ,5,5,5
#Sta/Elev= 4
 0.00000 4.91979 0.00000-0.08021  100000-0.08021  100000 4.91979
#Mann= 3 ,0,0
 0.00000 0.03000 0.00000 0.00000 0.03000 0.00000  100000 0.03000 0.00000
Bank Sta=0,100000
XS Rating Curve= 0 ,0
Exp/Cntr=0,0

Type RM Length L Ch R = 1 ,125     ,5,5,5
#Sta/Elev= 4
 0.00000 4.92176 0.00000-0.07824  100000-0.07824  100000 4.92176
#Mann= 3 ,0,0
 0.00000 0.03000 0.00000 0.00000 0.03000 0.00000  100000 0.03000 0.00000
Bank Sta=0,100000
XS Rating Curve= 0 ,0
Exp/Cntr=0,0

Type RM Length L Ch R = 1 ,120     ,5,5,5
#Sta/Elev= 4
 0.00000 4.92362 0.00000-0.07638  100000-0.07638  100000 4.92362
#Mann= 3 ,0,0
 0.00000 0.03000 0.00000 0.00000 0.03000 0.00000  100000 0.03000 0.00000
Bank Sta=0,100000
XS Rating Curve= 0 ,0
Exp/Cntr=0,0

Type RM Length L Ch R = 1 ,115     ,5,5,5
#Sta/Elev= 4
 0.00000 4.92537 0.00000-0.07463  100000-0.07463  100000 4.92537
#Mann= 3 ,0,0
 0.00000 0.03000 0.00000 0.00000 0.03000 0.00000  100000 0.03000 0.00000
Bank Sta=0,100000
XS Rating Curve= 0 ,0
Exp/Cntr=0,0

Type RM Length L Ch R = 1 ,110     ,5,5,5
#Sta/Elev= 4
 0.00000 4.92701 0.00000-0.07299  100000-0.07299  100000 4.92701
#Mann= 3 ,0,0
 0.00000 0.03000 0.00000 0.00000 0.03000 0.00000  100000 0.03000 0.00000
Bank Sta=0,100000
XS Rating Curve= 0 ,0
Exp/Cntr=0,0

Type RM Length L Ch R = 1 ,105     ,5,5,5
#Sta/Elev= 4
 0.00000 4.92854 0.00000-0.07146  100000-0.07146  100000 4.92854
#Mann= 3 ,0,0
 0.00000 0.03000 0.00000 0.00000 0.03000 0.00000  100000 0.03000 0.00000
Bank Sta=0,100000
XS Rating Curve= 0 ,0
Exp/Cntr=0,0

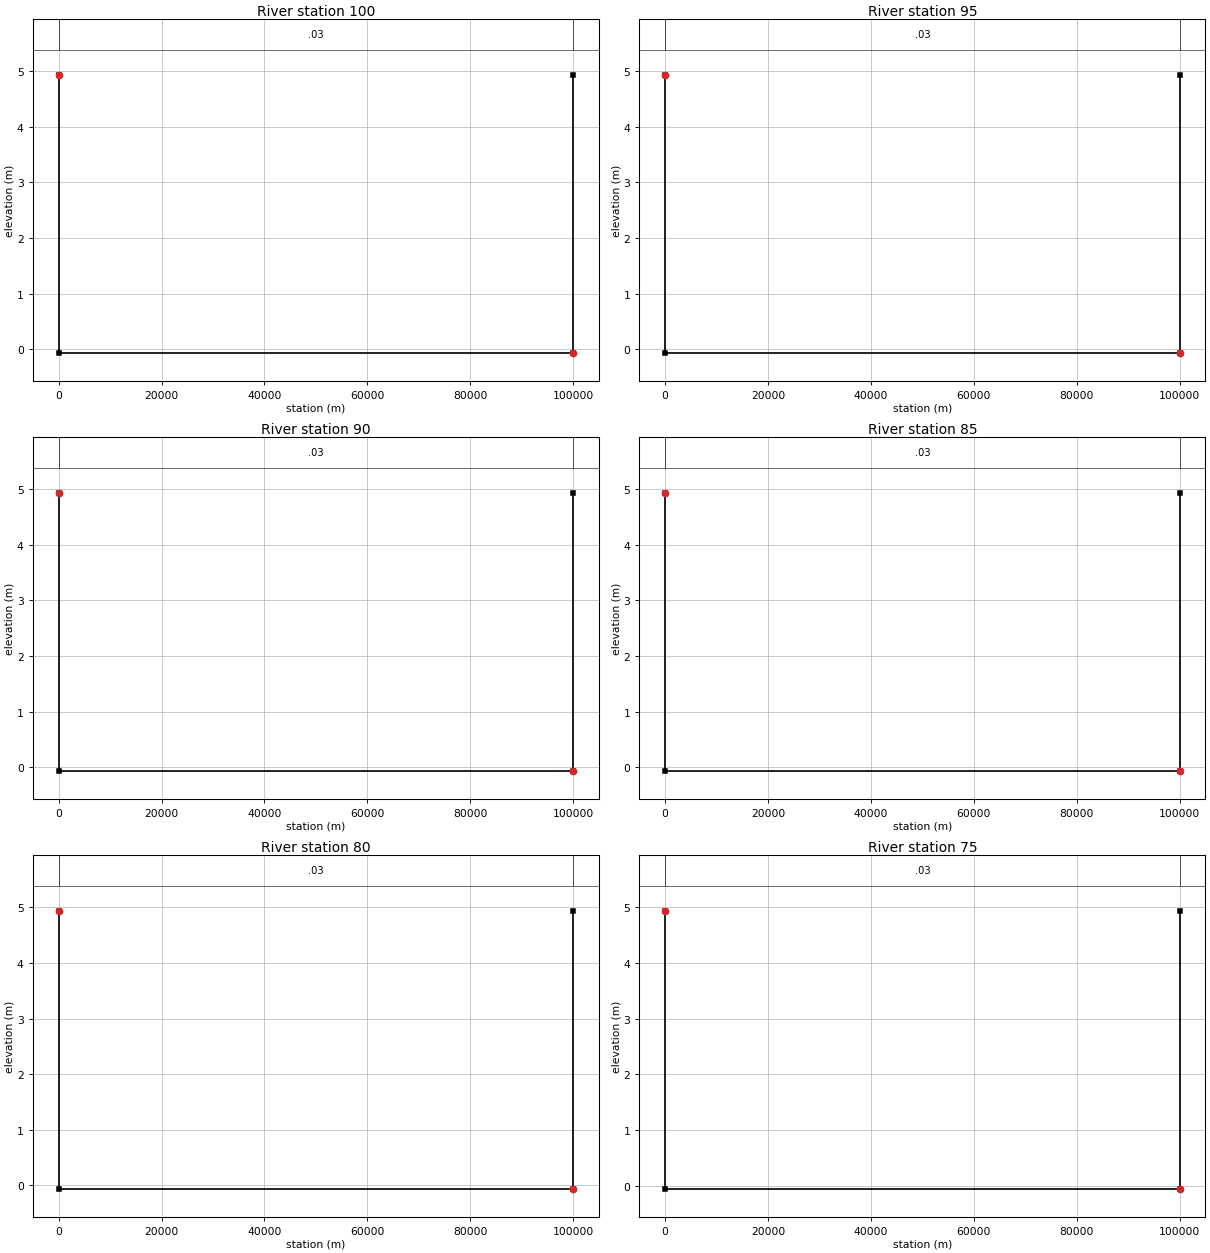
Type RM Length L Ch R = 1 ,100     ,5,5,5
#Sta/Elev= 4
 0.00000 4.92998 0.00000-0.07002  100000-0.07002  100000 4.92998
#Mann= 3 ,0,0
 0.00000 0.03000 0.00000 0.00000 0.03000 0.00000  100000 0.03000 0.00000
Bank Sta=0,100000
XS Rating Curve= 0 ,0
Exp/Cntr=0,0

Type RM Length L Ch R = 1 ,95      ,5,5,5
#Sta/Elev= 4
 0.00000 4.93132 0.00000-0.06868  100000-0.06868  100000 4.93132
#Mann= 3 ,0,0
 0.00000 0.03000 0.00000 0.00000 0.03000 0.00000  100000 0.03000 0.00000
Bank Sta=0,100000
XS Rating Curve= 0 ,0
Exp/Cntr=0,0

Type RM Length L Ch R = 1 ,90      ,5,5,5
#Sta/Elev= 4
 0.00000 4.93257 0.00000-0.06743  100000-0.06743  100000 4.93257
#Mann= 3 ,0,0
 0.00000 0.03000 0.00000 0.00000 0.03000 0.00000  100000 0.03000 0.00000
Bank Sta=0,100000
XS Rating Curve= 0 ,0
Exp/Cntr=0,0

Type RM Length L Ch R = 1 ,85      ,5,5,5
#Sta/Elev= 4
 0.00000 4.93372 0.00000-0.06628  100000-0.06628  100000 4.93372
#Mann= 3 ,0,0
 0.00000 0.03000 0.00000 0.00000 0.03000 0.00000  100000 0.03000 0.00000
Bank Sta=0,100000
XS Rating Curve= 0 ,0
Exp/Cntr=0,0

Type RM Length L Ch R = 1 ,80      ,5,5,5
#Sta/Elev= 4
 0.00000 4.93479 0.00000-0.06521  100000-0.06521  100000 4.93479
#Mann= 3 ,0,0
 0.00000 0.03000 0.00000 0.00000 0.03000 0.00000  100000 0.03000 0.00000
Bank Sta=0,100000
XS Rating Curve= 0 ,0
Exp/Cntr=0,0

Type RM Length L Ch R = 1 ,75      ,5,5,5
#Sta/Elev= 4
 0.00000 4.93578 0.00000-0.06422  100000-0.06422  100000 4.93578
#Mann= 3 ,0,0
 0.00000 0.03000 0.00000 0.00000 0.03000 0.00000  100000 0.03000 0.00000
Bank Sta=0,100000
XS Rating Curve= 0 ,0
Exp/Cntr=0,0

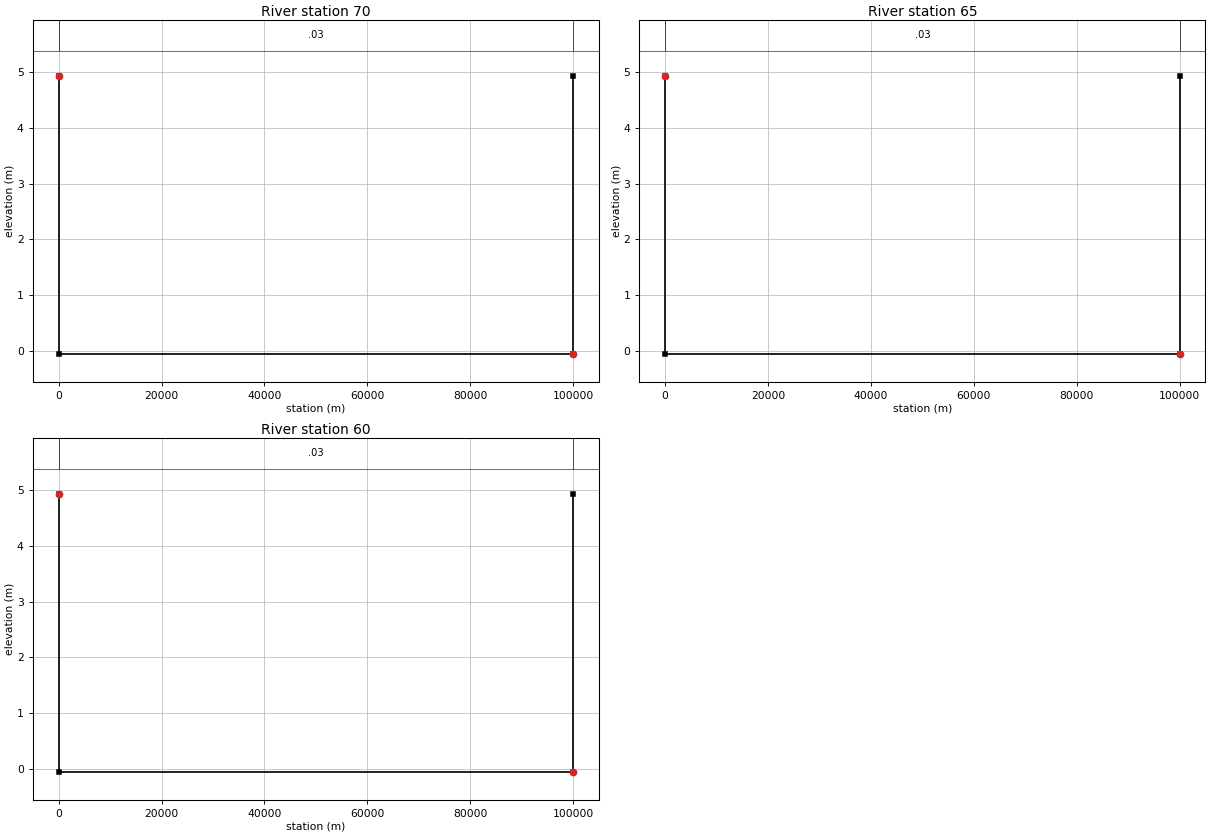
Type RM Length L Ch R = 1 ,70      ,5,5,5
#Sta/Elev= 4
 0.00000 4.93668 0.00000-0.06332  100000-0.06332  100000 4.93668
#Mann= 3 ,0,0
 0.00000 0.03000 0.00000 0.00000 0.03000 0.00000  100000 0.03000 0.00000
Bank Sta=0,100000
XS Rating Curve= 0 ,0
Exp/Cntr=0,0

Type RM Length L Ch R = 1 ,65      ,5,5,5
#Sta/Elev= 4
 0.00000  4.9375 0.00000-0.06250  100000-0.06250  100000  4.9375
#Mann= 3 ,0,0
 0.00000 0.03000 0.00000 0.00000 0.03000 0.00000  100000 0.03000 0.00000
Bank Sta=0,100000
XS Rating Curve= 0 ,0
Exp/Cntr=0,0

Type RM Length L Ch R = 1 ,60      ,5,5,5
#Sta/Elev= 4
 0.00000 4.93826 0.00000-0.06174  100000-0.06174  100000 4.93826
#Mann= 3 ,0,0
 0.00000 0.03000 0.00000 0.00000 0.03000 0.00000  100000 0.03000 0.00000
Bank Sta=0,100000
XS Rating Curve= 0 ,0
Exp/Cntr=0,0