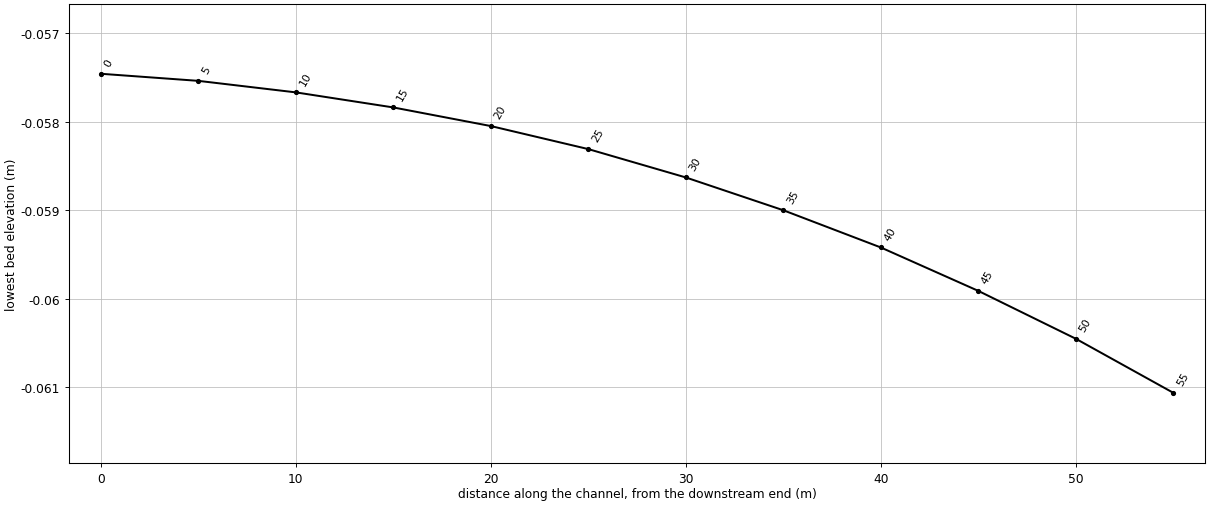
HEC-RAS study macdonald.prj: A1F-001 MacDonald backwater dx=5 m

--- macdonald.g01 (geometry) --- (continued)

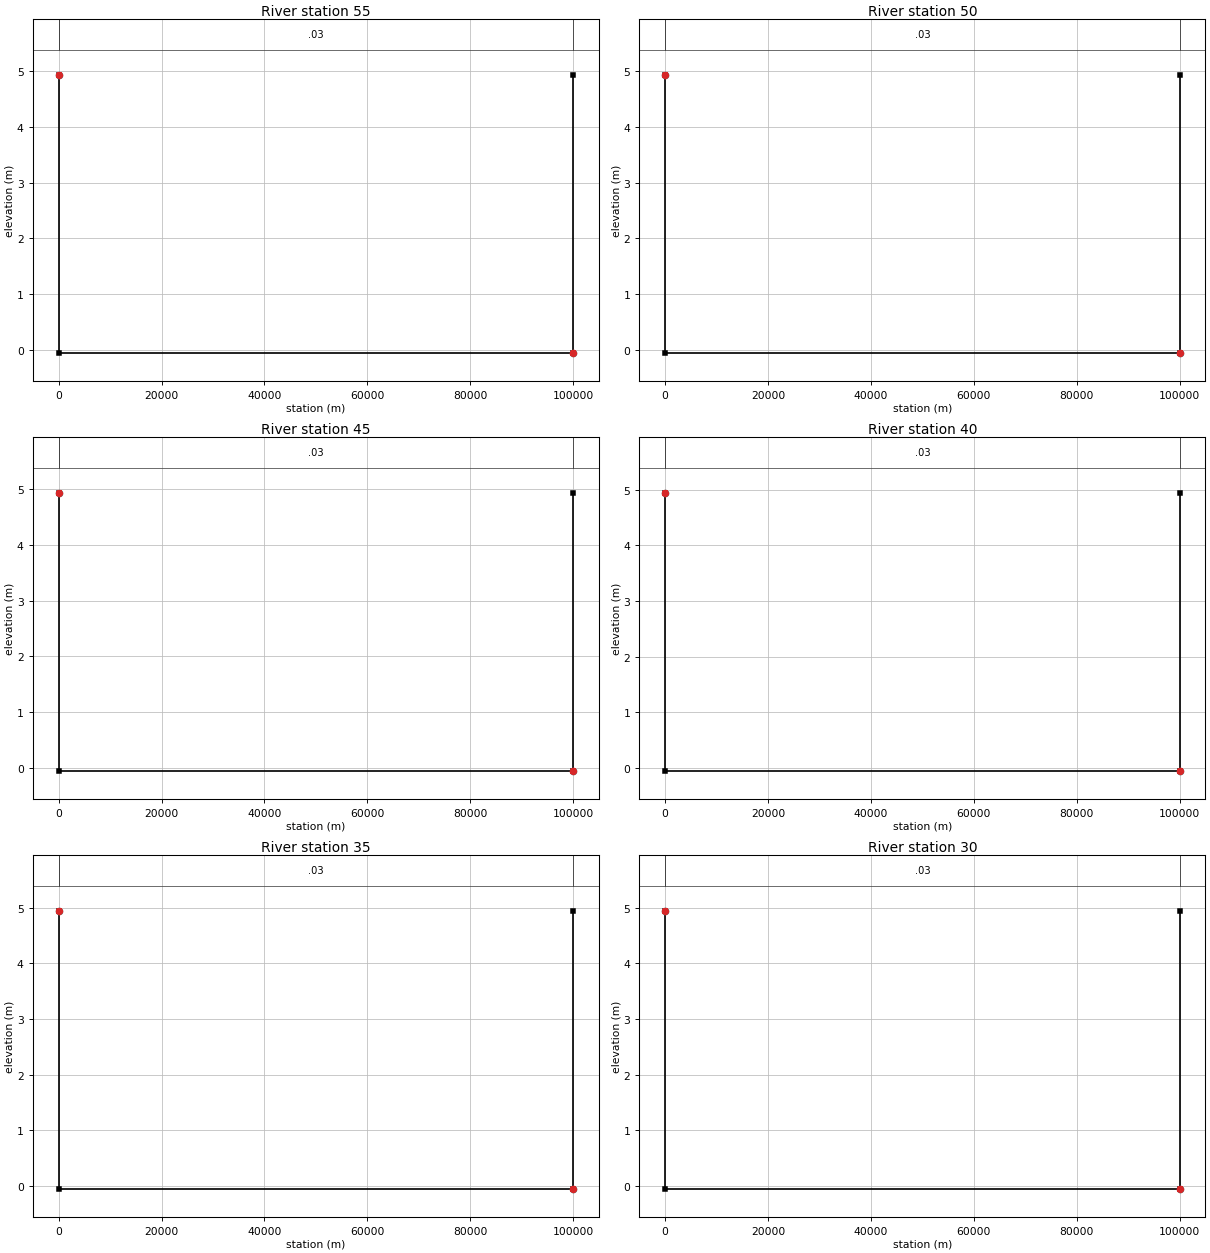
Type RM Length L Ch R = 1 ,55      ,5,5,5
#Sta/Elev= 4
 0.00000 4.93894 0.00000-0.06106  100000-0.06106  100000 4.93894
#Mann= 3 ,0,0
 0.00000 0.03000 0.00000 0.00000 0.03000 0.00000  100000 0.03000 0.00000
Bank Sta=0,100000
XS Rating Curve= 0 ,0
Exp/Cntr=0,0

Type RM Length L Ch R = 1 ,50      ,5,5,5
#Sta/Elev= 4
 0.00000 4.93955 0.00000-0.06045  100000-0.06045  100000 4.93955
#Mann= 3 ,0,0
 0.00000 0.03000 0.00000 0.00000 0.03000 0.00000  100000 0.03000 0.00000
Bank Sta=0,100000
XS Rating Curve= 0 ,0
Exp/Cntr=0,0

Type RM Length L Ch R = 1 ,45      ,5,5,5
#Sta/Elev= 4
 0.00000 4.94009 0.00000-0.05991  100000-0.05991  100000 4.94009
#Mann= 3 ,0,0
 0.00000 0.03000 0.00000 0.00000 0.03000 0.00000  100000 0.03000 0.00000
Bank Sta=0,100000
XS Rating Curve= 0 ,0
Exp/Cntr=0,0

Type RM Length L Ch R = 1 ,40      ,5,5,5
#Sta/Elev= 4
 0.00000 4.94058 0.00000-0.05942  100000-0.05942  100000 4.94058
#Mann= 3 ,0,0
 0.00000 0.03000 0.00000 0.00000 0.03000 0.00000  100000 0.03000 0.00000
Bank Sta=0,100000
XS Rating Curve= 0 ,0
Exp/Cntr=0,0

Type RM Length L Ch R = 1 ,35      ,5,5,5
#Sta/Elev= 4
 0.00000   4.941 0.00000-0.05900  100000-0.05900  100000   4.941
#Mann= 3 ,0,0
 0.00000 0.03000 0.00000 0.00000 0.03000 0.00000  100000 0.03000 0.00000
Bank Sta=0,100000
XS Rating Curve= 0 ,0
Exp/Cntr=0,0

Type RM Length L Ch R = 1 ,30      ,5,5,5
#Sta/Elev= 4
 0.00000 4.94137 0.00000-0.05863  100000-0.05863  100000 4.94137
#Mann= 3 ,0,0
 0.00000 0.03000 0.00000 0.00000 0.03000 0.00000  100000 0.03000 0.00000
Bank Sta=0,100000
XS Rating Curve= 0 ,0
Exp/Cntr=0,0

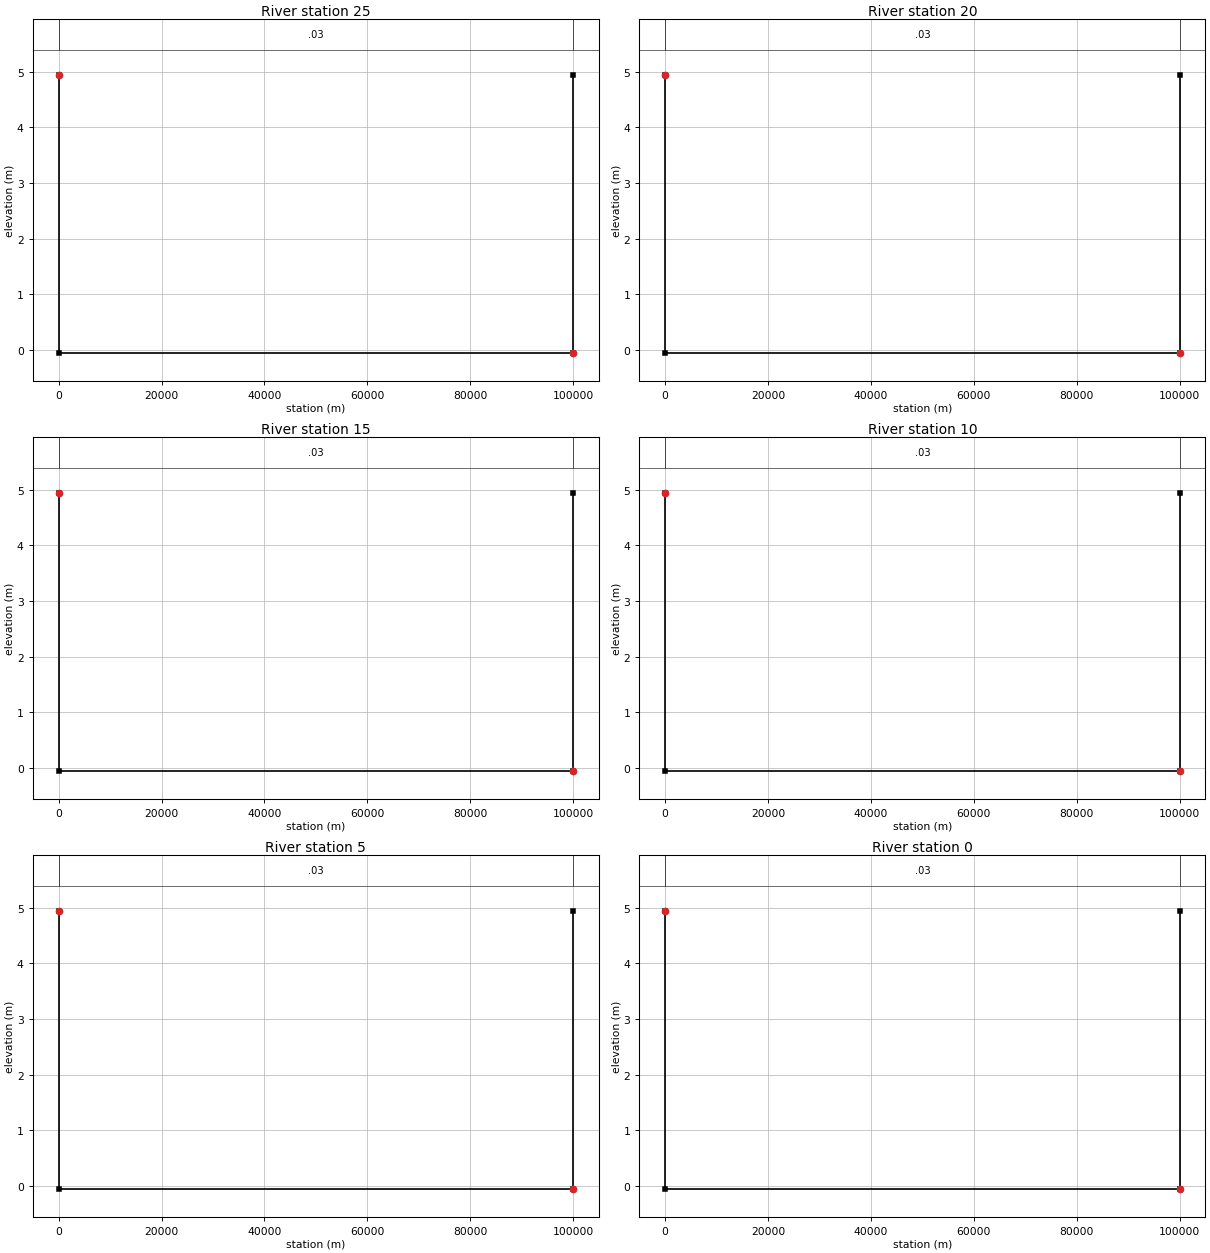
Type RM Length L Ch R = 1 ,25      ,5,5,5
#Sta/Elev= 4
 0.00000 4.94169 0.00000-0.05831  100000-0.05831  100000 4.94169
#Mann= 3 ,0,0
 0.00000 0.03000 0.00000 0.00000 0.03000 0.00000  100000 0.03000 0.00000
Bank Sta=0,100000
XS Rating Curve= 0 ,0
Exp/Cntr=0,0

Type RM Length L Ch R = 1 ,20      ,5,5,5
#Sta/Elev= 4
 0.00000 4.94195 0.00000-0.05805  100000-0.05805  100000 4.94195
#Mann= 3 ,0,0
 0.00000 0.03000 0.00000 0.00000 0.03000 0.00000  100000 0.03000 0.00000
Bank Sta=0,100000
XS Rating Curve= 0 ,0
Exp/Cntr=0,0

Type RM Length L Ch R = 1 ,15      ,5,5,5
#Sta/Elev= 4
 0.00000 4.94216 0.00000-0.05784  100000-0.05784  100000 4.94216
#Mann= 3 ,0,0
 0.00000 0.03000 0.00000 0.00000 0.03000 0.00000  100000 0.03000 0.00000
Bank Sta=0,100000
XS Rating Curve= 0 ,0
Exp/Cntr=0,0

Type RM Length L Ch R = 1 ,10      ,5,5,5
#Sta/Elev= 4
 0.00000 4.94233 0.00000-0.05767  100000-0.05767  100000 4.94233
#Mann= 3 ,0,0
 0.00000 0.03000 0.00000 0.00000 0.03000 0.00000  100000 0.03000 0.00000
Bank Sta=0,100000
XS Rating Curve= 0 ,0
Exp/Cntr=0,0

Type RM Length L Ch R = 1 ,5       ,5,5,5
#Sta/Elev= 4
 0.00000 4.94246 0.00000-0.05754  100000-0.05754  100000 4.94246
#Mann= 3 ,0,0
 0.00000 0.03000 0.00000 0.00000 0.03000 0.00000  100000 0.03000 0.00000
Bank Sta=0,100000
XS Rating Curve= 0 ,0
Exp/Cntr=0,0

Type RM Length L Ch R = 1 ,0       ,0,0,0
#Sta/Elev= 4
 0.00000 4.94254 0.00000-0.05746  100000-0.05746  100000 4.94254
#Mann= 3 ,0,0
 0.00000 0.03000 0.00000 0.00000 0.03000 0.00000  100000 0.03000 0.00000
Bank Sta=0,100000
XS Rating Curve= 0 ,0
Exp/Cntr=0,0